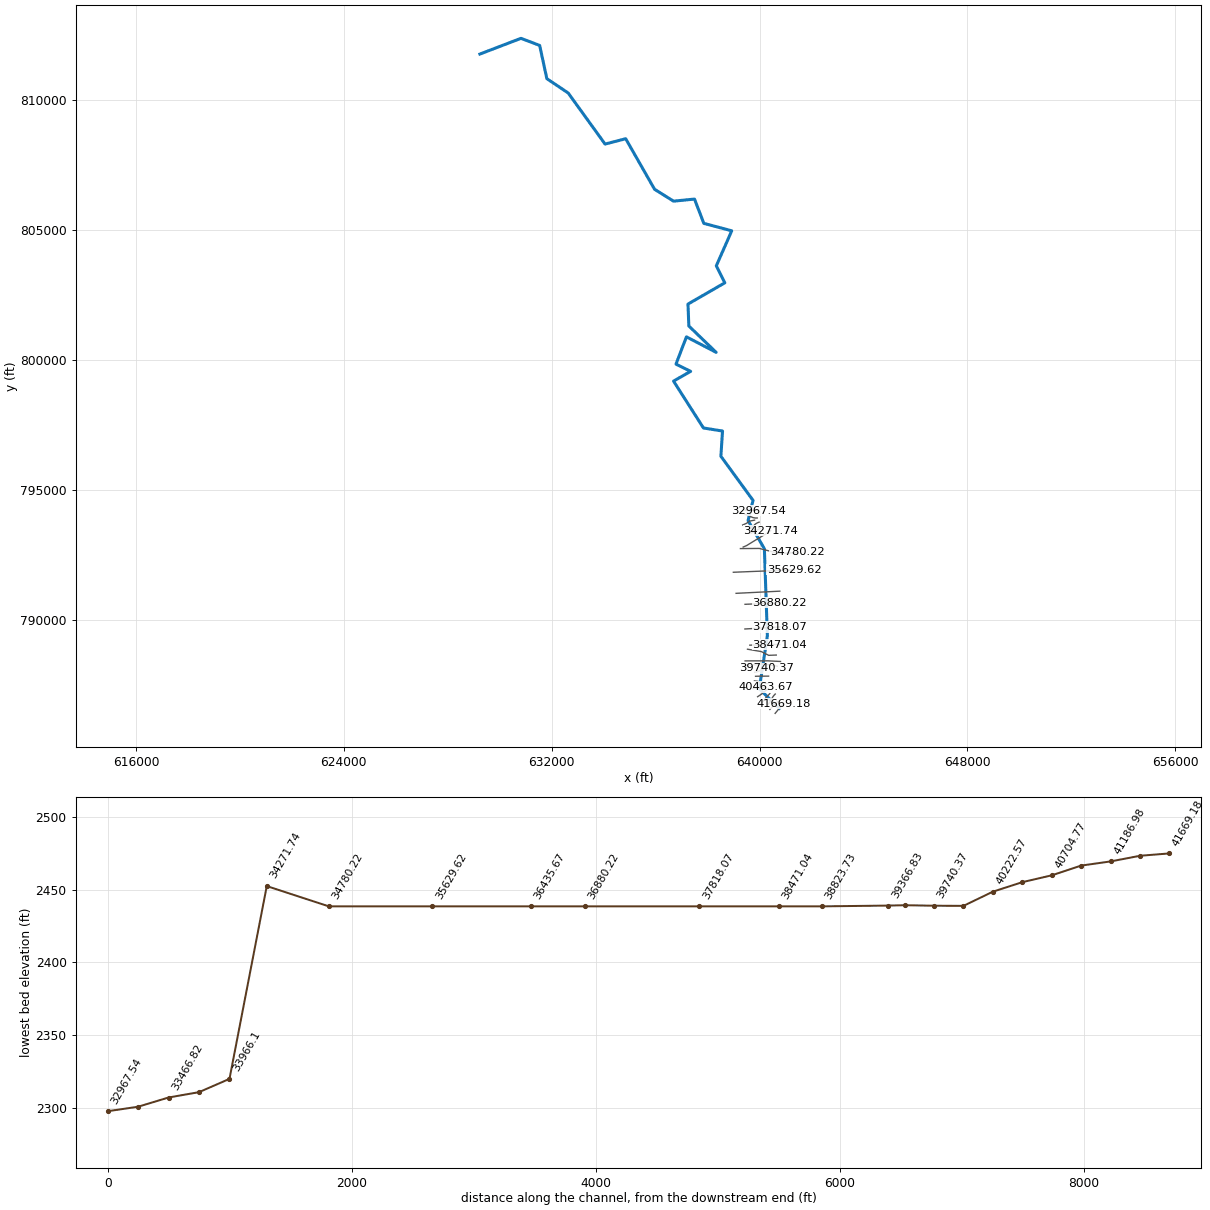
--- 12582_ras.prj (project) ---

Proj Title=12582
Current Plan=p01
Default Exp/Contr=0.3,0.1
English Units
Geom File=g01
Flow File=f01
Plan File=p01
Y Axis Title=Elevation
X Axis Title(PF)=Main Channel Distance
X Axis Title(XS)=Station
BEGIN DESCRIPTION:
RFD model 12582 exported to HEC-RAS
END DESCRIPTION:

--- 12582_ras.p01 (plan) ---

Plan Title=Plan 01
Program Version=4.10
Short Identifier=Plan 01
Geom File=g01
Flow File=f01
Subcritical Flow
Calc Critical at every XS
Secant Critical Depth

--- 12582_ras.f01 (steady flow) ---

Flow Title=Flow 01
Program Version=5.01
Number of Profiles= 6
Profile Names=10yr,25yr,50yr,100yr,100plus,500yr
River Rch & RM=12582,160,41669.18
 2351.98 3652.88  4847.5  5877.5 8581.15 9899.51
River Rch & RM=12582,160,41428.08
 2355.03 3657.65 4853.86 5885.25 8592.46  9910.8
River Rch & RM=12582,160,41186.98
 2373.85  3687.1 4893.17 5933.08  8662.3 9980.51
River Rch & RM=12582,160,40945.88
 2376.89 3691.86 4899.52 5940.81 8673.59 9991.77
River Rch & RM=12582,160,40704.77
 2420.59 3759.97  4990.2  6050.9 8834.32 10150.9
River Rch & RM=12582,160,40463.67
  2435.6  3783.4 5021.42 6088.84 8889.7110205.76
River Rch & RM=12582,160,40222.57
 2439.74 3789.87 5030.05 6099.34 8905.0410220.98
River Rch & RM=12582,160,39981.47
 2443.59  3795.9  5038.1 6109.14 8919.3410235.17
River Rch & RM=12582,160,39740.37
 2448.55 3803.66 5048.45 6121.73 8937.7210253.41
River Rch & RM=12582,160,39499.27
 2472.74  3841.5 5098.95 6183.18 9027.44 10342.4
River Rch & RM=12582,160,39366.83
 2810.11 4365.22 5794.41 7025.4310257.1311535.44
River Rch & RM=12582,160,38823.73
 2818.16  4377.8  5811.2 7045.8610286.9511564.44
River Rch & RM=12582,160,38471.04
 2989.43 4645.16 6167.55 7478.8310919.09 12174.6
River Rch & RM=12582,160,37818.07
 3076.12 4780.63 6348.24  7698.511239.81 12482.7
River Rch & RM=12582,160,36880.22
 3249.88 5051.31 6708.55 8135.7211878.1513089.23
River Rch & RM=12582,160,36435.67
 3458.83 5377.64 7143.69  8664.512650.18 13819.4
River Rch & RM=12582,160,35629.62
 3523.37 5478.25  7277.7 8827.1812887.6914042.11
River Rch & RM=12582,160,34780.22
 3537.09 5499.66 7306.23 8861.8312938.2814089.53
River Rch & RM=12582,160,34271.74
 3606.08  5607.4 7449.89  9036.413193.1514328.34
River Rch & RM=12582,160, 33966.1
 3623.85 5635.12 7486.85 9081.2913258.6814389.58
River Rch & RM=12582,160,33716.46
 3654.29 5682.59 7550.08 9158.0513370.7614494.06
River Rch & RM=12582,160,33466.82
 3735.16 5808.65 7717.97 9361.8313668.2714770.65
River Rch & RM=12582,160,33217.18
 3739.51 5815.43 7727.01 9372.81 13684.314785.57
River Rch & RM=12582,160,32967.54
 3744.87 5823.81 7738.18 9386.3713704.1114803.99
River Rch & RM=12582,160, 32717.9
 3754.58 5838.96 7758.38 9410.9113739.93 14837.3
River Rch & RM=12582,160,32468.26
 3764.01 5853.68 7778.02 9434.7713774.77 14869.7
River Rch & RM=12582,160,32218.61
 3767.58 5859.25 7785.44 9443.7913787.9414881.95
River Rch & RM=12582,160,31968.97
 3778.76 5876.72 7808.75 9472.12 13829.314920.43
River Rch & RM=12582,160,31719.33
 3864.66 6010.86 7987.61 9689.4414146.5815214.76
River Rch & RM=12582,160,31469.69
 4065.62 6325.85 8408.6910202.1814895.1915909.52
River Rch & RM=12582,160,31220.05
 4070.59 6333.64 8419.0810214.8414913.6615926.56
River Rch & RM=12582,160,30970.41
 4089.78 6363.76 8459.3810263.9514985.3715992.97
River Rch & RM=12582,160,30720.77
 4096.24 6373.87 8472.8910280.3815009.3516015.08
River Rch & RM=12582,160,30471.13
 4134.42 6433.75 8552.9710377.9215151.7716146.65
River Rch & RM=12582,160,30221.48
 4163.36 6479.27 8613.9710452.3615260.4416247.37
River Rch & RM=12582,160,29971.84
    4167 6485.01 8621.6510461.7315274.1316260.05
River Rch & RM=12582,160, 29722.2
 4170.89 6491.12 8629.8410471.7315288.7316273.57
River Rch & RM=12582,160,29472.56
 4178.17 6502.58  8645.210490.4715316.0816298.91
River Rch & RM=12582,160,29222.92
 4257.26 6627.27 8812.51 10694.915614.5516575.78
River Rch & RM=12582,160,28973.28
  4265.4 6640.11 8829.7510715.96 15645.316604.28
River Rch & RM=12582,160,28723.64
 4268.96 6645.74 8837.3210725.2215658.8316616.86
River Rch & RM=12582,160,   28474
 4273.24 6652.51 8846.4110736.3515675.0716631.94
River Rch & RM=12582,160,28238.08
 4288.46 6676.55 8878.7210775.8715732.7616685.51
River Rch & RM=12582,160,28109.87
 4317.91 6723.19 8941.4710852.7315844.9816789.96
River Rch & RM=12582,160,27974.71
 4321.18 6728.38 8948.47 10861.3 15857.516801.64
River Rch & RM=12582,160,27725.07
 4348.01 6770.95 9005.8410931.6715960.2416897.48
River Rch & RM=12582,160,27475.43
 4381.82 6824.61 9078.1311020.3216089.6617018.02
River Rch & RM=12582,160,27225.79
 4386.22 6831.59 9087.5511031.8916106.5617033.79
River Rch & RM=12582,160,26976.15
 4403.04 6858.36 9123.6811076.2616171.3517094.33
River Rch & RM=12582,160,26726.51
 4409.48 6868.62 9137.5311093.2716196.1817117.53
River Rch & RM=12582,160,26476.87
 4413.38 6874.83 9145.9211103.5916211.24 17131.6
River Rch & RM=12582,160,26227.22
 4415.64 6878.44 9150.8111109.6116220.0317139.88
River Rch & RM=12582,160,25977.58
 4417.64 6881.66 9155.1811115.0116227.9117147.33
River Rch & RM=12582,160,25727.94
 4420.79 6886.69 9162.0111123.42 16240.217158.92
River Rch & RM=12582,160,25228.66
 4421.01 6887.05  9162.511124.0316241.0817159.75
River Rch & RM=12582,160,24479.74
 4441.12 6919.31 9206.2711178.0316319.9217234.15
River Rch & RM=12582,160,23980.45
 4456.77 6944.51 9240.5311220.3916381.7717292.76
River Rch & RM=12582,160,23730.81
 4459.01  6948.1  9245.411226.3916390.5317301.01
River Rch & RM=12582,160,23481.17
 4464.96 6957.68 9258.4211242.4916414.0417323.28
River Rch & RM=12582,160,23231.53
 4466.92 6960.85 9262.7311247.8316421.8317330.69
River Rch & RM=12582,160,22981.89
 4468.66 6963.66 9266.5611252.5716428.7617337.29
River Rch & RM=12582,160,22732.25
 4470.43  6966.5 9270.4211257.3516435.7317343.88
River Rch & RM=12582,160,22482.61
 4474.46 6972.96 9279.1811268.1416451.4917358.71
River Rch & RM=12582,160,22232.96
 4479.83 6981.56 9290.8511282.53 16472.517378.47
River Rch & RM=12582,160,21983.32
 4496.35 7007.95 9326.5511326.4816536.6617438.54
River Rch & RM=12582,160,21733.68
 4506.32 7023.87 9348.0811352.9716575.34 17474.7
River Rch & RM=12582,160,21486.98
 4509.48 7028.92 9354.9111361.3816587.62 17486.2
River Rch & RM=12582,160,21248.25
 4511.23 7031.74 9358.7611366.1416594.5617492.77
River Rch & RM=12582,160,20998.61
 4512.77 7034.21 9362.1211370.2916600.6317498.52
River Rch & RM=12582,160,20748.97
 4514.51 7037.02 9365.9511375.0316607.5517505.09
River Rch & RM=12582,160,20499.32
  4691.8 7320.62 9750.04 11848.217298.3818150.68
River Rch & RM=12582,160,20307.65
 4693.09 7322.71 9752.8811851.7217303.5218155.53
River Rch & RM=12582,160,20167.11
 4693.95  7324.1 9754.7811854.0717306.9418158.77
River Rch & RM=12582,160,20060.48
 4700.59 7334.84 9769.4311872.2317333.4618183.85
River Rch & RM=12582,160,19905.63
 4701.45 7336.23 9771.3311874.5817336.8818187.09
River Rch & RM=12582,160,19745.49
  4710.7 7351.17 9791.69 11899.817373.7118221.85
River Rch & RM=12582,160,19495.85
 4714.14 7356.73 9799.2611909.18 17387.418234.78
River Rch & RM=12582,160,19384.27
  4735.9 7392.06 9847.5611969.1617474.9718317.92
River Rch & RM=12582,160,19246.21
 4740.78 7399.97 9858.3611982.5717494.5518336.46
River Rch & RM=12582,160,18996.56
 4744.76 7406.45 9867.2211993.5917510.6418351.78
River Rch & RM=12582,160,18746.92
 4751.07  7416.7 9881.2512011.0217536.0918375.95
River Rch & RM=12582,160,18497.28
 4755.06 7423.19 9890.1312022.0517552.1918391.25
River Rch & RM=12582,160,18247.64
 4759.67 7430.69 9900.3912034.8117570.8218408.97
River Rch & RM=12582,160, 17965.3
 4764.96 7439.26  9912.112049.3517592.0518429.08
River Rch & RM=12582,160,17748.36
 4765.58 7440.29  9913.512051.0917594.59 18431.5
River Rch & RM=12582,160,17611.88
 4766.42 7441.65 9915.3612053.4117597.9818434.72
River Rch & RM=12582,160,17546.79
 4768.93 7445.74 9920.9612060.3617608.1318444.37
River Rch & RM=12582,160,17281.29
 4784.77 7471.34 9955.86 12103.617671.2618503.85
River Rch & RM=12582,160,17234.09
 4810.79 7513.4210013.2512174.7417775.1218601.75
River Rch & RM=12582,160,16975.19
 4824.99 7536.5110044.8612214.04 17832.518656.23
River Rch & RM=12582,160,16725.54
 4828.53 7542.2910052.7612223.8717846.8518669.84
River Rch & RM=12582,160,16568.33
 4829.37 7543.6410054.6212226.1817850.2218673.04
River Rch & RM=12582,160,16475.19
 4834.59 7552.1310066.2412240.6217871.3118693.05
River Rch & RM=12582,160,16348.69
  4837.3 7556.5510072.2812248.1317882.2818703.45
River Rch & RM=12582,160,16225.55
 4841.65 7563.64   1008212260.2317899.9418720.25
River Rch & RM=12582,160,16090.31
 4842.88 7565.6510084.7512263.6717904.9618725.04
River Rch & RM=12582,160,15977.68
 4844.51 7568.3110088.4212268.2517911.6418731.44
River Rch & RM=12582,160,15920.83
  4849.2    757610098.9812281.4217930.8718749.82
River Rch & RM=12582,160, 15791.4
 4850.01 7577.3310100.8112283.7117934.2118753.02
River Rch & RM=12582,160,   15633
 4851.24 7579.3310103.5612287.1417939.2218757.81
River Rch & RM=12582,160,15443.75
 4857.15 7589.0110116.8612303.7317963.4518780.98
River Rch & RM=12582,160,15194.11
 4859.59 7593.0210122.36 12310.617973.4818790.56
River Rch & RM=12582,160,14944.47
 4867.14 7605.3710139.3412331.7818004.39 18820.1
River Rch & RM=12582,160,14694.83
 5012.41 7843.1810466.0812739.4118599.5419387.31
River Rch & RM=12582,160,14381.54
 5021.98 7858.9210487.7712766.5218639.1319425.15
River Rch & RM=12582,160,14195.54
 5024.18 7862.5410492.7512772.7518648.2119433.82
River Rch & RM=12582,160, 13945.9
  5030.8 7873.3910507.6912791.4218675.4719459.82
River Rch & RM=12582,160,13696.26
 5037.19  7883.910522.1512809.4918701.8619485.01
River Rch & RM=12582,160,13446.62
 5043.19 7893.7610535.7212826.4518726.6219508.62
River Rch & RM=12582,160,13196.98
 5045.57 7897.6710541.11 12833.218736.4819518.06
River Rch & RM=12582,160,12947.34
 5214.28 8173.5510919.9713305.62 19426.220170.65
River Rch & RM=12582,160,12807.27
    5256 8242.2111014.6113424.0319599.0820335.01
River Rch & RM=12582,160,12643.98
 5258.55  8246.411020.3913431.2719609.6620345.07
River Rch & RM=12582,160, 12446.2
 5278.24 8278.8811065.2313487.4419691.6620423.18
River Rch & RM=12582,160,12287.73
 5284.65 8289.4611079.8413505.75 19718.420448.68
River Rch & RM=12582,160,12045.57
 5292.25 8301.9911097.1413527.4219750.0420478.79
River Rch & RM=12582,160,11809.48
 5305.71 8324.1811127.7613565.7719806.0320532.03
River Rch & RM=12582,160, 11573.4
 5309.85 8330.9911137.1313577.4819823.1320548.22
River Rch & RM=12582,160,11337.31
 5339.64 8379.91 11204.513661.6819946.06 20664.5
River Rch & RM=12582,160,11101.22
    5342 8383.7911209.8513668.3719955.8320673.73
River Rch & RM=12582,160,10865.14
 5349.28 8395.7511226.3213688.97 19985.920702.18
River Rch & RM=12582,160,10629.05
 5354.72 8404.72 11238.713704.4820008.5520723.69
River Rch & RM=12582,160,10392.96
 5365.65 8422.7211263.5313735.5620053.91 20766.7
River Rch & RM=12582,160,10156.88
 5419.08 8510.5911384.6313887.0420275.0820975.88
River Rch & RM=12582,160, 9920.79
 5426.99 8523.6611402.6813909.6720308.1121007.22
River Rch & RM=12582,160,9684.703
 5440.05 8545.2411432.5113947.0920362.7521059.16
River Rch & RM=12582,160,9448.616
 5449.97 8561.6611455.2513975.6320404.4221098.85
River Rch & RM=12582,160,9212.529
 5457.02 8573.3511471.4213995.9320434.0621127.07
River Rch & RM=12582,160,8976.164
 5462.55  8582.511484.0814011.8420457.2821149.18
River Rch & RM=12582,160,8757.166
 5463.51 8584.0911486.2814014.59 20461.321152.99
River Rch & RM=12582,160,8559.104
 5787.38 9116.3512219.6314931.6921800.27 22409.8
River Rch & RM=12582,160,8267.069
 5794.09  9127.412234.8614950.7621828.1122435.88
River Rch & RM=12582,160,8030.704
 5800.59  9138.112249.6414969.2621855.1222461.19
River Rch & RM=12582,160,7794.339
 5806.27 9147.4912262.6114985.5321878.8722483.52
River Rch & RM=12582,160,7557.974
  5819.5 9169.3612292.8415023.4521934.2322535.59
River Rch & RM=12582,160,7321.609
 5825.95    918012307.5515041.8921961.1622560.86
River Rch & RM=12582,160,7085.244
 5834.14 9193.5112326.1915065.2421995.25 22592.8
River Rch & RM=12582,160,6848.879
 5838.34 9200.4212335.7415077.19 22012.722609.14
River Rch & RM=12582,160,6612.514
 5841.59 9205.7712343.1215086.4322026.1922621.76
River Rch & RM=12582,160,6376.149
  5874.5 9259.7512417.4115179.2422161.6922747.82
River Rch & RM=12582,160,6139.784
 5878.51 9266.3512426.5115190.6422178.3422763.38
River Rch & RM=12582,160,5903.419
 5884.44 9276.1112439.9715207.4822202.9222786.33
River Rch & RM=12582,160,5667.054
 5907.24 9313.4212491.2415271.4622296.3322872.87
River Rch & RM=12582,160,5430.689
 5907.82 9314.3712492.5515273.0922298.7222875.09
Boundary for River Rch & Prof#=12582,160,1
Up Type= 0
Dn Type= 2
Boundary for River Rch & Prof#=12582,160,2
Up Type= 0
Dn Type= 2
Boundary for River Rch & Prof#=12582,160,2
Up Type= 0
Dn Type= 2
Boundary for River Rch & Prof#=12582,160,2
Up Type= 0
Dn Type= 2
Boundary for River Rch & Prof#=12582,160,2
Up Type= 0
Dn Type= 2
Boundary for River Rch & Prof#=12582,160,2
Up Type= 0
Dn Type= 2

--- 12582_ras.g01 (geometry) ---

Geom Title=12582
Program Version=4.10

River Reach=12582,160
Reach XY= 30
640760.928171933786600.672420606 639991.21169129787353.009319156
640302.409607857 789395.93466638640186.972060829792741.252964333
639559.701274514793825.708971918639751.107524604794604.354805261
638512.826274514796302.271471918638576.628357857797272.323555276
637842.253357857797390.813138589 636691.21169129799194.198555246
637350.065857857799570.500638589636784.961691201799846.542305246
 637187.30544129800897.323555261638330.534607857800300.969388589
 637279.67420581801314.623459801637247.201274514802159.042305246
638665.170024633802976.750638589638337.045024514803631.698555246
638930.578010708804978.920777485637857.661343962805263.642999694
637497.418288469 806199.84091638636691.428705066806119.111749694
635959.657871753806577.445083037634850.170536667808521.964903012
634056.226993978808316.246627644632635.348218918810283.056588948
631815.380089253810833.770057932631539.303097129812112.544198677
630819.275196373812385.392912716629238.647317976 811779.82059215

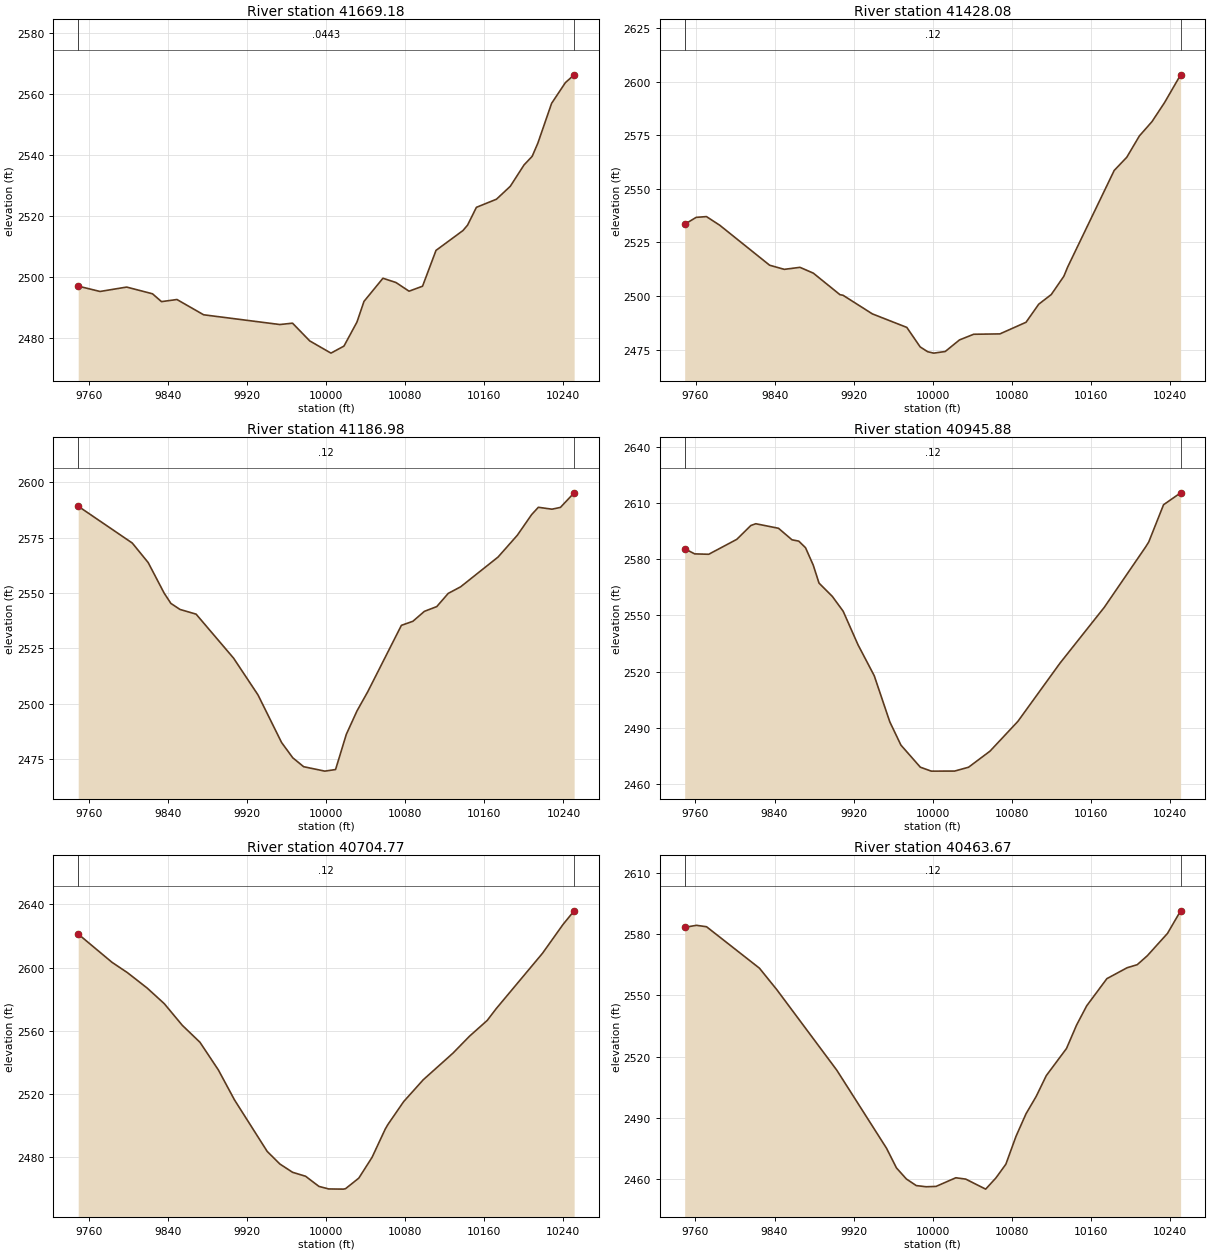
Type RM Length L Ch R = 1 ,41669.18,241.101400,241.101400,241.101400
XS GIS Cut Line= 6
640600.809315483786407.408768708 640662.82915298786481.317898056
640749.499516512786588.562681969640812.095469924786662.134445986
640873.480495365786728.364873681640931.374212291786784.591084457
#Sta/Elev= 30
9749.0042497.029 9771.082495.2729798.0762496.7149824.1852494.5159833.3072491.947
9848.9412492.6429875.9362487.642 9953.082484.4529965.9372484.8949983.3752479.083
10004.842475.08910017.992477.39310031.142485.25510038.252492.02110057.442499.601
10070.592498.21310083.882495.36910097.522496.99210111.152508.71810138.422515.214
10143.092516.99410152.052522.81910172.392525.48510186.332529.70310200.272536.701
10208.512539.52610214.212543.80910228.152556.85710242.092563.63810250.982566.199
#Mann= 3 , 0 , 0
9749.004  0.0443       09749.004  0.0443       010250.98  0.0443       0
#XS Ineff= 2 , 0
       0                               0
Bank Sta=9749.004,10250.98
Exp/Cntr=0.3,0.1

Type RM Length L Ch R = 1 ,41428.08,241.101300,241.101300,241.101300
XS GIS Cut Line= 6
640397.159905584786558.680029655640562.653184828786740.627434527
640566.889811304786744.929977076640594.944338409786774.166283042
640636.529440151786810.182979861640757.767071386786905.853058773
#Sta/Elev= 30
9749.0062533.4759760.6582536.7139771.0672537.0649784.5852533.0129834.9672514.411
9849.8292512.4839865.6922513.422 9879.212510.7169906.2452500.6619909.2762500.412
    99392491.7219973.8342485.4349987.3522476.3469994.9592474.096 10001.12473.444
10012.712474.19910027.16  2479.610041.522482.23410068.052482.40610094.512487.829
10107.322496.22610120.062500.752 10132.82509.27210136.592513.51110183.752558.569
10196.492564.72110209.232574.64810221.972581.30910234.712590.19410250.972603.128
#Mann= 3 , 0 , 0
9749.006    0.12       09749.006    0.12       010250.97    0.12       0
#XS Ineff= 2 , 0
       0                               0
Bank Sta=9749.006,10250.97
Exp/Cntr=0.3,0.1

Type RM Length L Ch R = 1 ,41186.98,241.101400,241.101400,241.101400
XS GIS Cut Line= 6
640321.031384713786741.500609642640441.125066769786896.409140292
640484.312370013 786994.90929112640514.288783575787045.838906303
640555.544549349787099.506469432640604.542640549787151.320106855
#Sta/Elev= 30
9749.0562589.2029803.7512572.5849819.8532563.7669835.9542550.0099842.8322545.313
9852.0562542.588 9868.352540.4659906.2682520.5859930.9922503.9789954.8432482.492
9966.1892475.5759977.1822471.565 9998.582469.56910009.462470.29110020.312486.156
10031.162496.78510042.012505.41610076.082535.41110087.692537.23510099.29 2541.72
10111.872543.87910123.422549.82810136.032552.81810173.872566.24910193.32 2576.07
10207.87 2585.4310214.652588.72610228.412587.86710236.982588.67110250.872595.255
#Mann= 3 , 0 , 0
9749.056    0.12       09749.056    0.12       010250.87    0.12       0
#XS Ineff= 2 , 0
       0                               0
Bank Sta=9749.056,10250.87
Exp/Cntr=0.3,0.1

Type RM Length L Ch R = 1 ,40945.88,241.101300,241.101300,241.101300
XS GIS Cut Line= 6
640063.893556019786797.870704538640166.120896626786902.665165215
640212.163597848786958.499560794640239.339063385787004.733527717
640313.476556307787078.702364725640396.525107868787171.367666771
#Sta/Elev= 30
9749.0662585.7279759.195 2582.959773.4032582.7429801.8182590.7319816.0262598.139
9821.0122599.0819844.0122596.652 9857.682590.4819864.5092589.7819871.3482586.268
9879.1792576.9099885.0162567.3139898.5192560.1729909.4492552.2619924.4422534.342
9940.8852517.7579956.6032493.1249967.8622480.6529987.5292468.812 9998.532466.697
10022.142466.719 10036.32468.77410058.012477.36410086.272493.33410128.772524.409
10173.722554.37810215.522586.65510218.672589.31510233.662609.24910250.932615.623
#Mann= 3 , 0 , 0
9749.066    0.12       09749.066    0.12       010250.93    0.12       0
#XS Ineff= 2 , 0
       0                               0
Bank Sta=9749.066,10250.93
Exp/Cntr=0.3,0.1

Type RM Length L Ch R = 1 ,40704.77,241.101400,241.101400,241.101400
XS GIS Cut Line= 6
639926.191781399787048.203146344640075.321356852787146.827157919
640179.782858162787237.549290619640228.644777317787275.564980993
 640277.62000336787308.498541825640332.678831921787340.678452496
#Sta/Elev= 30
9749.0252621.2579783.1842603.4289798.8932596.8459818.7562587.1599836.1122577.274
9854.3282563.6029872.2372552.857 9890.882535.3499907.1862516.4249940.2762483.864
9953.1092475.8919965.9432470.6539979.164 2468.139992.6632461.71910002.452460.113
10017.442459.99710019.582460.274   100332466.95210046.422480.08310059.842498.056
10062.432500.83110078.392515.31610098.212529.13610128.172545.89410145.072556.699
10162.992566.66710171.982574.037 10218.92609.095 10239.72627.34110250.962635.959
#Mann= 3 , 0 , 0
9749.025    0.12       09749.025    0.12       010250.96    0.12       0
#XS Ineff= 2 , 0
       0                               0
Bank Sta=9749.025,10250.96
Exp/Cntr=0.3,0.1

Type RM Length L Ch R = 1 ,40463.67,241.101300,241.101300,241.101300
XS GIS Cut Line= 6
 639743.27106975787350.740746887639919.140245071787380.245778192
639961.098905906787383.062414911640013.294249227787379.977407827
640041.428346919787382.079931447640237.982197223 787423.85536238
#Sta/Elev= 30
9749.0572583.341    97612584.3269771.1822583.6359824.7252563.3589842.4392552.762
9903.0492513.4379953.3522475.2699963.3752465.6669973.3932460.2639983.4042457.029
9993.4142456.44710003.452456.62710023.492460.84910033.522460.18510053.65 2455.29
10064.042460.773 10074.12467.48110084.32 2481.0810094.542492.19310104.772500.634
10114.992510.80310135.442524.07310145.662535.54610155.882544.94610176.332558.249
10196.782563.574   102072565.06110217.22 2569.4310237.672580.38310250.942591.415
#Mann= 3 , 0 , 0
9749.057    0.12       09749.057    0.12       010250.94    0.12       0
#XS Ineff= 2 , 0
       0                               0
Bank Sta=9749.057,10250.94
Exp/Cntr=0.3,0.1

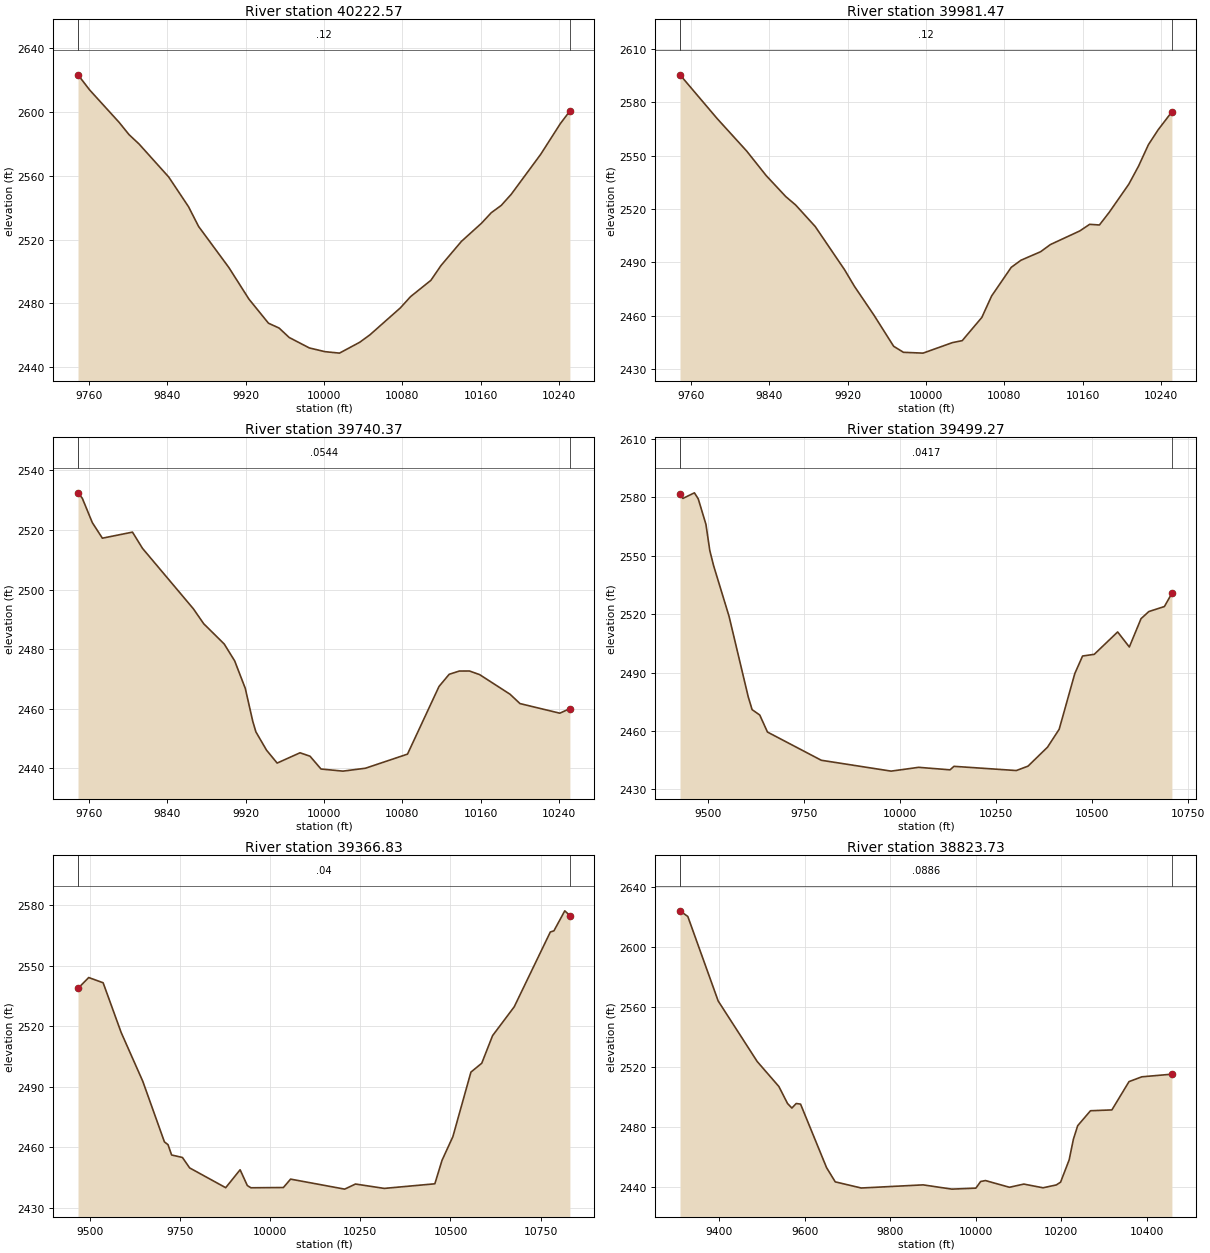
Type RM Length L Ch R = 1 ,40222.57,241.101400,241.101400,241.101400
XS GIS Cut Line= 6
639803.157353636787657.517536479639914.554947618787643.765669474
640072.843262363787606.911280935640185.617457152787575.721011817
640231.154187114787567.349886033640294.648617994787561.598672865
#Sta/Elev= 30
9749.0472623.4699760.9362613.9629791.0522593.5939801.0912585.9349811.2082580.126
9841.5632559.3479861.8062540.6759872.079 2528.299902.8962502.5499923.4412482.669
9943.3792467.5329954.258 2464.47 9964.532458.5619985.0752452.004   100012449.666
10015.842448.74310036.492455.56510046.862460.20810077.992477.17210088.36 2484.21
10109.112494.45110119.492503.79210140.242518.89810160.592530.20110170.762536.918
10180.922541.49910191.042548.43510221.172573.57510241.252592.88410250.942600.747
#Mann= 3 , 0 , 0
9749.047    0.12       09749.047    0.12       010250.94    0.12       0
#XS Ineff= 2 , 0
       0                               0
Bank Sta=9749.047,10250.94
Exp/Cntr=0.3,0.1

Type RM Length L Ch R = 1 ,39981.47,241.101400,241.101400,241.101400
XS GIS Cut Line= 5
639847.040656484787834.786711418639981.357218345787838.480462508
640096.982524514787838.890566668640098.982524514787838.890566668
640348.970496125787840.654216172
#Sta/Elev= 30
9749.0072595.332 9786.982570.7139816.9922552.5389836.9992538.6889857.0072526.882
9867.0112522.2099887.0172510.0889917.0172485.7519927.0172476.5039947.0172460.238
9967.0172442.8319977.0172439.4329997.0172438.97110027.022444.87910037.022445.988
10057.022459.02910067.022471.08810087.022487.16810097.02 2491.1810117.022495.948
10127.02 2499.9810157.02 2507.6310167.022511.33310177.02 2510.9710187.022518.076
10207.022533.89310217.022544.09910227.02 2556.0810237.022564.50310250.992574.551
#Mann= 3 , 0 , 0
9749.007    0.12       09749.007    0.12       010250.99    0.12       0
#XS Ineff= 2 , 0
       0                               0
Bank Sta=9749.007,10250.99
Exp/Cntr=0.3,0.1

Type RM Length L Ch R = 1 ,39740.37,241.101300,241.101300,241.101300
XS GIS Cut Line= 6
639810.719893036787986.895433847639890.955645971788004.495030201
639959.999199431788025.789598438640154.209948994788113.094482058
640222.324222393788131.507058228640285.162642173 788142.34180688
#Sta/Elev= 30
9749.0652532.4789753.4472530.6619763.6852522.4689773.9232517.2579804.6362519.286
9814.8742513.8389866.835 2493.53  9877.32488.549 9898.232481.7429908.8822476.094
 9919.722466.8539927.3462455.8239930.5582452.2529941.3962446.1119952.2352441.778
9975.5712445.2299985.7912444.0789997.0012439.781 10019.42439.07510042.272440.043
10085.23 2444.7810117.412467.50310127.772471.57710138.122472.66610148.482472.678
10158.842471.46210189.862464.87910200.012461.742 10240.62458.51910250.912460.055
#Mann= 3 , 0 , 0
9749.065  0.0544       09749.065  0.0544       010250.91  0.0544       0
#XS Ineff= 2 , 0
       0                               0
Bank Sta=9749.065,10250.91
Exp/Cntr=0.3,0.1

Type RM Length L Ch R = 1 ,39499.27,132.438200,132.438200,132.438200
XS GIS Cut Line= 4
 639417.53319338 788271.49477302639895.310971202788277.050328581
640100.866526723788321.494773016640684.199860068788224.272550811
#Sta/Elev= 30
9428.0612581.6459435.5282579.357 9465.532582.2319475.5312579.1159495.532 2566.04
9505.5332552.6059515.5342544.7889555.5362518.932 9605.542477.543 9615.542470.995
9635.5422468.1989655.5432459.4759795.5532444.999 9977.172439.42410048.792441.372
 10130.5 2440.0910140.642441.88610302.852439.72610333.262441.97810383.952451.702
10414.372460.91210454.922489.45210475.192498.49210505.612499.36210566.442510.845
10596.852503.12210627.262517.65210647.542521.30410688.092523.88710707.562530.669
#Mann= 3 , 0 , 0
9428.061  0.0417       09428.061  0.0417       010707.56  0.0417       0
#XS Ineff= 2 , 0
       09874.699        10209.01       0
Bank Sta=9428.061,10707.56
Exp/Cntr=0.3,0.1

Type RM Length L Ch R = 1 ,39366.83,543.101100,543.101100,543.101100
XS GIS Cut Line= 3
639445.310971172788427.050328579640309.199860097788429.828106341
640809.199860065788404.828106337
#Sta/Elev= 30
9466.7082538.7389496.3972544.1189536.3972541.5219586.3982516.8679646.3982492.655
9706.3982462.6069716.3982461.2139726.398  2456.19756.3982454.8719776.3992449.691
9876.3992439.8829916.3992448.7669936.3992440.9469946.3992439.839 10036.42439.968
 10056.42444.129 10206.42439.169 10236.42441.695 10316.42439.52710456.562441.808
10476.582453.48510506.622465.19910556.682497.20510586.722501.61310616.762515.298
10676.832529.60810776.962566.70310786.972567.28310817.012577.20210831.232574.859
#Mann= 3 , 0 , 0
9466.708    0.04       09466.708    0.04       010831.23    0.04       0
#XS Ineff= 2 , 0
       09812.527        10282.91       0
Bank Sta=9466.708,10831.23
Exp/Cntr=0.3,0.1

Type RM Length L Ch R = 1 ,38823.73,352.692500,352.692500,352.692500
XS GIS Cut Line= 4
639536.977637826788877.050328551640070.310971201788785.383661907
640353.644304514788640.939217469 640645.31097117788652.050328577
#Sta/Elev= 30
9308.263 2624.189326.5492620.3939397.576 2564.089488.8962523.7279539.6292507.059
9559.922 2495.719570.0692492.6939580.2152495.7399590.362 2495.319651.2422452.946
9671.5352443.4889732.415 2439.399877.129 2441.489944.4762438.643 10000.62439.305
10011.822443.73510023.052444.35410079.172439.88210112.842442.00310157.742439.536
10188.822441.43510198.822443.28910218.842458.07810228.842471.94310238.852480.929
10268.872490.90410318.912491.44910358.942510.31210388.962513.51710459.322515.274
#Mann= 3 , 0 , 0
9308.263  0.0886       09308.263  0.0886       010459.32  0.0886       0
#XS Ineff= 2 , 0
       0                10194.12       0
Bank Sta=9308.263,10459.32
Exp/Cntr=0.3,0.1

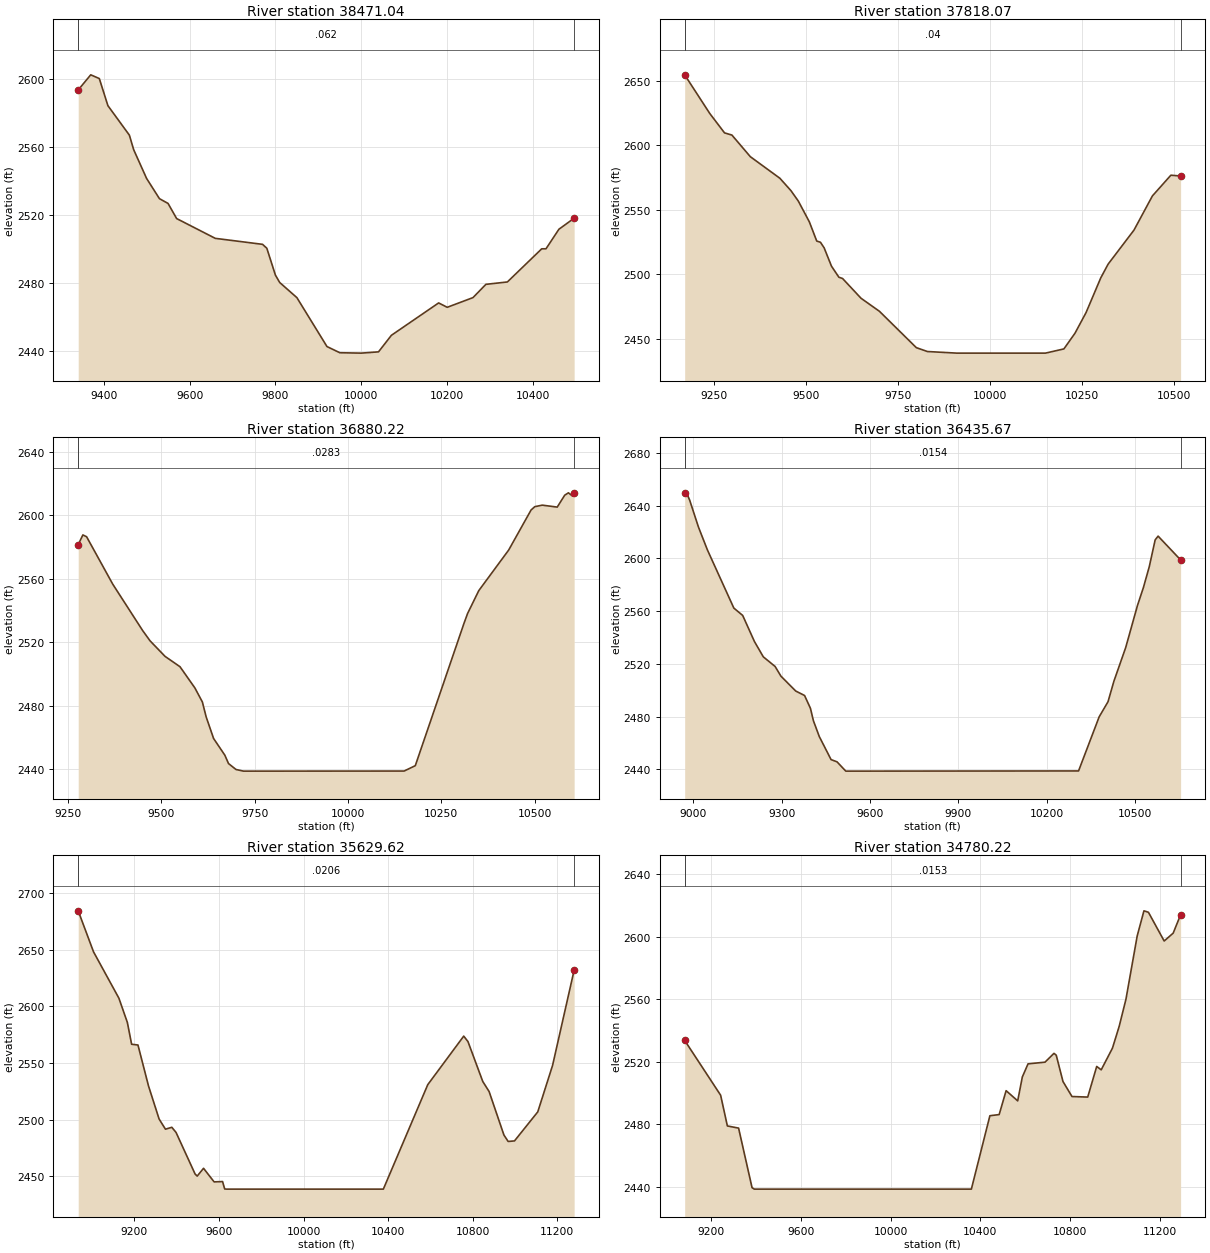
Type RM Length L Ch R = 1 ,38471.04,652.967900,652.967900,652.967900
XS GIS Cut Line= 3
639625.866526751789032.605884122640548.088748933  789060.3836619
640780.528202849789055.438141611
#Sta/Elev= 30
9340.6422593.4229369.789 2602.329389.7982600.1299409.8072584.185 9459.832566.834
9469.8342558.2979499.8482541.4179529.8612529.485 9549.872526.693 9569.882517.788
 9659.922506.146 9769.972502.6299779.9752500.3249799.9842484.5169809.9882480.176
9850.0072471.2789920.0382442.5139950.052 2438.8710000.072438.64310040.092439.387
10070.112449.12510180.162468.16610200.172465.59510260.192471.304 10290.22479.093
10340.212480.49710420.232499.99110430.232500.01110460.242511.48910495.772518.001
#Mann= 3 , 0 , 0
9340.642   0.062       09340.642   0.062       010495.77   0.062       0
#XS Ineff= 2 , 0
       0                               0
Bank Sta=9340.642,10495.77
Exp/Cntr=0.3,0.1

Type RM Length L Ch R = 1 ,37818.07,937.842900,937.842900,937.842900
XS GIS Cut Line= 2
639436.977637828789654.828106347640781.422082275 789732.60588412
#Sta/Elev= 30
9170.2382654.9119238.3742624.8819278.4412609.7989298.4742608.1059348.5582591.285
9428.6922574.5469458.7422564.9319478.7752556.8319508.8262540.6349528.8592525.731
9538.8762524.8079548.8922520.5029568.9262506.2079588.9592497.6389598.9762496.646
 9649.062481.2989699.143 2471.14 9799.312442.8959829.3612439.8899909.4942438.643
 10149.92438.64310199.982441.91810230.032454.08610260.082470.09310300.152497.151
10320.182507.841 10390.32534.24310440.382560.82410490.462576.90610516.932576.285
#Mann= 3 , 0 , 0
9170.238    0.04       09170.238    0.04       010516.93    0.04       0
#XS Ineff= 2 , 0
       0                               0
Bank Sta=9170.238,10516.93
Exp/Cntr=0.3,0.1

Type RM Length L Ch R = 1 ,36880.22,444.554100,444.554100,444.554100
XS GIS Cut Line= 2
639442.533193381790604.828106335 640770.31097117790660.383661891
#Sta/Elev= 30
9277.221 2581.589289.6992587.7249299.7082586.5799369.7692556.6529449.8392527.387
9469.8562520.8499509.8912511.0799549.9262504.5549589.9612491.1199609.9792482.266
9619.9882472.9469640.0052459.2369670.0312448.744 9680.042443.4179700.0572439.675
9720.0752438.64310150.452438.69110180.482442.08110310.592531.663 10320.62538.126
10350.632552.573 10430.7 2578.1710490.752603.46610500.762605.55910520.772606.519
10560.812605.28110580.83 2612.7910590.842614.29510600.842612.40810606.162614.071
#Mann= 3 , 0 , 0
9277.221  0.0283       09277.221  0.0283       010606.16  0.0283       0
#XS Ineff= 2 , 0
       0                               0
Bank Sta=9277.221,10606.16
Exp/Cntr=0.3,0.1

Type RM Length L Ch R = 1 ,36435.67,806.053100,806.053100,806.053100
XS GIS Cut Line= 2
639098.088748931791027.050328565640781.422082276791110.383661911
#Sta/Elev= 30
8970.1432649.7068977.0622649.3368987.0752644.1679017.111 2623.659047.1482606.549
9137.2582562.2889167.2952556.7159207.3442536.8789237.3812525.321 9277.432518.017
9297.4542510.6269347.5152499.3969377.5522496.0039397.5772486.2599407.5892476.897
9427.6132464.8639467.6622447.3699487.6872445.7249517.7242438.64310308.692438.783
10378.782479.84410408.812491.26410428.842506.84310468.892532.34710508.942564.286
10528.962577.78210548.982593.64110569.012613.99810579.022616.87210655.542598.835
#Mann= 3 , 0 , 0
8970.143  0.0154       08970.143  0.0154       010655.54  0.0154       0
#XS Ineff= 2 , 0
       0                               0
Bank Sta=8970.143,10655.54
Exp/Cntr=0.3,0.1

Type RM Length L Ch R = 1 ,35629.62,849.399600,849.399600,849.399600
XS GIS Cut Line= 2
638992.533193412791838.161439687641336.977637857 791932.60588413
#Sta/Elev= 30
8933.8722684.5299006.3982648.2729126.4952607.3019166.527 2585.839186.5442566.644
9216.568 2565.979266.6082529.7049316.6492500.5569346.6732491.6019376.6982493.276
9396.7142488.7429486.7872452.0329496.7952450.1449526.8192457.041 9576.862445.048
9616.8922445.313  9626.92438.7789636.9092438.64310377.512438.64310587.682530.946
10757.822573.83810777.832569.01110847.892533.75410877.912524.85410947.972486.458
10967.992480.75410998.012481.249 11108.12506.89511178.162547.97811280.22 2632.16
#Mann= 3 , 0 , 0
8933.872  0.0206       08933.872  0.0206       011280.22  0.0206       0
#XS Ineff= 2 , 0
       0                               0
Bank Sta=8933.872,11280.22
Exp/Cntr=0.3,0.1

Type RM Length L Ch R = 1 ,34780.22,508.480600,508.480600,508.480600
XS GIS Cut Line= 4
 639264.75541562792749.272550825639992.533193411792754.828106348
640770.310971174792554.828106354641448.088748931792599.272550801
#Sta/Elev= 30
9082.0982533.7399242.3482498.6959272.3492479.041 9322.352477.6599382.352 2439.58
9392.3522438.64310359.692438.64310442.292485.57310483.592486.31310514.572501.606
10566.192495.07410586.842510.37410612.292518.73910687.832519.81710727.912525.467
10737.932524.282   107682507.44410808.092497.84710878.242497.49810918.322517.082
10938.362514.93110988.472528.78611018.542542.776 11048.62560.06311098.712600.527
11128.77 2616.5911148.822615.65911218.97 2597.2911259.052602.32511292.212614.091
#Mann= 3 , 0 , 0
9082.098  0.0153       09082.098  0.0153       011292.21  0.0153       0
#XS Ineff= 2 , 0
       0                               0
Bank Sta=9082.098,11292.21
Exp/Cntr=0.3,0.1

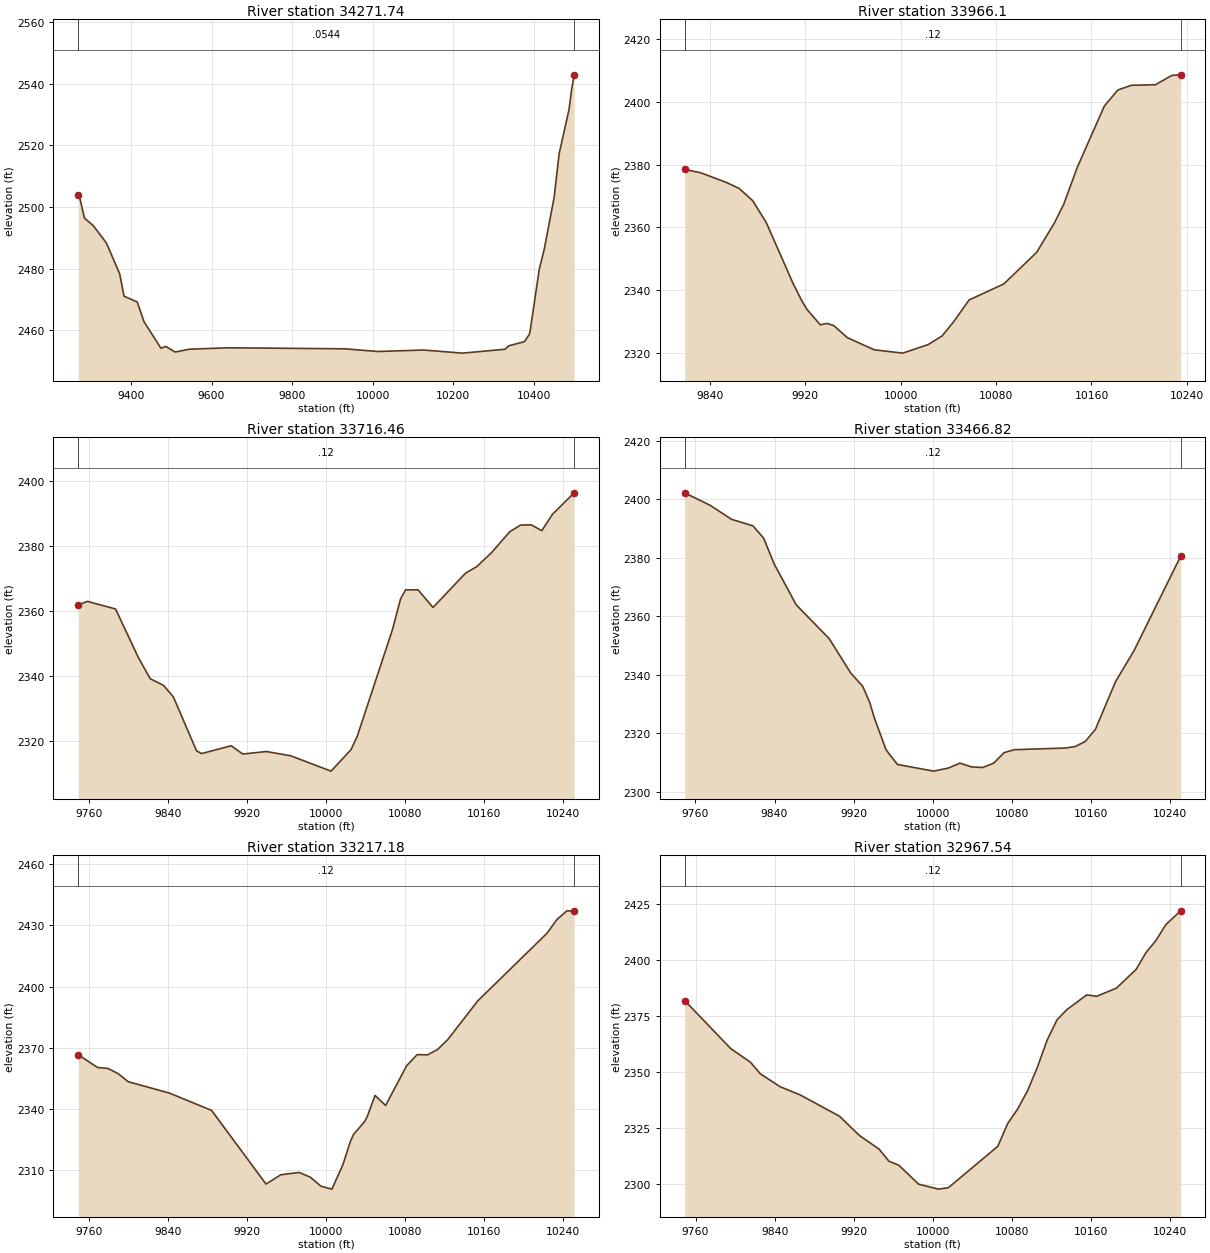
Type RM Length L Ch R = 1 ,34271.74,305.634000,305.634000,305.634000
XS GIS Cut Line= 6
639370.740447938792807.564165905639505.001366615792866.032630503
639778.178536952793034.321516171639979.657988876793155.209187329
640305.383102804793352.491150662640425.338309377793438.807033703
#Sta/Elev= 30
9269.0922503.7969273.7382502.5149284.6452496.3979306.4592493.953 9339.182488.289
9371.9022478.3569382.8092471.059 9415.532469.1829432.5422462.765 9474.372454.177
9486.1382454.7849509.6582452.9479544.8682453.8599642.1692454.3219930.9312453.985
10012.632453.11210125.722453.598 10222.92452.58810328.292453.84310337.772454.969
10376.332456.30410388.652458.652 10390.7 2459.7710413.29 2479.7410425.612486.238
10450.252503.07110462.572517.19910487.212531.63710493.432537.91610499.94 2542.87
#Mann= 3 , 0 , 0
9269.092  0.0544       09269.092  0.0544       010499.94  0.0544       0
#XS Ineff= 2 , 0
       0                               0
Bank Sta=9269.092,10499.94
Exp/Cntr=0.3,0.1

Type RM Length L Ch R = 1 , 33966.1,249.641300,249.641300,249.641300
XS GIS Cut Line= 2
 639674.70468337793338.688999011640041.434952623 793534.96717128
#Sta/Elev= 30
9818.8222378.4199832.1962377.3799853.3882374.3559864.5262372.3739875.8682368.467
 9887.21 2361.549909.8942341.9449916.964 2336.649921.237 2333.899932.5792328.896
9938.1562329.3569943.9212328.6499955.2632324.8099977.9482320.91910001.732319.877
10022.922322.57110034.662325.33910044.122329.71910057.342336.818 10086.52341.936
10114.052352.01110128.882361.36110136.74 2367.3310148.082379.07210170.76 2398.61
10182.112403.75910193.452405.24910213.652405.42810227.48 2408.4210234.772408.589
#Mann= 3 , 0 , 0
9818.822    0.12       09818.822    0.12       010234.77    0.12       0
#XS Ineff= 2 , 0
       0                               0
Bank Sta=9818.822,10234.77
Exp/Cntr=0.3,0.1

Type RM Length L Ch R = 1 ,33716.46,249.641200,249.641200,249.641200
XS GIS Cut Line= 6
639572.734771675793490.119443675639743.699664587 793595.64662568
639814.768611843793670.787645097639859.927485159793706.979785977
639918.509763471  793740.1583997639985.355549392793767.099120489
#Sta/Elev= 30
9749.0542361.8689758.4412362.9129786.8252360.5839810.2382345.4719821.9442339.141
 9835.382337.1019845.3572333.553 9868.772316.9969873.8492316.131 9903.892318.537
9915.5962315.9899939.4392316.7669963.9222315.46910004.912310.73810025.172317.357
10031.522321.52810067.09 2354.2710075.27  2363.710080.322366.47210092.972366.465
10108.132361.051 10140.92371.56210152.442373.62710167.55 2377.9810185.852384.355
10196.63 2386.3810207.422386.459 10218.22384.66710228.982389.70110250.932396.294
#Mann= 3 , 0 , 0
9749.054    0.12       09749.054    0.12       010250.93    0.12       0
#XS Ineff= 2 , 0
       0                               0
Bank Sta=9749.054,10250.93
Exp/Cntr=0.3,0.1

Type RM Length L Ch R = 1 ,33466.82,249.641300,249.641300,249.641300
XS GIS Cut Line= 6
639351.065458628793656.928815447639502.723821859793723.854471425
639589.852033087 793784.99886896639623.508391472793803.659891437
639658.097982473793814.257744639639809.609320739793844.174915806
#Sta/Elev= 30
9749.0752402.229 9774.922397.9499796.515 2393.169818.1112390.9539828.9092386.748
9839.7822377.8129861.9722363.9029895.2572352.3829917.1292340.5979929.2832336.025
9936.3982330.4629940.9822325.2479952.6812314.4869955.6672313.065 9964.382309.334
   100012307.04810015.822308.09910027.67 2309.78 10039.12308.50610050.542308.282
10061.83 2309.7910072.282313.37210082.742314.38310134.062314.94910144.252315.454
10154.442317.20610164.642321.31210185.022337.64510203.52  2348.110250.88 2380.52
#Mann= 3 , 0 , 0
9749.075    0.12       09749.075    0.12       010250.88    0.12       0
#XS Ineff= 2 , 0
       0                               0
Bank Sta=9749.075,10250.88
Exp/Cntr=0.3,0.1

Type RM Length L Ch R = 1 ,33217.18,249.641200,249.641200,249.641200
XS GIS Cut Line= 6
639435.845549654794063.117449737639554.824836257794029.174898028
639707.587529595 793957.93561761639759.168516215793938.881372007
639831.719111196793926.515194157639912.375445376793926.819407816
#Sta/Elev= 30
9749.0572366.5749768.7612360.3099779.0482359.8679789.335 2357.369799.6222353.369
9841.3812347.7729883.9862339.3069939.0962303.1859954.098 2307.759972.6272308.874
9983.8042306.5899994.8082302.11910005.772300.70410016.742312.47910024.352323.906
10027.722327.54510038.692333.70310041.53 2336.2310049.432346.63610060.092341.701
10081.412361.19210092.072366.637 10102.52366.50510112.77 2369.1610123.042374.021
10153.372392.96810223.522426.16110233.53 2432.8610243.532437.11110250.912436.929
#Mann= 3 , 0 , 0
9749.057    0.12       09749.057    0.12       010250.91    0.12       0
#XS Ineff= 2 , 0
       0                               0
Bank Sta=9749.057,10250.91
Exp/Cntr=0.3,0.1

Type RM Length L Ch R = 1 ,32967.54,249.641300,249.641300,249.641300
XS GIS Cut Line= 6
639448.491616983794225.084888127639627.704724095794214.986509841
639668.293583313794215.216264112639727.745623521794218.759041371
639771.090163831794219.552306416 639949.96687477794214.172448479
#Sta/Elev= 30
9749.0242381.9579795.6062360.4729815.6372354.3379825.6532349.1729845.6852343.389
9865.7172339.784 9905.782330.1969925.8122321.6169945.8162315.4849955.8172310.063
9965.8172308.2899985.8422299.81510005.892297.59910015.912298.23310065.942316.746
10075.942326.90510085.952333.36910095.952341.50410105.962352.05110115.962364.321
10125.962373.37110135.972377.92710155.982384.47510165.98 2383.8510185.992387.482
   102062395.90910216.012403.45910226.012408.79210236.012415.89810250.992422.079
#Mann= 3 , 0 , 0
9749.024    0.12       09749.024    0.12       010250.99    0.12       0
#XS Ineff= 2 , 0
       0                               0
Bank Sta=9749.024,10250.99
Exp/Cntr=0.3,0.1