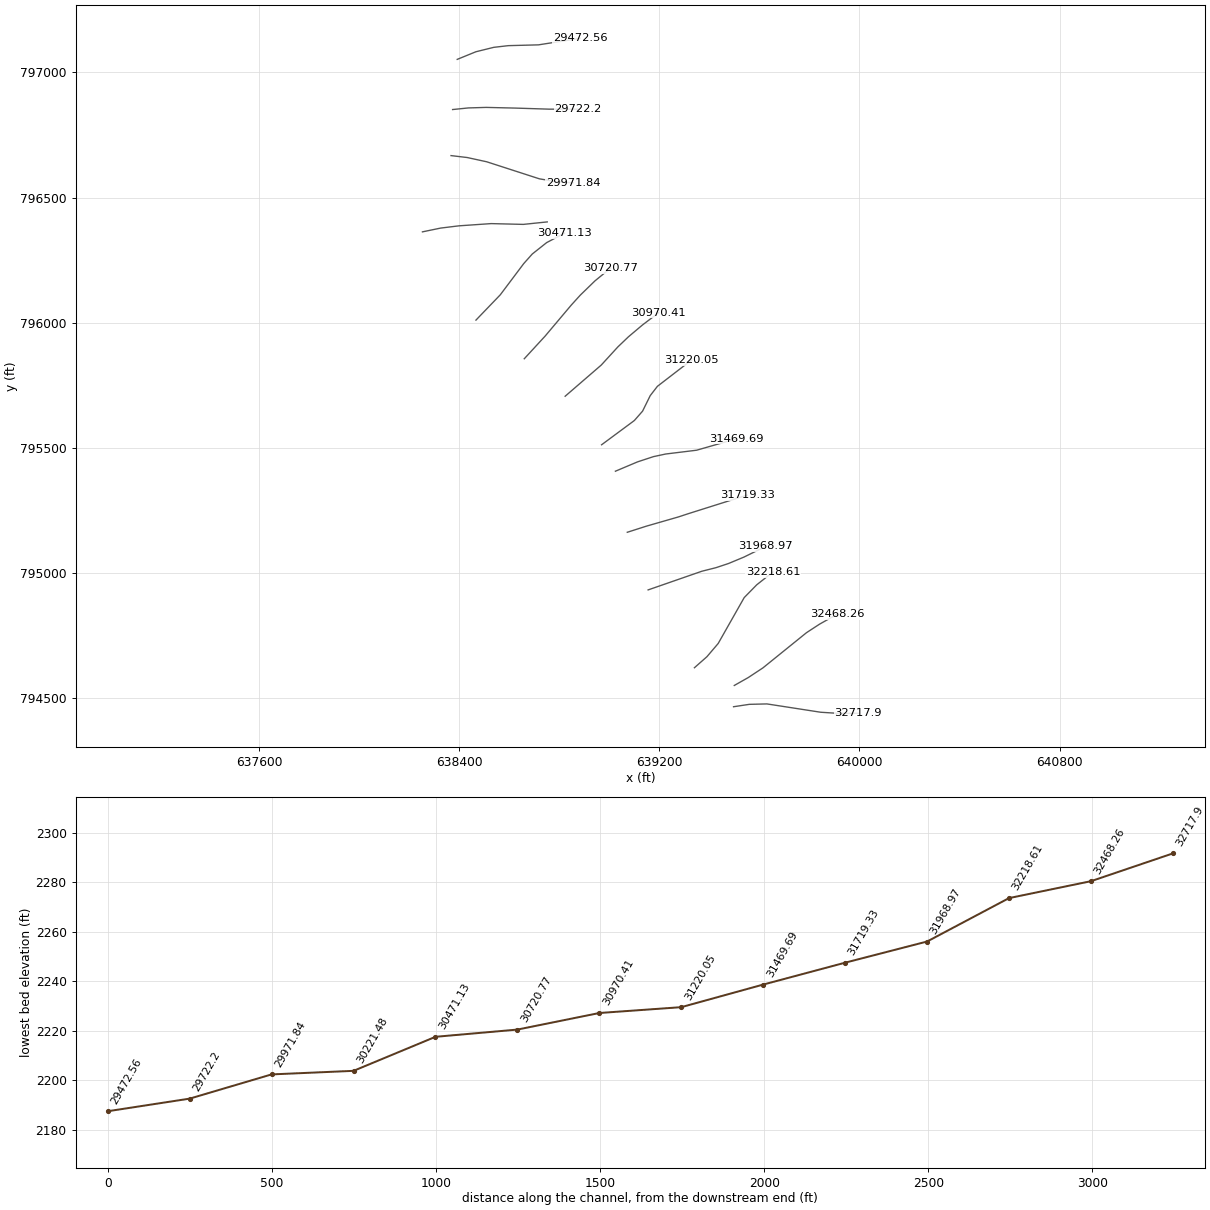
HEC-RAS study 12582_ras.prj: 12582

--- 12582_ras.g01 (geometry) --- (continued)

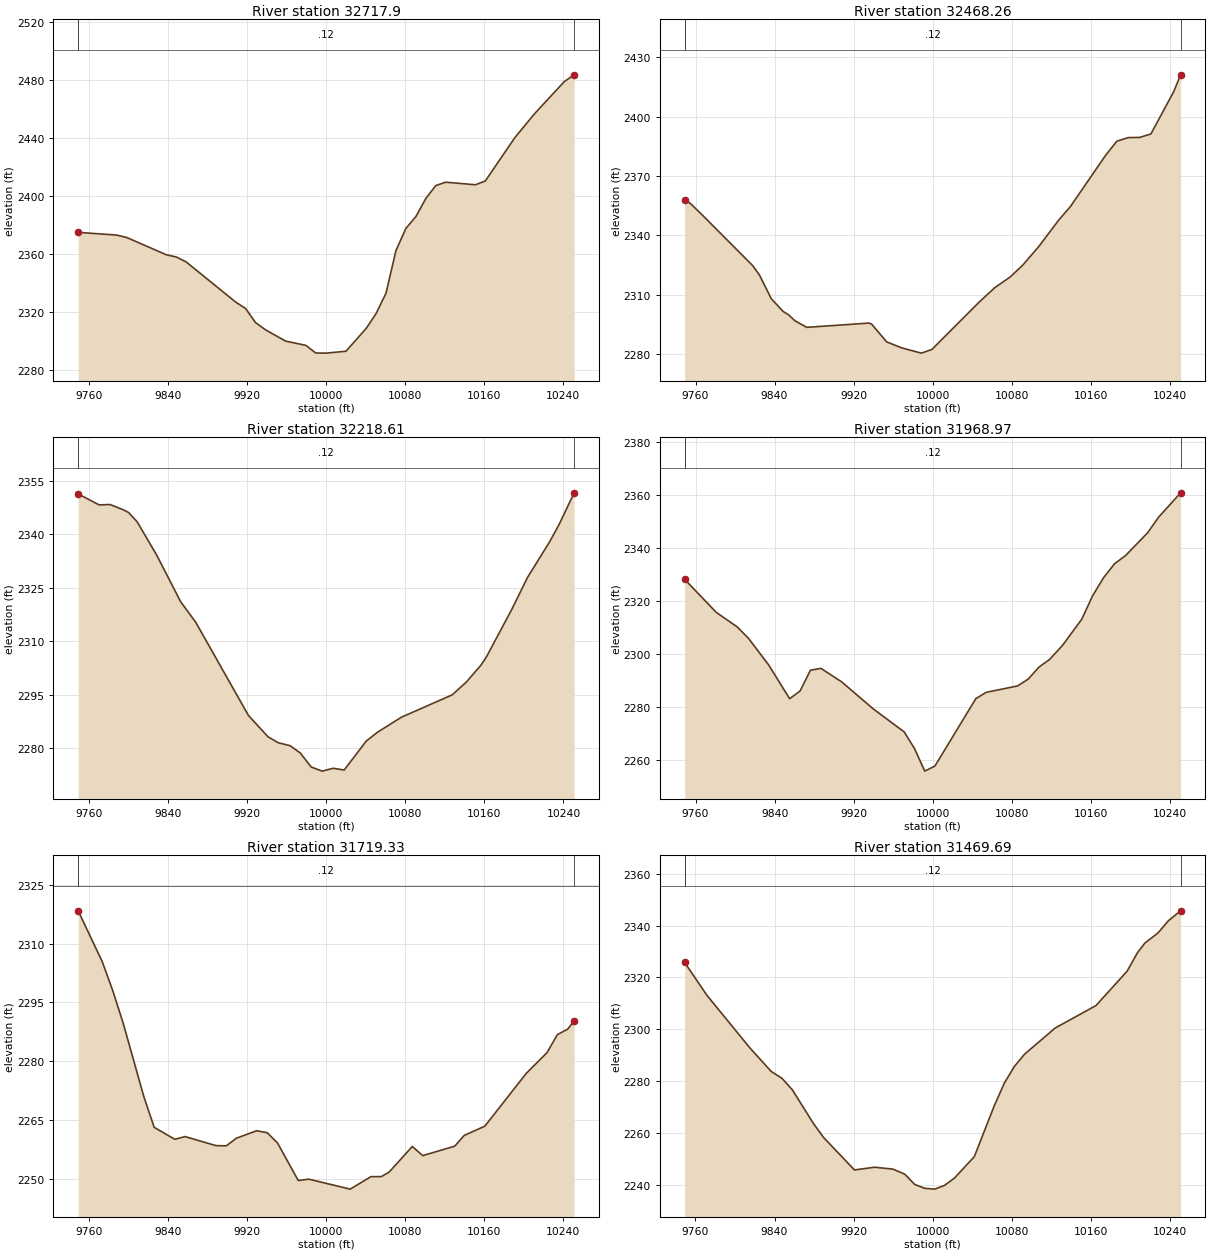
Type RM Length L Ch R = 1 , 32717.9,249.641200,249.641200,249.641200
XS GIS Cut Line= 6
639496.602563897794465.840867603639559.641404369794475.386254433
639630.147513734794477.067984407639845.107134791794443.815407728
 639916.30801545794439.304671425639994.899833244794439.618981446
#Sta/Elev= 30
9749.0652374.758  9787.92372.9059798.0142371.2639838.2352359.324 9848.252357.825
 9858.252354.4359908.3992326.7479918.4582322.3279928.5172312.6219938.633 2307.64
9958.9882299.8459979.342 2296.959989.5192291.6589999.6972291.57810020.022292.874
10040.342308.45210050.462318.73210060.552332.84410070.642362.25610080.732377.523
10090.832385.67210100.922398.18110110.94    240710120.962409.32610151.022407.547
10161.042410.14410191.06 2440.1310211.062456.59710241.062478.66410250.962483.274
#Mann= 3 , 0 , 0
9749.065    0.12       09749.065    0.12       010250.96    0.12       0
#XS Ineff= 2 , 0
       0                               0
Bank Sta=9749.065,10250.96
Exp/Cntr=0.3,0.1

Type RM Length L Ch R = 1 ,32468.26,249.641300,249.641300,249.641300
XS GIS Cut Line= 6
 639499.52495825 794550.81124962639555.048684979794582.183712686
639613.982890771794621.006576892639788.227613672794761.683932126
639839.821644533794795.361459277639911.188736458794835.572465742
#Sta/Elev= 30
9749.0452358.0669755.3342355.848 9766.822350.2759817.9392324.6099824.7362319.867
 9836.712307.8689848.6852301.4239854.2952299.719 9860.66  2296.79872.6352293.402
 9935.57 2295.559938.2552295.0169953.5052286.0289968.7562282.997 9988.552280.349
9999.2712282.22110046.452305.874   100632313.52510078.382318.84810090.892324.732
10107.432334.29810127.462347.612 10139.4  2354.510174.992380.41510186.472387.623
10197.952389.43210209.422389.506 10220.92391.27310243.862412.55610250.96 2421.19
#Mann= 3 , 0 , 0
9749.045    0.12       09749.045    0.12       010250.96    0.12       0
#XS Ineff= 2 , 0
       0                               0
Bank Sta=9749.045,10250.96
Exp/Cntr=0.3,0.1

Type RM Length L Ch R = 1 ,32218.61,249.641200,249.641200,249.641200
XS GIS Cut Line= 6
639340.156316886 794621.63702595639390.177468866794665.707118478
639435.198387665794718.541559452639539.210244286794901.877226529
639589.283560371 794952.91784143639654.236928859795004.311479652
#Sta/Elev= 30
9749.0562351.3779770.2052348.2879781.337 2348.399795.0082346.8779800.0552346.135
9808.6792343.5489828.4292334.2069852.7142321.0939867.9412315.3419921.3182289.143
9941.1522283.1489951.5292281.4879963.3852280.6659973.7392278.6259984.8442274.667
9995.9492273.51610006.992274.31810018.162273.825 10040.52281.957 10051.82284.422
10076.042288.65310127.472294.93510141.972298.58810156.532303.26810162.152305.611
10188.092319.12410203.642327.89210226.342338.05510235.872342.91510250.872351.678
#Mann= 3 , 0 , 0
9749.056    0.12       09749.056    0.12       010250.87    0.12       0
#XS Ineff= 2 , 0
       0                               0
Bank Sta=9749.056,10250.87
Exp/Cntr=0.3,0.1

Type RM Length L Ch R = 1 ,31968.97,249.641300,249.641300,249.641300
XS GIS Cut Line= 6
639155.104303147794932.579518977639369.630453431795007.043957681
639426.171324075795021.320058846639476.747491604795038.133531794
639538.537680024795063.870750045639624.983365619795106.236102664
#Sta/Elev= 30
9749.0292328.297 9780.912315.8769802.2382310.3499813.5742306.0819834.1492295.961
9855.2422283.2859865.7882286.1699876.3352294.0179886.8812294.7379907.9742289.622
9939.6142279.5269971.2532270.7399981.6872264.4539992.022 2255.9710002.33 2257.91
10043.762283.339 10054.32285.69810085.912288.09610096.692290.66410107.522295.177
10118.362298.10310131.622303.47910150.862313.24310161.882322.09210173.022328.954
10184.162334.19510195.292337.28910217.57 2345.86 10228.72351.75910250.962360.932
#Mann= 3 , 0 , 0
9749.029    0.12       09749.029    0.12       010250.96    0.12       0
#XS Ineff= 2 , 0
       0                               0
Bank Sta=9749.029,10250.96
Exp/Cntr=0.3,0.1

Type RM Length L Ch R = 1 ,31719.33,249.641200,249.641200,249.641200
XS GIS Cut Line= 6
639071.755752665795162.786395152639148.626105706795187.370200665
639275.903501466795224.002107896639310.899954635795235.511664047
639312.791029806795236.162689928639551.192294611795311.352222901
#Sta/Elev= 30
 9749.012318.3319773.4142305.3299783.9132298.0529794.4122289.7959815.4092271.016
9825.9082263.1749846.7542260.118 9857.162260.8099888.3782258.5119898.7842258.447
 9909.192260.4019929.6122262.2979940.4072261.7979950.8132259.1479971.7352249.614
9982.2622249.97110024.292247.42410045.26  2250.610055.742250.60710063.632251.746
 10087.22258.29610097.692255.95510130.122258.37610139.632261.091 10160.62263.472
10202.542276.92710223.512282.199   102342286.78210244.482288.19710250.982290.322
#Mann= 3 , 0 , 0
 9749.01    0.12       0 9749.01    0.12       010250.98    0.12       0
#XS Ineff= 2 , 0
       09932.547                       0
Bank Sta=9749.01,10250.98
Exp/Cntr=0.3,0.1

Type RM Length L Ch R = 1 ,31469.69,249.641300,249.641300,249.641300
XS GIS Cut Line= 6
 639024.29736318795406.753195516639112.832020091795444.082675342
639176.482841339795465.009958222639225.379938655 795475.45882718
639348.732453338795490.600874451639506.716471966795535.840422904
#Sta/Elev= 30
9749.0862325.7829771.5542313.1679814.9642292.9659836.6692283.8499847.451 2281.24
9857.9782276.8339879.0312264.0279889.5582258.4849920.881 2245.969941.3332247.006
9959.977 2246.269971.8352244.3229981.8792240.3739991.9232238.90110001.962238.573
10011.992239.99410022.032242.80210042.182251.06410062.48 2270.7410072.622279.413
10082.772285.79310093.032290.49710123.992300.55410165.292309.19710196.74 2322.39
10207.222329.49810214.812333.24710228.192337.18310238.672341.87410250.952345.653
#Mann= 3 , 0 , 0
9749.086    0.12       09749.086    0.12       010250.95    0.12       0
#XS Ineff= 2 , 0
       0                               0
Bank Sta=9749.086,10250.95
Exp/Cntr=0.3,0.1

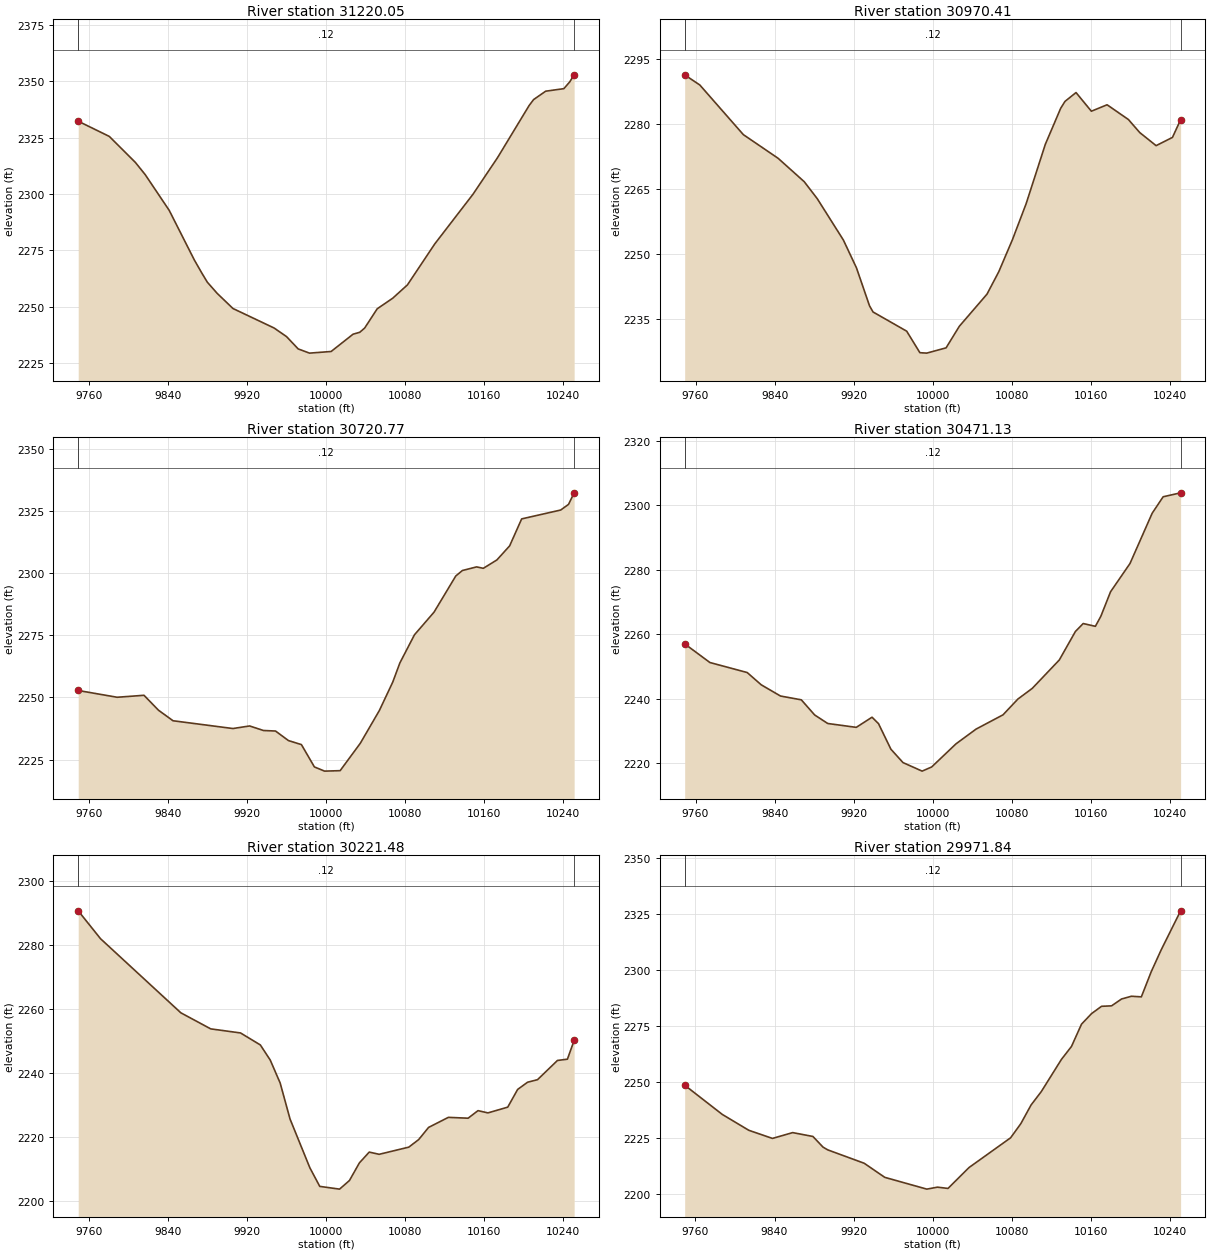
Type RM Length L Ch R = 1 ,31220.05,249.641200,249.641200,249.641200
XS GIS Cut Line= 6
638969.060624429795512.350581073639100.033541011795609.246060949
639132.959310976795646.780610932639163.550221827795708.818993061
639192.263856266795745.912859281639328.707101228795850.941698109
#Sta/Elev= 30
9749.0962332.3239780.5342325.5859806.8832314.0759816.8932308.6189841.1332292.801
9866.7712270.618 9874.052265.059 9879.732260.9189889.7732255.9229905.6482249.247
9947.2762240.5949959.9252236.7599971.6682231.312 9983.142229.44410005.012230.173
10027.182237.83610033.97 2238.6910038.922240.55810051.632249.10710067.312253.804
10082.182259.69710109.842277.87610148.582299.94510173.372316.14510205.382339.303
10209.882341.91910222.052345.63110240.472346.76310246.392349.745 10250.92352.897
#Mann= 3 , 0 , 0
9749.096    0.12       09749.096    0.12       0 10250.9    0.12       0
#XS Ineff= 2 , 0
       0                               0
Bank Sta=9749.096,10250.9
Exp/Cntr=0.3,0.1

Type RM Length L Ch R = 1 ,30970.41,249.641300,249.641300,249.641300
XS GIS Cut Line= 6
 638823.37623195795706.228395682638967.705138473795830.794544154
639033.972525001795903.139187489639076.327355384795943.664728682
639132.638328757795991.071442737 639197.07002446796039.989862691
#Sta/Elev= 30
9749.0272291.2619764.381 2288.919808.3672277.4789843.6372272.0079870.0562266.609
9883.2662262.6839909.6852253.1529922.8942246.7469936.1042237.9979939.6772236.572
9973.7382232.1439987.0812227.1859993.9852227.08510013.592228.30210026.952233.259
10054.992240.68510066.932245.85910080.77 2253.2610094.612261.54210114.052275.247
10129.582283.54310133.932285.13410145.11 2287.1710160.632282.86810176.562284.354
10198.14 2280.9510209.63 2277.9410226.172274.93110242.712276.83210250.962280.909
#Mann= 3 , 0 , 0
9749.027    0.12       09749.027    0.12       010250.96    0.12       0
#XS Ineff= 2 , 0
       0                               0
Bank Sta=9749.027,10250.96
Exp/Cntr=0.3,0.1

Type RM Length L Ch R = 1 ,30720.77,249.641200,249.641200,249.641200
XS GIS Cut Line= 6
638659.970044036795856.024101631638743.308738913795946.476511705
638848.070899861796070.667712972638883.941688242796110.190097348
638943.073050675796167.570804463639005.569467321796218.601682323
#Sta/Elev= 30
9749.0222252.8139788.4222250.0899815.6162250.8799830.236 2244.899844.9942240.639
9905.5682237.5149922.506 2238.559936.507 2236.72 9948.722236.5089961.8262232.665
9974.9332231.051 9988.042222.0859998.3842220.38510014.11 2220.5710034.492231.566
10053.852244.78810067.352256.17810074.562263.88510089.342275.20510109.132284.301
10131.142298.85110137.852301.05410152.212302.50910159.012301.94110172.752305.305
10185.662310.96510197.822321.808 10237.32325.37710245.252327.64410250.952332.295
#Mann= 3 , 0 , 0
9749.022    0.12       09749.022    0.12       010250.95    0.12       0
#XS Ineff= 2 , 0
       0                               0
Bank Sta=9749.022,10250.95
Exp/Cntr=0.3,0.1

Type RM Length L Ch R = 1 ,30471.13,249.641300,249.641300,249.641300
XS GIS Cut Line= 6
638466.852514838796010.420862381638564.172067274796111.608557421
638657.952000531796236.325258914638691.844184561796274.363478171
638749.516516304796320.084327079638820.913026112796357.565511772
#Sta/Elev= 30
9749.0312257.0049774.6022251.1989812.3082248.0929826.5022244.2779846.0052240.793
9867.0692239.6139880.5582234.9129893.8262232.2599922.6842231.061 9938.632234.213
 9945.182232.2159957.6932224.2879969.9772220.1129989.3372217.462    99992218.755
10023.542225.92210043.932230.519 10071.22234.95510086.232239.85210100.762243.165
10128.142251.99110144.432260.83610152.322263.31610164.652262.44610170.222265.591
   101802273.17510199.692281.96910222.142297.58410233.242302.69310250.91 2303.92
#Mann= 3 , 0 , 0
9749.031    0.12       09749.031    0.12       010250.91    0.12       0
#XS Ineff= 2 , 0
       0                               0
Bank Sta=9749.031,10250.91
Exp/Cntr=0.3,0.1

Type RM Length L Ch R = 1 ,30221.48,249.641200,249.641200,249.641200
XS GIS Cut Line= 6
638252.873660731796362.952310529638325.647782035796378.042237483
 638399.07562565796387.044639597638527.576388925    796395.92607
638656.215152914796392.791684794638751.750392309796402.720848154
#Sta/Elev= 30
9749.0492290.7059771.6462281.9849852.9432258.8239883.1682253.8029913.3122252.532
 9933.362248.7859943.3842244.0619953.4082236.9069963.4322225.622 9983.48 2210.39
9993.5042204.56610013.55 2203.7110023.582206.40910033.592211.89910043.592215.291
 10053.62214.59110083.632216.83710093.632219.20110103.642222.99810123.652226.145
10143.652225.87910153.652228.24610163.68 2227.5410183.742229.33210193.772234.868
 10203.82237.12310213.882237.92210234.062243.92710244.152244.33610250.962250.192
#Mann= 3 , 0 , 0
9749.049    0.12       09749.049    0.12       010250.96    0.12       0
#XS Ineff= 2 , 0
       0                               0
Bank Sta=9749.049,10250.96
Exp/Cntr=0.3,0.1

Type RM Length L Ch R = 1 ,29971.84,249.641300,249.641300,249.641300
XS GIS Cut Line= 6
638367.179283654 796667.60704505638431.627620345796659.942787857
638509.725348938796642.930825173638720.479919645796574.813723216
638789.463683765796563.129897041638854.650350777796558.985937187
#Sta/Elev= 30
9749.0772248.6049787.1642235.563 9813.982228.496  9837.92224.8789858.3692227.465
9878.8382225.7469889.0722220.9959893.9092219.7599930.6952213.8129951.5522207.528
9994.0972202.27510004.842203.15310015.522202.58610036.872211.92310078.852225.143
10089.212231.44610099.572239.76910109.942245.75810130.342260.12210140.482265.876
10150.632275.80610160.772280.50610170.912283.76510181.05 2283.9710191.132287.018
10201.152288.24910211.172287.97310221.192299.20610231.212308.892 10250.92326.319
#Mann= 3 , 0 , 0
9749.077    0.12       09749.077    0.12       0 10250.9    0.12       0
#XS Ineff= 2 , 0
       0                               0
Bank Sta=9749.077,10250.9
Exp/Cntr=0.3,0.1

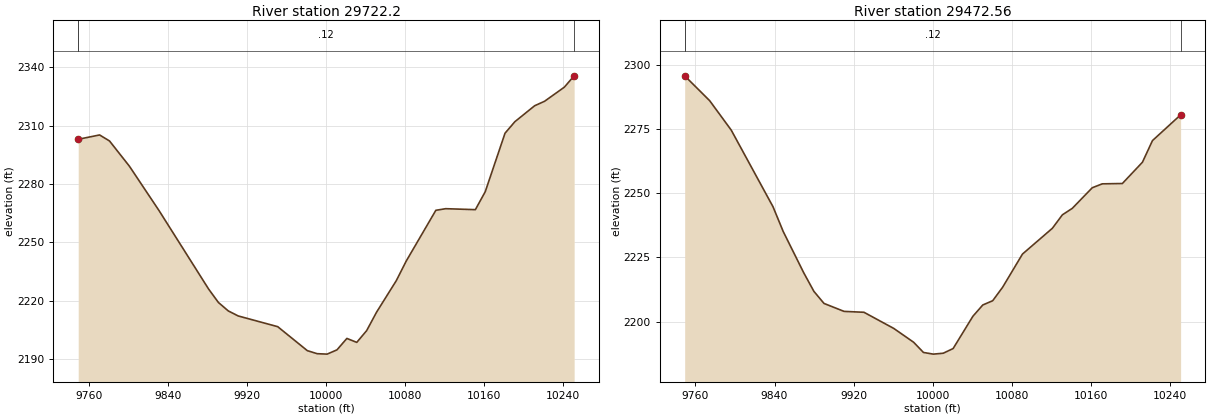
Type RM Length L Ch R = 1 , 29722.2,249.641300,249.641300,249.641300
XS GIS Cut Line= 6
638373.476009165796851.594545316638436.911981324796858.063153381
638507.461627747796860.162333625638623.049150239796857.461596517
638759.950401283796853.129787829638874.970138928796853.169537248
#Sta/Elev= 30
9749.0352303.0249770.6712305.2589780.7232302.1689800.8262289.1959830.8962266.299
9880.9182226.0489890.921 2219.079900.9242214.7179910.9272212.1319950.9382206.612
9980.9462194.2659990.9492192.70710000.952192.48210010.962194.68910020.962200.557
10030.972198.52810040.972204.57110050.98 2214.0410070.992230.29610080.992240.339
10111.012266.48910121.012267.31610151.022266.81910161.022276.07510181.02 2306.15
10191.022312.09210211.022320.28910221.022322.58110241.02 2329.8310250.992335.682
#Mann= 3 , 0 , 0
9749.035    0.12       09749.035    0.12       010250.99    0.12       0
#XS Ineff= 2 , 0
       0                               0
Bank Sta=9749.035,10250.99
Exp/Cntr=0.3,0.1

Type RM Length L Ch R = 1 ,29472.56,249.641200,249.641200,249.641200
XS GIS Cut Line= 6
638391.944915364797052.022720242638466.618208616797082.470816364
638538.140884017797100.126922648638596.437332443797106.873384428
638716.581419255797109.996130766638883.025123052797136.075872964
#Sta/Elev= 30
9749.0812295.6359774.3232285.9919796.1622274.5449838.4792244.7099848.8622235.031
9869.6282218.9849879.873 2211.799890.0792207.1039910.3962204.012 9930.532203.665
 9960.732197.374 9980.742192.018 9990.742188.03610000.742187.38810010.742187.739
10020.742189.55410040.772202.11710050.792206.50710060.812208.16510070.842213.407
10090.94 2226.3110121.212236.34510131.292241.56210141.382244.10310161.562252.107
10171.692253.61910192.01 2253.7510212.332262.02210222.492270.44410250.972280.443
#Mann= 3 , 0 , 0
9749.081    0.12       09749.081    0.12       010250.97    0.12       0
#XS Ineff= 2 , 0
       0                               0
Bank Sta=9749.081,10250.97
Exp/Cntr=0.3,0.1