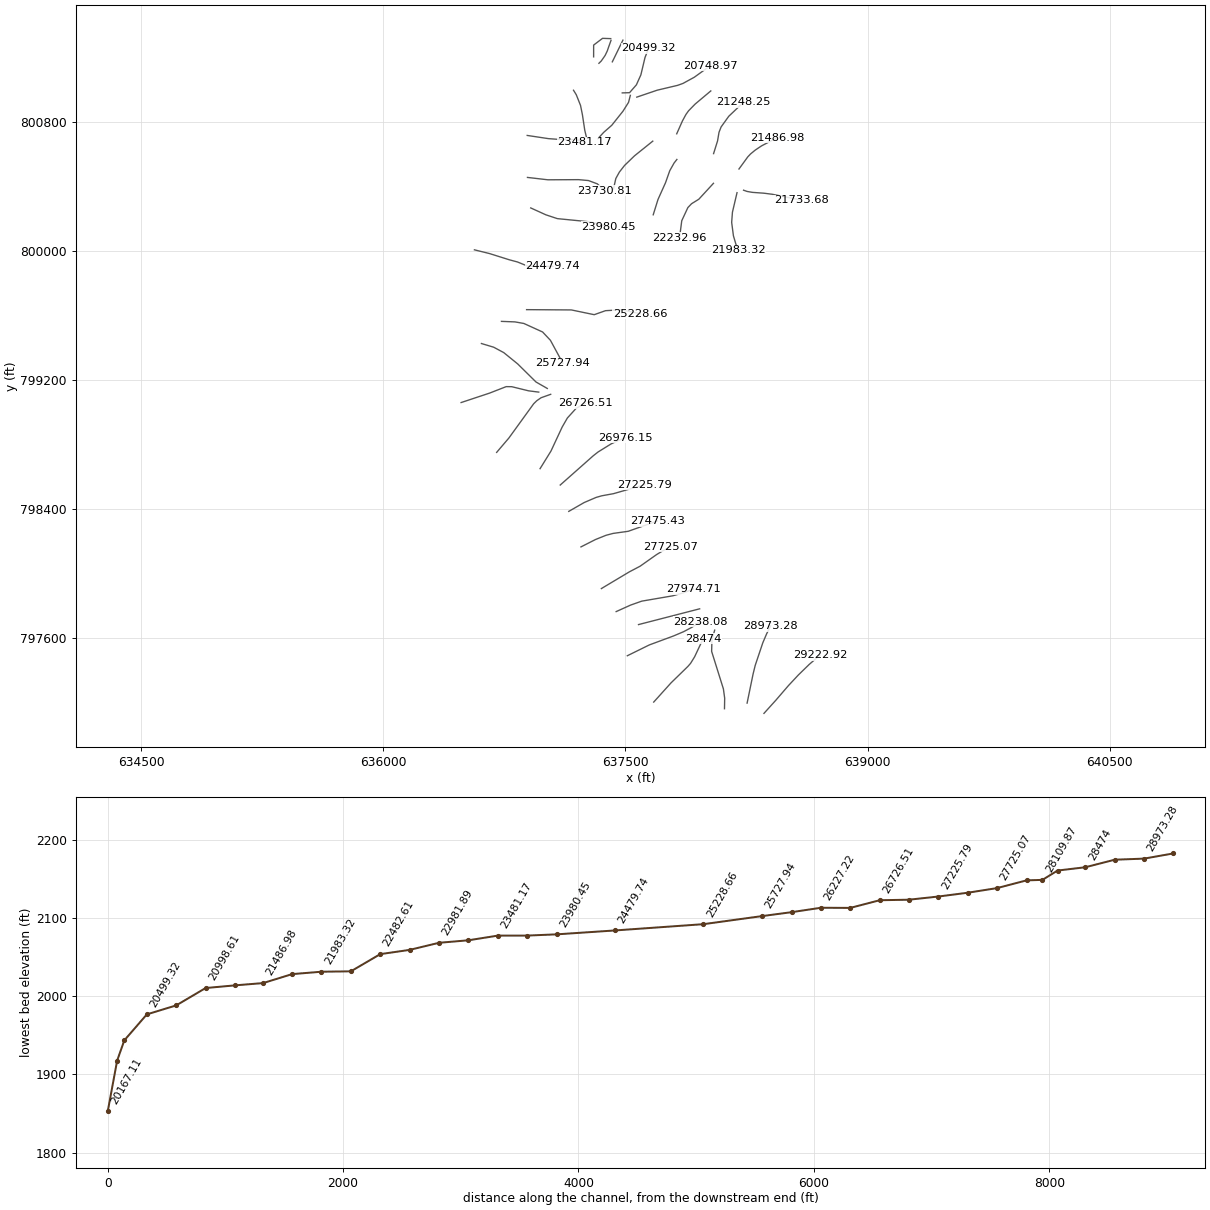
HEC-RAS study 12582_ras.prj: 12582

--- 12582_ras.g01 (geometry) --- (continued)

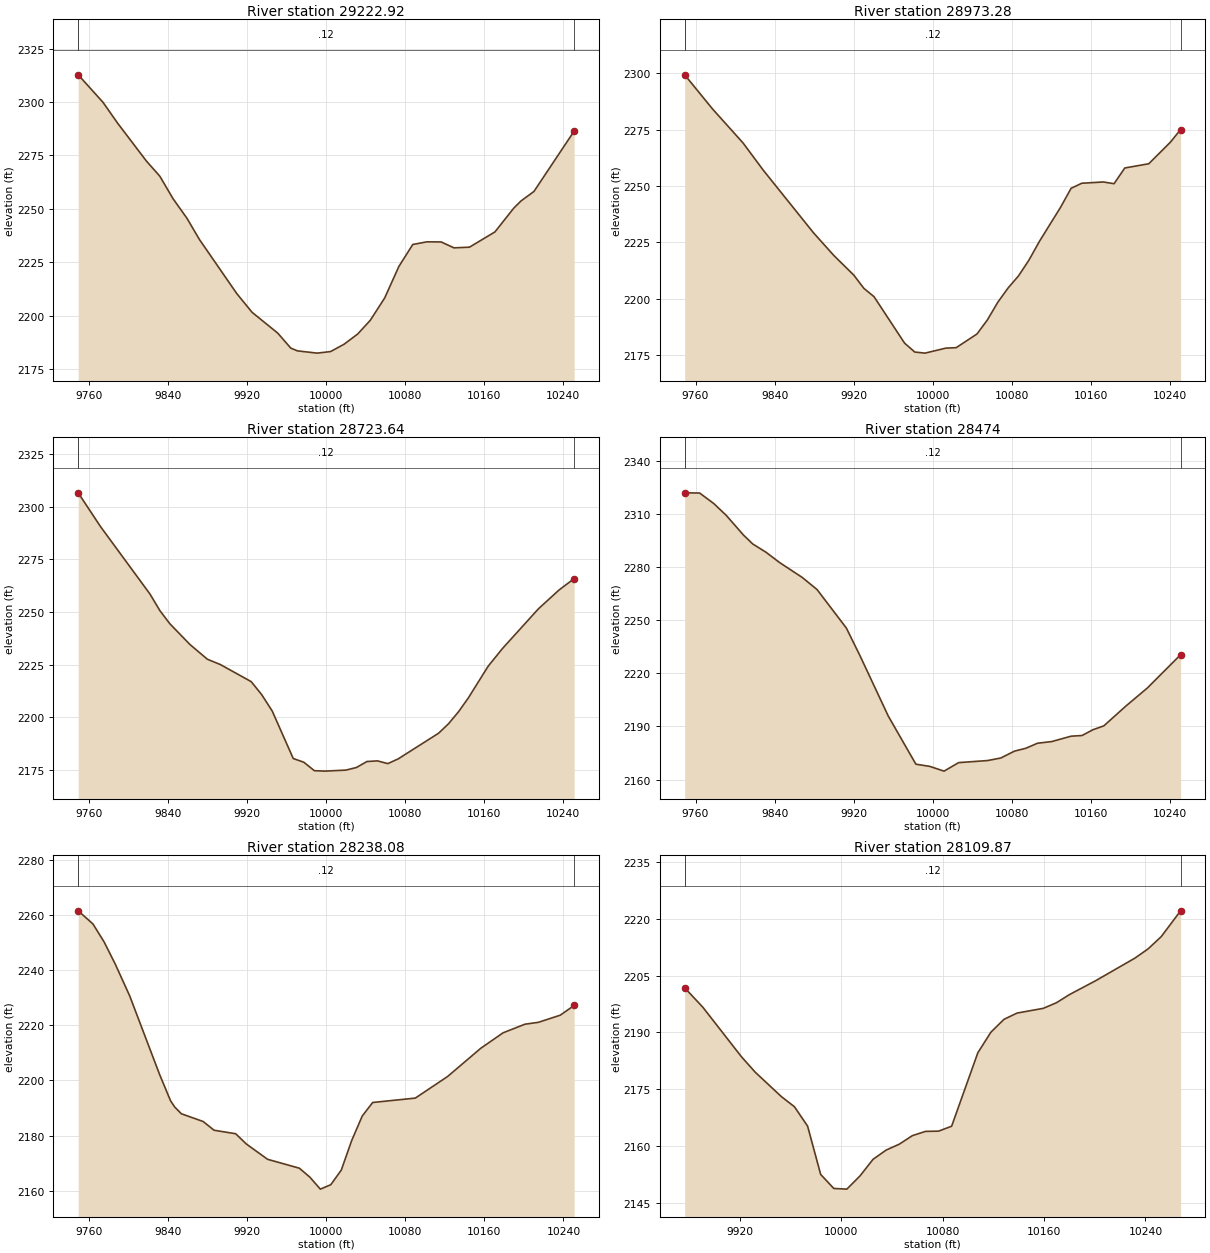
Type RM Length L Ch R = 1 ,29222.92,249.641300,249.641300,249.641300
XS GIS Cut Line= 6
638358.171221072797133.740812292638432.009671771797215.395366668
638509.728707926797305.654734914638571.348481585797371.624874137
 638638.63648636797437.113137409638705.873826772797494.805950031
#Sta/Elev= 30
9749.0062312.7319774.0962299.8639789.0062290.0329818.1152272.3219831.5972265.279
9845.0792254.6749859.0952245.5679871.7692235.5869909.6542210.225 9924.982201.549
9950.9472191.8199964.1432184.7999970.957 2183.499990.8432182.44110004.442183.173
10018.172186.62310031.912191.40710044.63 2197.8110059.222208.28610073.572223.024
10087.662233.30510101.992234.54710116.332234.49310129.392231.72510145.012232.045
10170.762239.17110189.842250.30810197.112253.65410210.292258.13310250.972286.381
#Mann= 3 , 0 , 0
9749.006    0.12       09749.006    0.12       010250.97    0.12       0
#XS Ineff= 2 , 0
       0                               0
Bank Sta=9749.006,10250.97
Exp/Cntr=0.3,0.1

Type RM Length L Ch R = 1 ,28973.28,249.641200,249.641200,249.641200
XS GIS Cut Line= 6
638253.738774365797197.393297058638290.977820059797378.283920349
638304.096868868797431.268192259638350.875913254797570.568650947
638375.264401914797627.808817751638399.766648001797675.311605117
#Sta/Elev= 30
9749.0312299.2779777.3722284.0569808.1692269.0149828.5732256.9579879.4872229.141
9899.8532219.1789920.2192210.3859930.4012204.5279940.6642200.838 9971.572180.233
9981.8722176.2759992.2722175.78310013.352178.00410023.852178.20810044.852184.274
10055.352190.47710065.862198.30310076.362204.69510086.882210.04810097.512217.097
10108.132225.42710129.382240.43610140.11 2248.9210150.982251.17110172.722251.729
10183.592250.96310194.462257.93710218.752259.81510240.572269.37210250.962274.996
#Mann= 3 , 0 , 0
9749.031    0.12       09749.031    0.12       010250.96    0.12       0
#XS Ineff= 2 , 0
       0                               0
Bank Sta=9749.031,10250.96
Exp/Cntr=0.3,0.1

Type RM Length L Ch R = 1 ,28723.64,249.641300,249.641300,249.641300
XS GIS Cut Line= 6
638113.639679308 797162.51205437638114.850161312797227.892521964
638106.900846782797285.424963564638034.014053505 797517.79916821
638035.911162829797588.131440278638052.927589265797649.500790251
#Sta/Elev= 30
9749.0632306.5349771.6052290.5129821.659 2258.499831.7152250.596 9841.772244.378
9862.0392234.5549879.7572227.5119892.9392224.9799924.0672216.8889934.6492210.752
9945.3222202.9729966.668 2180.379977.3412178.6049988.014 2174.599998.6872174.378
10019.952174.86710030.582176.09610041.212178.93510051.842179.24610062.422177.951
 10072.82180.17910113.762192.38910123.812196.88910133.822202.51610143.822209.127
10163.88 2224.1910178.442232.63510214.752251.45410235.572260.373 10250.92265.801
#Mann= 3 , 0 , 0
9749.063    0.12       09749.063    0.12       0 10250.9    0.12       0
#XS Ineff= 2 , 0
       0                               0
Bank Sta=9749.063,10250.9
Exp/Cntr=0.3,0.1

Type RM Length L Ch R = 1 ,   28474,235.916400,235.916400,235.916400
XS GIS Cut Line= 6
637675.293618826 797203.74785015637782.162313115797322.328908041
 637886.83931165797424.449139698637903.305226631797443.285980491
637928.678618934797484.211164624637980.982161251797595.316029138
#Sta/Elev= 30
9749.0282322.1899764.1762322.0769778.4642316.141  9791.12309.4379808.3392298.419
9818.023 2293.219831.4852288.5259844.9472282.8119868.0882274.2899883.0252267.466
9912.6552245.7029926.6662229.8099955.0862195.9039983.0312168.6799997.1062167.431
10011.562164.75310026.292169.56110055.662170.73810068.94 2172.1810082.972176.098
 10094.12177.63910106.172180.53610120.582181.48510140.072184.51510151.13 2184.89
10162.182188.16110173.23 2190.3610195.342201.45210217.442211.85910250.952230.627
#Mann= 3 , 0 , 0
9749.028    0.12       09749.028    0.12       010250.95    0.12       0
#XS Ineff= 2 , 0
       0                               0
Bank Sta=9749.028,10250.95
Exp/Cntr=0.3,0.1

Type RM Length L Ch R = 1 ,28238.08,128.213100,128.213100,128.213100
XS GIS Cut Line= 6
 637511.79951514797490.787708393637648.034584685797557.766736969
637797.525604469797613.125730373637859.982093864797639.611444912
637912.154947062797667.175902924637964.969290079797702.878817489
#Sta/Elev= 30
9748.9232261.6059763.8322256.8459775.1262250.313 9786.422242.2639801.0112230.731
9831.3042202.1619842.325 2192.669846.6342190.3299853.3472187.904 9875.392185.091
9886.4122181.926 9908.292180.6559919.074 2176.939940.6432171.358 9972.752168.139
9983.3482164.8949993.9462160.53810004.542162.13810015.142167.43410025.742178.214
10036.35 2187.0810046.952192.00210090.072193.59710122.662201.41210156.36  2211.7
10178.982217.31610201.052220.43210214.652221.11610236.762223.70510250.832227.243
#Mann= 3 , 0 , 0
9748.923    0.12       09748.923    0.12       010250.83    0.12       0
#XS Ineff= 2 , 0
       0                               0
Bank Sta=9748.923,10250.83
Exp/Cntr=0.3,0.1

Type RM Length L Ch R = 1 ,28109.87,135.153000,135.153000,135.153000
XS GIS Cut Line= 2
  637581.1559605797683.804117665637959.845196635797781.460367665
#Sta/Elev= 30
9876.6482201.7979890.9452196.6819921.4832183.5649932.2532179.5239952.9082173.065
9963.2352170.3759973.5622165.2859983.8892152.5169994.2162148.80910004.54 2148.63
10014.872152.109 10025.22156.50510035.522158.94210045.852160.49810056.182162.753
10066.512163.87610076.83 2163.9410087.162165.24610107.812184.62810118.142190.084
10128.472193.481 10138.82195.12910159.452196.37510169.78 2197.8510180.112200.014
10200.762203.67610231.742209.64810242.072212.077 10252.4  2215.310267.73 2222.13
#Mann= 3 , 0 , 0
9876.648    0.12       09876.648    0.12       010267.73    0.12       0
#XS Ineff= 2 , 0
       0                               0
Bank Sta=9876.648,10267.73
Exp/Cntr=0.3,0.1

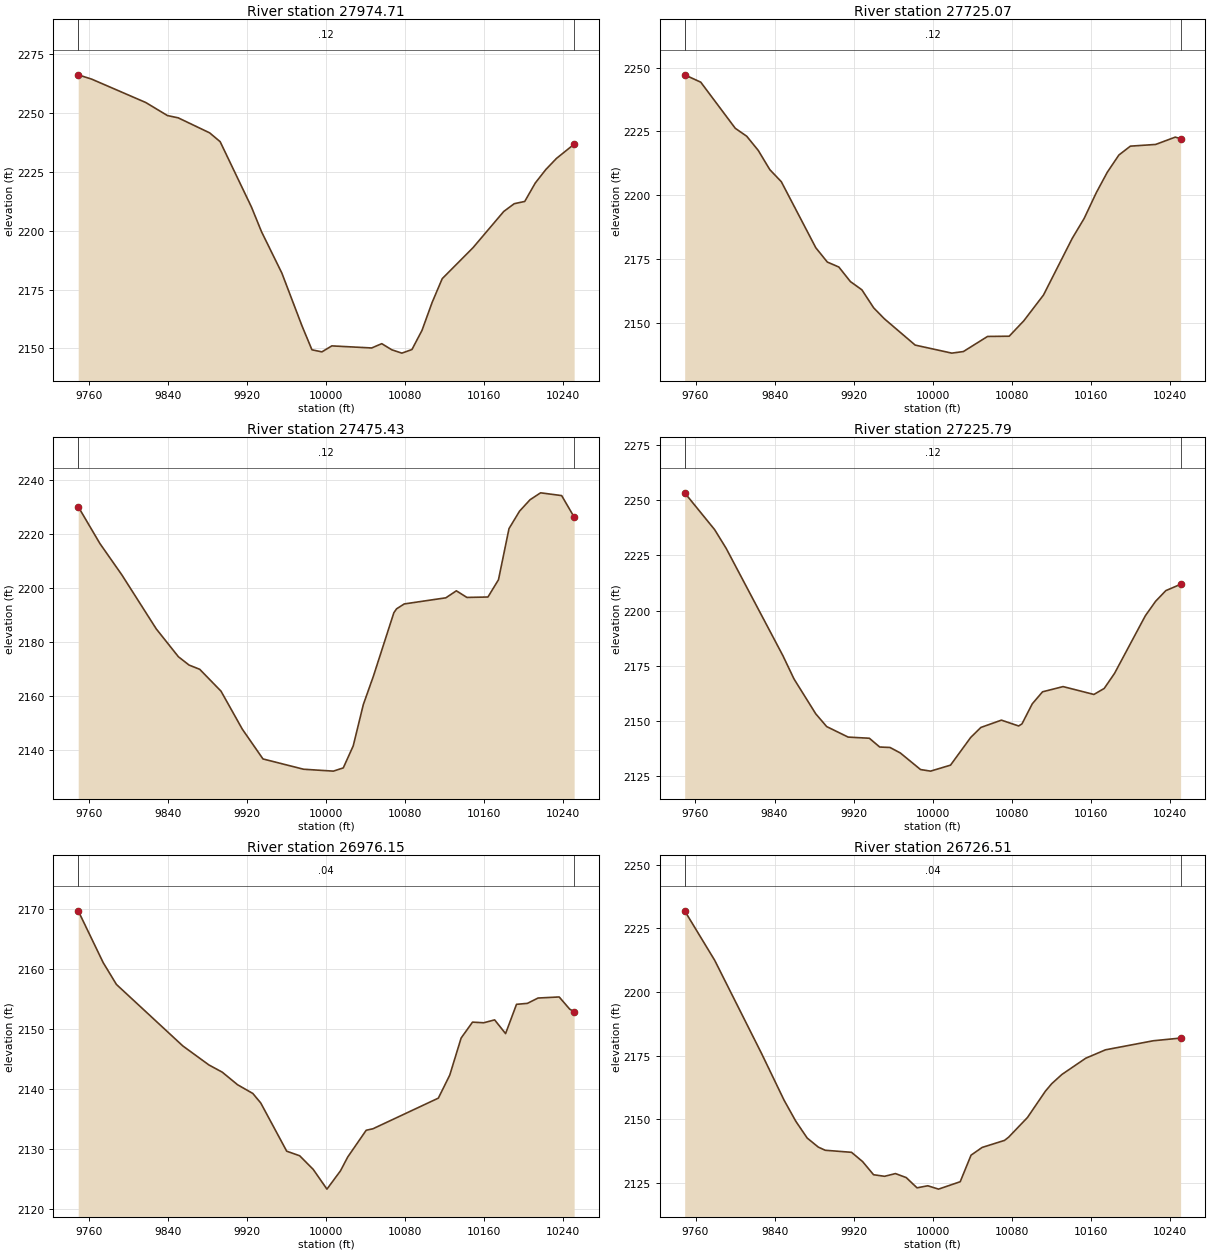
Type RM Length L Ch R = 1 ,27974.71,249.641200,249.641200,249.641200
XS GIS Cut Line= 6
637442.671188722797764.250850028 637531.85197719 797804.47884615
 637600.84559028797828.928665288637792.004421794797861.799715138
637858.129592409797880.193356523637921.822968855797903.962922433
#Sta/Elev= 30
9749.0982266.2559762.6232264.4419817.4752254.4859839.415 2248.949850.2722247.978
  9882.12241.5889892.7092237.8559924.3942210.0729934.6582199.5149955.1872181.973
9975.5252159.5699985.5972149.3949995.669 2148.5110005.732151.05710046.06 2150.17
10056.242151.99810066.432149.38710076.612147.977 10086.82149.50910096.982157.663
10107.172169.47610117.412179.61510148.552192.77310179.692208.19110190.272211.479
10200.942212.44910211.622220.29510222.292226.01710232.972230.70610250.922236.776
#Mann= 3 , 0 , 0
9749.098    0.12       09749.098    0.12       010250.92    0.12       0
#XS Ineff= 2 , 0
       0                               0
Bank Sta=9749.098,10250.92
Exp/Cntr=0.3,0.1

Type RM Length L Ch R = 1 ,27725.07,249.641300,249.641300,249.641300
XS GIS Cut Line= 6
637351.042048925797906.893778084637524.455570014798010.501267871
637590.962136625798045.437489088637692.884783461798117.308027165
637732.664782914798141.533822734637779.700831719798167.022929053
#Sta/Elev= 30
9749.0212247.181 9765.282244.3089800.2272226.2389811.8752223.1049823.5242217.548
9835.1732210.0449846.8222205.3129881.7692179.4129893.4172173.8259905.0662171.883
9916.7152166.1949928.3642162.9619940.3012155.8979951.0272151.6389982.2922141.304
 10019.42138.15610031.092138.77110055.572144.69210077.45 2144.7810092.272150.837
10112.162160.91910141.222183.09110153.342190.94410165.662201.05510176.762209.032
10188.472215.765 10200.12219.24210225.712219.908 10245.62222.78310250.942222.126
#Mann= 3 , 0 , 0
9749.021    0.12       09749.021    0.12       010250.94    0.12       0
#XS Ineff= 2 , 0
       0                               0
Bank Sta=9749.021,10250.94
Exp/Cntr=0.3,0.1

Type RM Length L Ch R = 1 ,27475.43,249.641200,249.641200,249.641200
XS GIS Cut Line= 6
637224.551127321798165.044437804637314.539680504798210.695831704
637380.330333437798237.093140945637423.467985697798248.496151208
637517.174596254798261.645255725637696.868139279798325.254814582
#Sta/Elev= 30
9749.1172230.1739771.1232216.4919793.2262204.9319828.1132184.8839850.5192174.566
9861.2942171.4899872.0692169.9229893.6192161.8159915.1692147.7419936.0852136.704
9977.1312132.89310007.29 2132.1910017.332133.38110027.392141.53210037.622156.847
10047.852167.40310068.522190.88210071.252192.31410079.032194.13510121.122196.406
10131.772199.00110142.422196.54810163.73  2196.710174.392203.10810185.042222.048
 10195.72228.51410206.352232.751   102172235.30410238.312234.28110250.962226.326
#Mann= 3 , 0 , 0
9749.117    0.12       09749.117    0.12       010250.96    0.12       0
#XS Ineff= 2 , 0
       0                               0
Bank Sta=9749.117,10250.96
Exp/Cntr=0.3,0.1

Type RM Length L Ch R = 1 ,27225.79,249.641300,249.641300,249.641300
XS GIS Cut Line= 6
 637149.05034525798385.065035097637244.503901582798439.851526043
637318.488423338798471.579794412637353.516535319798481.615515993
637426.175647158798494.784586969637619.331980053798550.226510331
#Sta/Elev= 30
9749.0572253.3749779.3612236.721 9791.042228.2369848.3832179.708  9859.72169.091
9881.748 2153.289892.7712147.524 9914.512142.7639935.9552142.242 9946.472138.265
9956.8722138.0639967.2742135.5859987.7652128.0729997.8952127.35310018.092130.058
10038.572142.61910048.822147.13110069.612150.43610087.052147.80310090.42 2148.74
10100.822157.81710111.232163.26910132.032165.63210163.242162.07310173.652164.797
10184.052171.57710215.262197.69910225.672204.26810236.072209.10910250.982211.957
#Mann= 3 , 0 , 0
9749.057    0.12       09749.057    0.12       010250.98    0.12       0
#XS Ineff= 2 , 0
       0                               0
Bank Sta=9749.057,10250.98
Exp/Cntr=0.3,0.1

Type RM Length L Ch R = 1 ,26976.15,249.641200,249.641200,249.641200
XS GIS Cut Line= 6
637096.190095258798548.313704389637300.323079145798729.173389732
637330.570873046798753.019158006 637410.86795017798802.791560786
637456.896229192798824.568825373637499.172957229798840.502236631
#Sta/Elev= 30
9749.0112169.6229774.2762161.0029787.7082157.3639854.8682147.1329881.249 2143.97
 9894.852142.7589910.2852140.671 9925.722139.2199933.7592137.6339960.014 2129.61
9973.1422128.8479986.9082126.56710000.752123.29210014.492126.34910021.792128.643
10040.482133.09110047.362133.344 10113.52138.44210125.022142.26410136.552148.443
10148.082151.09210159.412150.98710170.472151.46710181.542149.182 10192.62154.056
10203.662154.21710214.422155.10510235.792155.28310246.482153.24610250.942152.843
#Mann= 3 , 0 , 0
9749.011    0.04       09749.011    0.04       010250.94    0.04       0
#XS Ineff= 2 , 0
       0                               0
Bank Sta=9749.011,10250.94
Exp/Cntr=0.3,0.1

Type RM Length L Ch R = 1 ,26726.51,249.641300,249.641300,249.641300
XS GIS Cut Line= 6
636971.299141585798649.679636058637038.761620962798758.666778972
637108.161014159798907.461883248637140.349512522798963.406337828
637194.568210466799023.285658698637250.264060837799053.823984906
#Sta/Elev= 30
9749.0382231.8649779.4262212.424 9826.932175.7759849.6442157.4999861.5232149.227
9873.054 2142.639884.3542139.0719891.3022137.8529917.8532137.049 9929.022133.432
9940.1862128.2439951.3522127.6339962.3292128.6989973.2342127.1279984.1392123.108
9995.0432123.91110005.942122.59510027.862125.50510038.82 2135.9310050.052138.963
 10072.72141.73410076.892143.00510095.912150.72610114.022161.036 10120.42163.972
10130.782167.62310154.862173.98910174.85 2177.2910223.192180.84410250.882181.908
#Mann= 3 , 0 , 0
9749.038    0.04       09749.038    0.04       010250.88    0.04       0
#XS Ineff= 2 , 0
       0                               0
Bank Sta=9749.038,10250.88
Exp/Cntr=0.3,0.1

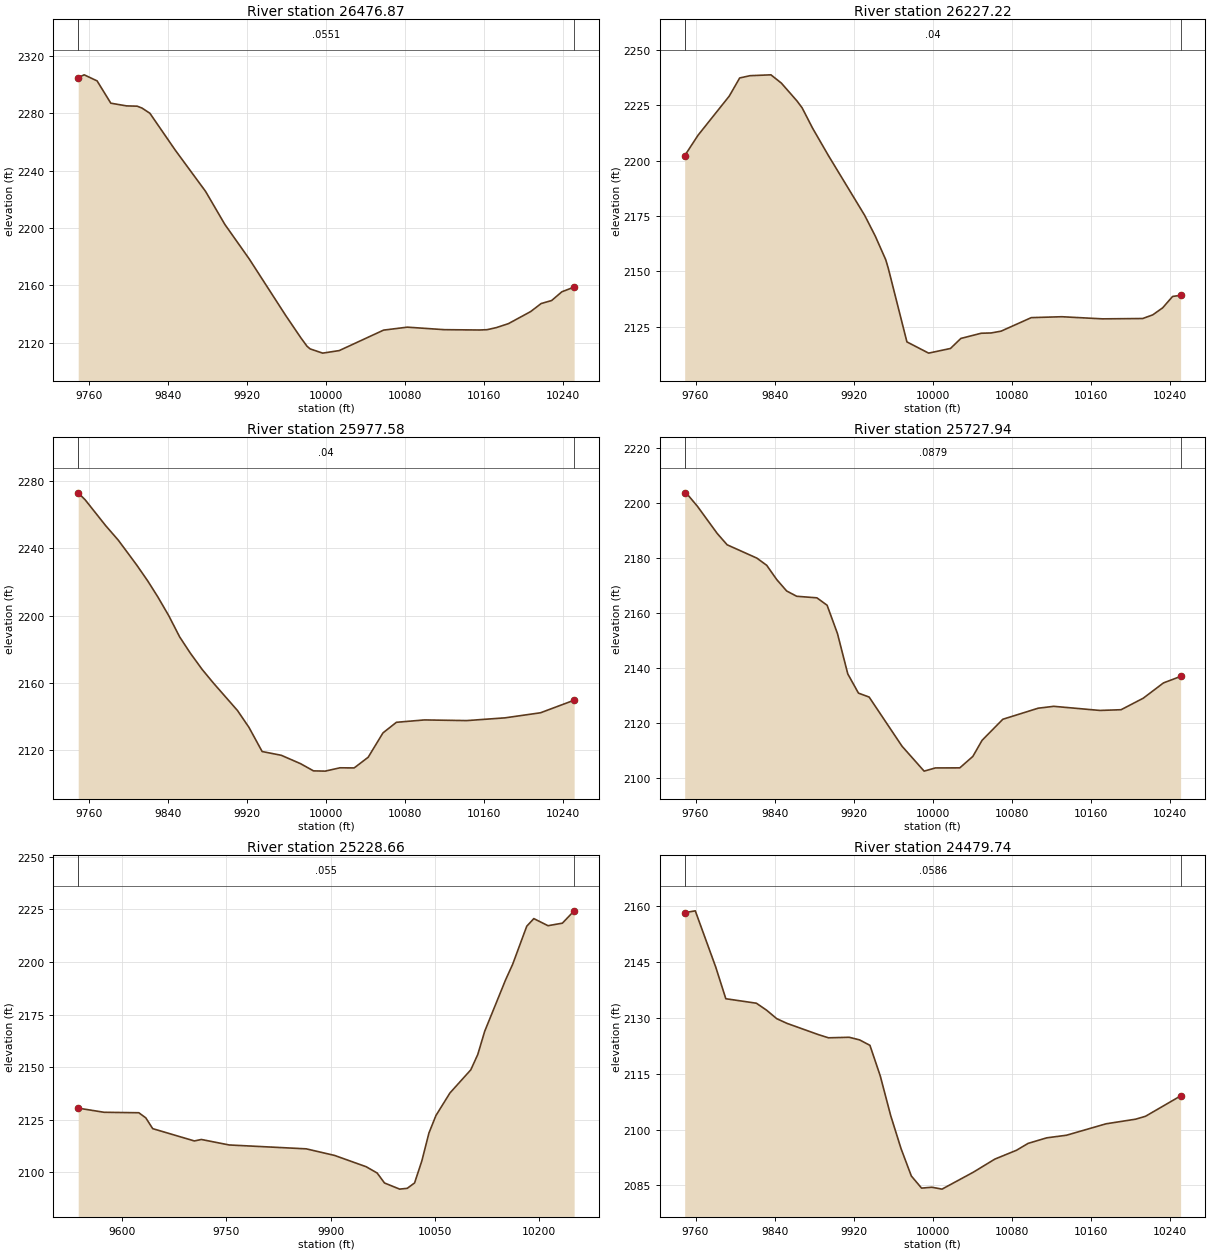
Type RM Length L Ch R = 1 ,26476.87,249.641200,249.641200,249.641200
XS GIS Cut Line= 6
636702.199631882798750.480185032636778.131596103798839.597706859
636931.678923915799051.776816755636950.750655011799070.454691558
636977.240550902799088.902707272637037.093732309 799110.25321743
#Sta/Elev= 30
9749.0262304.9459755.1092306.827 9768.152302.5859782.0282287.0489798.0322285.164
9808.6762284.9739813.6072283.6429821.5622280.0379847.3332254.2339877.9342225.544
9897.3942202.5779921.9992178.5669958.9072139.1739974.2142123.6139980.5982117.595
9983.7862115.7459996.4522112.815 10013.22114.58710058.042128.85410082.092130.917
10119.512129.16310154.862128.94210162.812129.14910172.22 2130.6210184.412133.369
10206.872141.77310217.522147.38610228.122149.48610238.432155.55610250.912158.871
#Mann= 3 , 0 , 0
9749.026  0.0551       09749.026  0.0551       010250.91  0.0551       0
#XS Ineff= 2 , 0
       0                               0
Bank Sta=9749.026,10250.91
Exp/Cntr=0.3,0.1

Type RM Length L Ch R = 1 ,26227.22,249.641300,249.641300,249.641300
XS GIS Cut Line= 6
636482.179239103799059.213781662636658.141266024799117.618933844
636761.447391047799157.861705687636795.702312832799157.453716525
636899.815877086799131.916240092636963.047509821799123.890504874
#Sta/Elev= 30
9749.0182202.1689762.5262211.4149794.1362229.1139804.6722237.2999815.209 2238.33
9836.2822238.7169846.8182234.9879862.6182226.9349867.8912223.7789878.4282214.627
9894.3622202.312 9931.112175.2659941.7652165.9639952.4732155.1749955.0512151.284
9973.8912118.0569995.8582112.98610017.96 2115.0910028.452119.61610049.082121.972
10059.112122.09510069.152122.90910099.752129.02610130.642129.42810171.832128.469
10212.47 2128.6210222.552130.25510232.632133.43910242.712138.59410250.822139.098
#Mann= 3 , 0 , 0
9749.018    0.04       09749.018    0.04       010250.82    0.04       0
#XS Ineff= 2 , 0
       0                               0
Bank Sta=9749.018,10250.82
Exp/Cntr=0.3,0.1

Type RM Length L Ch R = 1 ,25977.58,249.641200,249.641200,249.641200
XS GIS Cut Line= 6
636608.021290869 799424.88727962636684.056020794799401.998653762
636746.386716729799368.487999939 636832.73648416799298.401640921
636946.256402059799186.384381342637016.010268103799146.530621417
#Sta/Elev= 30
9749.0742273.1369756.2672268.8669776.8812253.5739789.6262244.9389808.3542230.063
 9819.58 2220.519829.6132211.1589840.6682199.9839851.723 2187.319862.3982177.735
9874.4692167.9429886.139 2159.649910.1942143.4829921.9112133.3549935.1922119.006
 9954.512116.7839974.0532111.7769987.1712107.487    99992107.33210013.942109.314
10028.22 2109.2410029.472109.73810042.512115.60410057.472130.11410071.092136.426
10099.472137.83110142.39 2137.4410180.942139.07510216.842142.09210250.932149.585
#Mann= 3 , 0 , 0
9749.074    0.04       09749.074    0.04       010250.93    0.04       0
#XS Ineff= 2 , 0
       0                               0
Bank Sta=9749.074,10250.93
Exp/Cntr=0.3,0.1

Type RM Length L Ch R = 1 ,25727.94,499.282500,499.282500,499.282500
XS GIS Cut Line= 6
636732.053340792799562.077636158636815.669836156799558.877284421
  636870.6216815799549.220290914636986.798870881799496.419417992
637035.315118045799444.947236385637113.091643976799301.549879406
#Sta/Elev= 30
9749.0462203.7619751.9932203.1189761.9942198.8329781.9962188.9419791.997 2184.83
9822.0572179.9759832.0772177.3459842.1572172.1669852.2422167.9949862.3982166.069
9882.8392165.4989893.1672162.7929903.6332152.4959914.0982137.7749924.8892130.778
9935.6822129.3479968.9132111.4679991.3052102.35610002.742103.51810027.44 2103.55
10040.642107.71810049.972113.58510070.95 2121.2510106.67 2125.2810122.522125.966
 10169.22124.46810190.642124.73310213.052128.92710233.512134.49910250.86 2136.87
#Mann= 3 , 0 , 0
9749.046  0.0879       09749.046  0.0879       010250.86  0.0879       0
#XS Ineff= 2 , 0
       0                               0
Bank Sta=9749.046,10250.86
Exp/Cntr=0.3,0.1

Type RM Length L Ch R = 1 ,25228.66,748.923800,748.923800,748.923800
XS GIS Cut Line= 6
 636887.79658553799634.758978769          637165799632.984356135
637306.580348445799603.524640227637376.794409614799628.398371071
637473.982877744799633.602783154637591.278116672799609.859756505
#Sta/Elev= 30
 9536.442130.5089573.6852128.5389623.7412128.3149633.7522125.9139643.7632120.763
9703.8232114.9089713.8332115.6129753.8722113.0059865.0022111.1569905.8592108.018
9951.3022102.6589967.0872099.6779977.6872094.9399999.5512092.01210010.462092.398
10021.012094.95310031.472105.39710041.682118.64610051.842127.01710071.972137.719
10102.02 2148.7210112.022155.97510122.032167.02110152.192191.52510162.262198.825
10182.612216.96410192.822220.59710213.252217.21910233.982218.42410250.91 2224.29
#Mann= 3 , 0 , 0
 9536.44   0.055       0 9536.44   0.055       010250.91   0.055       0
#XS Ineff= 2 , 0
       0                               0
Bank Sta=9536.44,10250.91
Exp/Cntr=0.3,0.1

Type RM Length L Ch R = 1 ,24479.74,499.282500,499.282500,499.282500
XS GIS Cut Line= 6
636564.586959042800005.326489978636658.433362238799982.063211604
636780.245705153799943.773676126636831.192817509799930.081117755
 636896.18277437799903.555033683637050.491323453799902.665267072
#Sta/Elev= 30
9749.0292158.1829759.7572158.6919780.3632143.6739790.6652135.1059821.5732133.901
9831.8762132.0379842.1792129.7529852.5992128.4899884.046  2125.59894.5292124.621
9915.4942124.7629925.976 2124.069936.4582122.6039946.9412114.3779957.423 2103.79
9967.9062094.9179978.3312087.5559988.6952084.2899999.0582084.52410009.412084.019
10040.922088.53610062.812092.07110084.772094.44910096.492096.29310115.312097.778
10135.312098.47810175.312101.54310205.312102.78710215.312103.569 10250.8 2109.03
#Mann= 3 , 0 , 0
9749.029  0.0586       09749.029  0.0586       0 10250.8  0.0586       0
#XS Ineff= 2 , 0
       0                               0
Bank Sta=9749.029,10250.8
Exp/Cntr=0.3,0.1

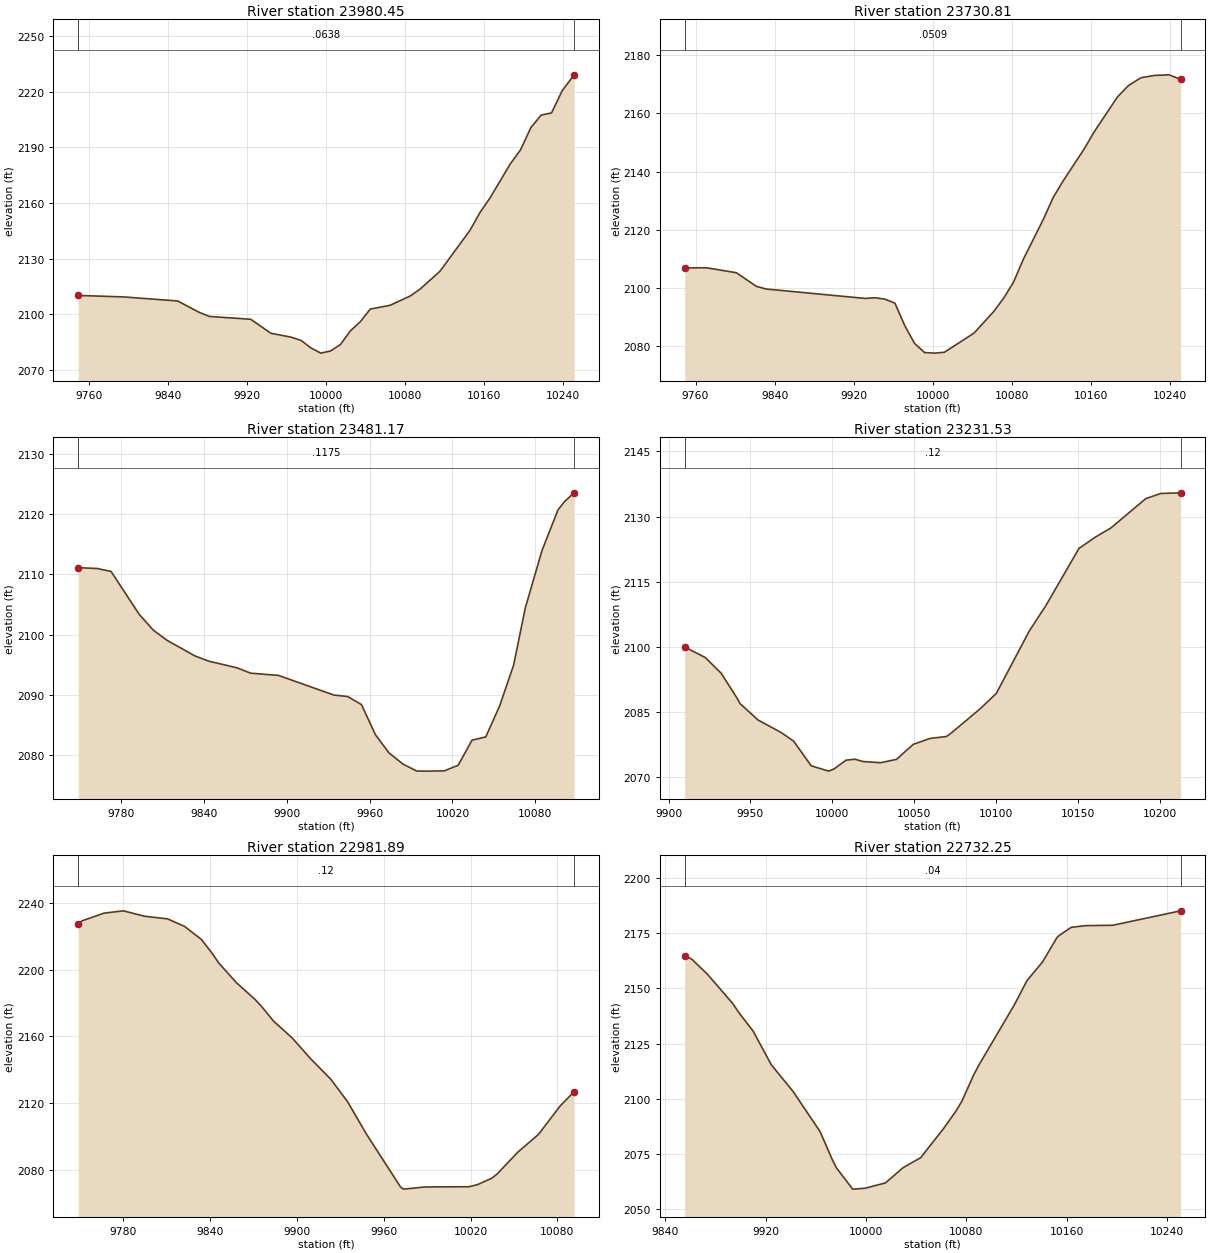
Type RM Length L Ch R = 1 ,23980.45,249.641300,249.641300,249.641300
XS GIS Cut Line= 6
636913.351095792800264.835044657637007.290309573800222.152011026
637078.423211068  800198.5646517637278.015766086800178.878982018
637335.855819584800167.188453528637396.401308589800147.300603376
#Sta/Elev= 30
9749.0832110.097 9794.832109.3019849.7492107.1259871.1382101.0759881.7952098.779
9923.7012097.2469944.0952089.6949964.4062087.6219974.5522085.8659984.5582081.812
9994.5642078.99810004.57 2080.1810014.572083.73310024.582091.06710034.582095.948
10044.592102.73510064.712104.80110084.842109.72610094.912113.48110115.042123.073
10145.472145.17910155.672154.84910165.882162.76710186.282180.99910196.692188.596
10207.122200.60210217.552207.34110228.032208.48910238.732220.40610250.922229.038
#Mann= 3 , 0 , 0
9749.083  0.0638       09749.083  0.0638       010250.92  0.0638       0
#XS Ineff= 2 , 0
       0                               0
Bank Sta=9749.083,10250.92
Exp/Cntr=0.3,0.1

Type RM Length L Ch R = 1 ,23730.81,249.641200,249.641200,249.641200
XS GIS Cut Line= 6
636893.169031081800453.784601374637019.609111251800439.157896223
637209.461816503800440.078825348637271.048624105800434.438827621
637326.085216072800413.926772762637372.667977616800370.833007585
#Sta/Elev= 30
9749.0292106.7679771.0862106.8499801.397 2105.139821.5822100.4389831.6152099.516
9931.7782096.276 9941.782096.5159951.7822096.0239961.7852094.6579971.7872086.872
9981.7892080.7269991.7912077.63510001.792077.43410011.792077.724 10041.82084.314
 10061.82091.78410071.812096.35510081.822101.90410091.832109.84110111.972123.509
10122.062131.12310132.252136.88710152.942147.56910163.852153.87810187.132165.759
10198.02 2169.5910210.712172.30110224.222173.09710239.212173.313 10250.92171.764
#Mann= 3 , 0 , 0
9749.029  0.0509       09749.029  0.0509       0 10250.9  0.0509       0
#XS Ineff= 2 , 0
       0                               0
Bank Sta=9749.029,10250.9
Exp/Cntr=0.3,0.1

Type RM Length L Ch R = 1 ,23481.17,249.641300,249.641300,249.641300
XS GIS Cut Line= 6
636891.537746806 800713.93156427637023.501644898800694.063574115
 637090.42736582800689.203367715637190.823423553800687.642519231
637213.364478957800684.593134036637245.964397451800671.468310861
#Sta/Elev= 30
9749.027 2111.089762.6832110.9459772.8272110.4579793.1162103.377 9803.262100.752
9813.4052099.0419833.609 2096.459843.6912095.5839863.8542094.4999873.9352093.598
9894.0352093.232 9934.142089.9769944.1672089.7329954.1812088.3889964.182 2083.43
9974.1822080.3619984.1832078.5459994.1832077.37910004.182077.36810014.192077.418
10024.192078.33910034.192082.49710044.192083.04310054.232088.18310064.322094.926
10072.772104.39210084.942113.95910096.492120.66910101.462122.10310108.172123.484
#Mann= 3 , 0 , 0
9749.027  0.1175       09749.027  0.1175       010108.17  0.1175       0
#XS Ineff= 2 , 0
       0                               0
Bank Sta=9749.027,10108.17
Exp/Cntr=0.3,0.1

Type RM Length L Ch R = 1 ,23231.53,249.641200,249.641200,249.641200
XS GIS Cut Line= 6
637178.400865463800993.960970678637195.639102226800965.908544808
637221.873931245800899.852883506637233.583745238800842.156454509
 637248.14361024800745.769849155637258.177563194800704.327923231
#Sta/Elev= 30
9909.8212099.9919922.4262097.5689932.0762093.9699941.5262088.4029943.7422086.933
9954.7022083.1749968.6422080.336 9976.432078.3139987.1292072.6429997.8272071.418
   100012071.90410008.492073.94810013.892074.15810018.842073.62710029.612073.358
10039.252074.12410049.452077.56910059.662078.93610069.862079.39610072.762080.203
10090.112085.67810100.232089.28910120.452103.69510130.572109.53610150.792122.689
10160.912125.30710170.242127.37910191.562134.13110200.752135.32610212.892135.475
#Mann= 3 , 0 , 0
9909.821    0.12       09909.821    0.12       010212.89    0.12       0
#XS Ineff= 2 , 0
       0                               0
Bank Sta=9909.821,10212.89
Exp/Cntr=0.3,0.1

Type RM Length L Ch R = 1 ,22981.89,249.641300,249.641300,249.641300
XS GIS Cut Line= 6
637530.463026671800962.149106002637519.323626621800918.820886848
637484.827607524 800864.10841109637415.224625098800776.617298415
637365.210843802800732.847004502637328.969105697800693.234011342
#Sta/Elev= 30
9749.0812227.7629751.9272229.5629766.8622234.1279780.3172235.5249794.8212232.279
9810.806 2230.689822.3722226.245 9834.132218.3579841.6992209.8259846.2982203.971
9858.4672192.2319871.1912182.2479875.3382178.449 9883.972169.2239896.7482159.201
9909.5262146.6739923.5252134.2689935.0832120.8179947.8622101.6679971.6562069.526
9973.7492068.215 9988.572069.52410019.082069.66610024.972070.96910034.512074.698
10038.132077.08810052.592090.37210067.052101.21610081.712118.01910091.572126.823
#Mann= 3 , 0 , 0
9749.081    0.12       09749.081    0.12       010091.57    0.12       0
#XS Ineff= 2 , 0
       0                               0
Bank Sta=9749.081,10091.57
Exp/Cntr=0.3,0.1

Type RM Length L Ch R = 1 ,22732.25,249.641200,249.641200,249.641200
XS GIS Cut Line= 6
637669.418118224800678.557665273637555.921200236800587.343343001
637494.536880732800527.911138714637462.402271229800486.821491089
637440.437533974800446.944808209 637425.93414688800382.267992548
#Sta/Elev= 30
9855.3752164.8939861.1652163.2289873.6522156.379 9893.712143.1869899.0042138.761
9909.9822130.6789924.4572115.4599941.7342103.4359963.3742085.1759973.1312072.411
9976.347 2068.829989.3192059.158    99992059.53410015.462061.98110029.482068.868
10043.572073.414 10062.22086.90510071.732094.577 10076.42098.99110085.822110.934
10090.17 2115.5610118.182142.57110128.252153.54910140.712162.04110152.132173.012
10153.972174.03110163.552177.69210174.962178.46110196.68 2178.6310250.772185.167
#Mann= 3 , 0 , 0
9855.375    0.04       09855.375    0.04       010250.77    0.04       0
#XS Ineff= 2 , 0
       0                               0
Bank Sta=9855.375,10250.77
Exp/Cntr=0.3,0.1

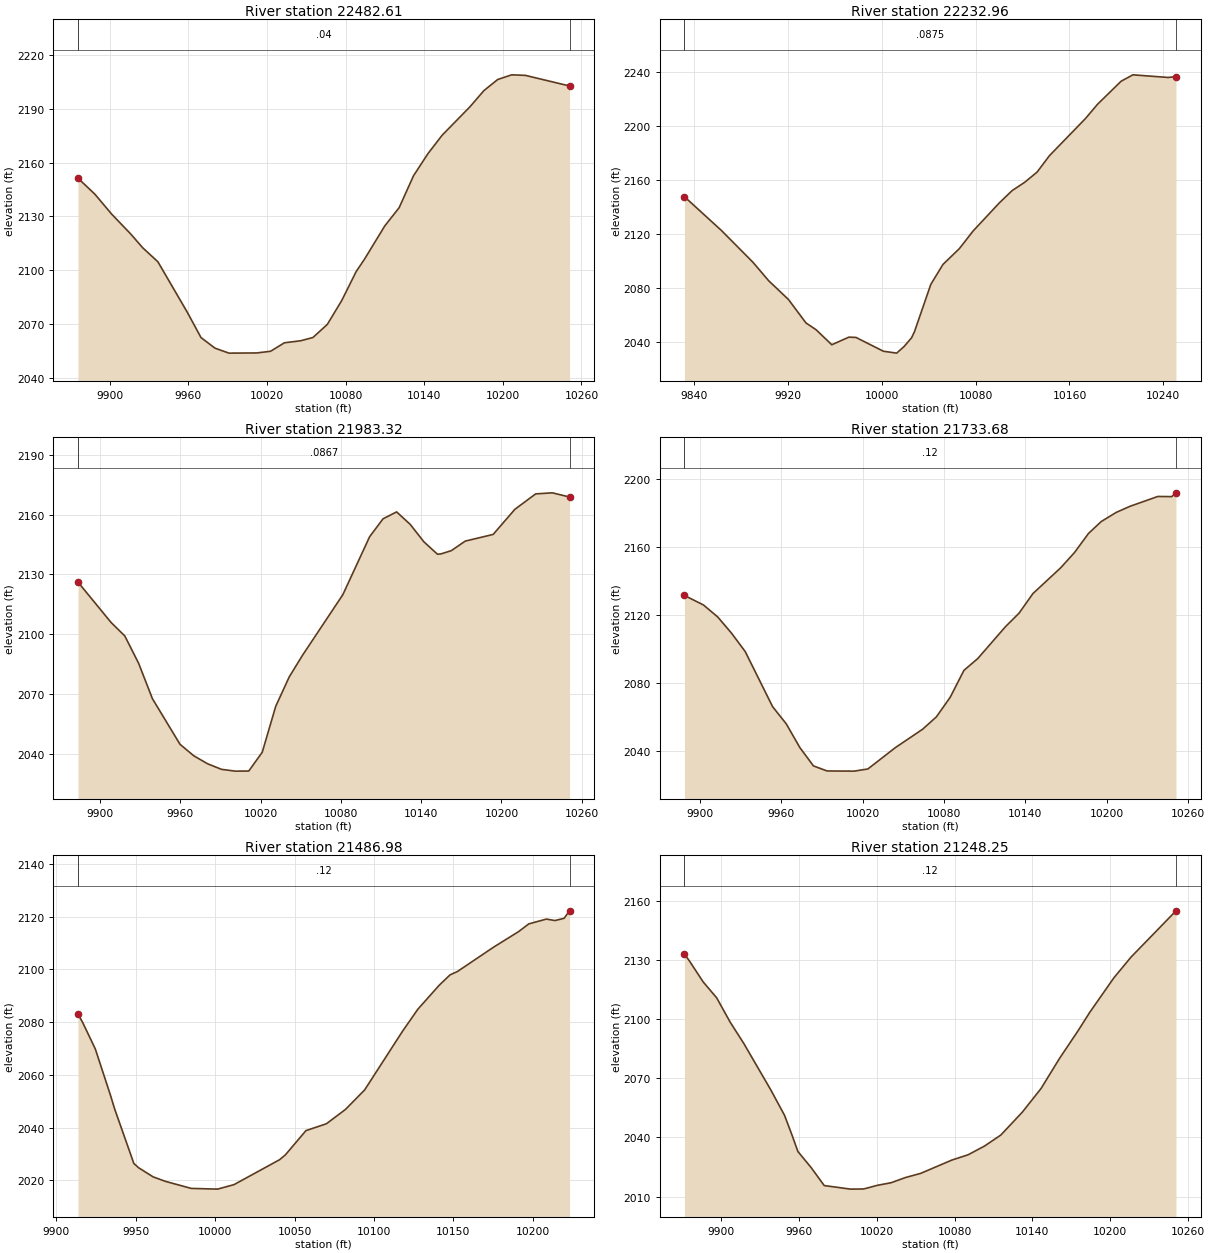
Type RM Length L Ch R = 1 ,22482.61,249.641300,249.641300,249.641300
XS GIS Cut Line= 6
637818.778299493800565.161076672637801.649037672800543.446441905
637774.708806522800495.549815697637748.250518624800420.778652356
637701.773978966800317.294710166637672.155105486800222.251712319
#Sta/Elev= 30
9875.8342151.3139888.7762142.3649901.5132131.298 9916.122120.1599925.1892112.519
 9936.79  2104.7 9959.09 2076.739969.7292062.3839980.3682056.4969991.0082053.725
10012.192053.82510022.77 2054.7610033.362059.49310045.762060.62110055.122062.448
10066.082069.74610077.052083.01810088.012099.10110094.572106.27210109.932124.687
10120.892134.86210131.862152.67510142.822164.973 10153.72175.29110174.932191.154
10185.542200.16410196.152206.40210206.772208.99110217.19 2208.6910250.93 2202.77
#Mann= 3 , 0 , 0
9875.834    0.04       09875.834    0.04       010250.93    0.04       0
#XS Ineff= 2 , 0
       0                               0
Bank Sta=9875.834,10250.93
Exp/Cntr=0.3,0.1

Type RM Length L Ch R = 1 ,22232.96,249.641200,249.641200,249.641200
XS GIS Cut Line= 6
638045.401741185800417.382178431637954.688543541800318.826388271
637909.696600709800290.940033757637886.823204263800266.985952476
637848.972244544800185.655188011637835.052090157800078.287368396
#Sta/Elev= 30
  9831.62147.6259863.0612122.6799889.9812099.1149903.4412085.3839920.3042071.509
9935.2442054.138 9943.822049.127 9957.282037.9659971.833 2043.599977.8512043.405
10001.332033.145 10012.62031.75710018.912036.62810025.272043.07610027.722047.443
10041.722082.65810052.112097.46410066.052109.12110077.672122.08710100.222143.077
10111.082152.13410121.842158.32310132.362165.82910142.872177.96910173.712205.583
10183.832215.99410204.072233.17910214.082237.88110244.11 2235.9310250.832236.534
#Mann= 3 , 0 , 0
  9831.6  0.0875       0  9831.6  0.0875       010250.83  0.0875       0
#XS Ineff= 2 , 0
       0                               0
Bank Sta=9831.6,10250.83
Exp/Cntr=0.3,0.1

Type RM Length L Ch R = 1 ,21983.32,249.641300,249.641300,249.641300
XS GIS Cut Line= 6
638191.319744003800359.263887721638162.965074685800238.500236066
638158.120350647800175.565628195638168.983974487800092.407220891
638184.596244156800039.370096656638199.782823241800001.494639144
#Sta/Elev= 30
9883.5432126.0889908.2792105.8369918.5462099.0619928.8562085.3569939.1672067.595
9959.789 2044.71  9970.12038.933 9980.412034.9369990.7212032.161   100012031.252
10011.152031.28710021.242040.74110031.322063.77210041.382078.48710051.39 2089.44
10081.432119.72710101.492148.86510111.522157.85210121.662161.31710131.832155.052
   101422146.33710152.172140.08910154.812140.24210162.532141.87510172.952146.668
 10193.82150.01410210.092162.63910225.57 2170.3510238.052170.885 10250.92168.784
#Mann= 3 , 0 , 0
9883.543  0.0867       09883.543  0.0867       0 10250.9  0.0867       0
#XS Ineff= 2 , 0
       0                               0
Bank Sta=9883.543,10250.9
Exp/Cntr=0.3,0.1

Type RM Length L Ch R = 1 ,21733.68,246.701400,246.701400,246.701400
XS GIS Cut Line= 6
638231.879020218800374.686032418638253.973048496800366.912695147
638286.396241543800361.290053432638359.008105057800356.005495673
 638411.11071556 800349.19402247638588.086368375800313.476784269
#Sta/Elev= 30
9888.6972131.659 9902.752126.0439913.2032119.0189923.3552109.5069933.5022098.612
9953.6962066.1559963.7242056.0749973.7522042.099 9983.782031.2729993.8082028.292
10013.862028.19510023.92 2029.4710044.092042.00610064.262052.87410074.372060.134
10084.542071.645 10094.72087.54610104.872094.483 10125.22113.17110135.362121.269
10145.572132.78410166.022147.95710176.242156.98410186.472168.14410195.882175.178
10206.92 2180.5610217.15 2184.18 10237.62189.95210247.832189.85610250.982192.093
#Mann= 3 , 0 , 0
9888.697    0.12       09888.697    0.12       010250.98    0.12       0
#XS Ineff= 2 , 0
       0                               0
Bank Sta=9888.697,10250.98
Exp/Cntr=0.3,0.1

Type RM Length L Ch R = 1 ,21486.98,238.731400,238.731400,238.731400
XS GIS Cut Line= 6
638203.361193885800505.988134818638257.818760115800580.843812261
638275.058127621800599.162828569638304.107567006800623.102109212
638342.571569493800648.884518734 638438.11523518800699.024127453
#Sta/Elev= 30
9913.5652083.047 9916.462079.9329924.4982069.8079934.1212052.119 9936.63 2047.16
9948.7622026.4459951.7832024.8229960.9022021.3719968.5912019.6819984.8632017.011
10001.49 2016.7310011.892018.44510040.512027.85610044.222029.71110057.182038.898
10070.052041.49110082.092046.93310094.132054.29710118.072076.59210127.69  2084.9
10141.062093.92810147.982097.91510152.552099.153 10175.32108.36210191.162114.297
10197.542117.21410208.652119.03410214.032118.47810219.772119.31510223.242122.161
#Mann= 3 , 0 , 0
9913.565    0.12       09913.565    0.12       010223.24    0.12       0
#XS Ineff= 2 , 0
       0                               0
Bank Sta=9913.565,10223.24
Exp/Cntr=0.3,0.1

Type RM Length L Ch R = 1 ,21248.25,249.641200,249.641200,249.641200
XS GIS Cut Line= 6
638046.103990261800601.228766982638070.851219347800680.490682406
 638079.77707514800733.566412942638092.708369325800766.532815135
638140.375012457800832.882083102638231.211634629800918.954178914
#Sta/Elev= 30
9871.4292132.931 9875.382129.3469885.8562118.8559896.3322110.7439906.808 2098.36
9917.2842087.6039938.2362063.9449948.7122051.2119954.4642041.235 9959.042032.861
9969.1862024.7859979.3332015.6369999.6222013.81910009.782013.90110020.182015.716
10031.032017.07210042.122019.70410053.782021.79510077.82 2028.5310090.432031.229
10103.052035.63310115.672041.22710132.272052.83710146.662064.75910161.052080.124
10175.442094.21610184.182103.26510203.052120.99610216.262131.44510250.882154.836
#Mann= 3 , 0 , 0
9871.429    0.12       09871.429    0.12       010250.88    0.12       0
#XS Ineff= 2 , 0
       0                               0
Bank Sta=9871.429,10250.88
Exp/Cntr=0.3,0.1

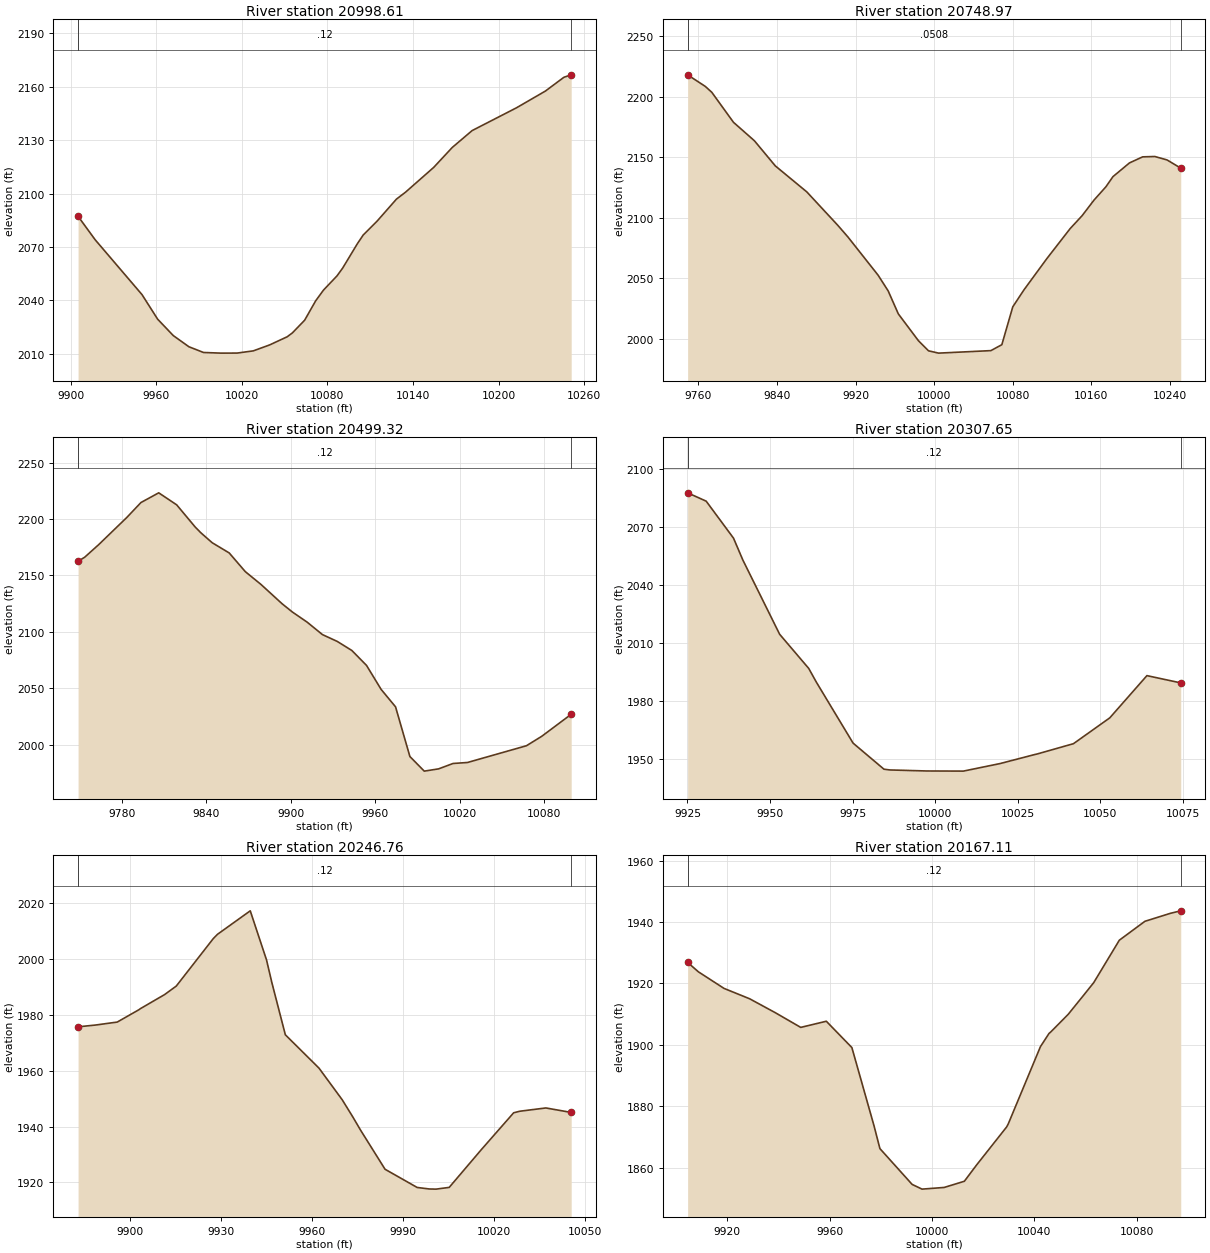
Type RM Length L Ch R = 1 ,20998.61,249.641300,249.641300,249.641300
XS GIS Cut Line= 6
637817.723297109800724.038227746637853.523515128800804.366082316
 637874.80392605800843.645857118637890.947719541800866.330450058
637931.770529658800908.183875469638028.894292817800989.641736451
#Sta/Elev= 30
9905.1842087.2269917.1672074.056 9950.022043.2499960.9712029.4729971.9222020.268
9982.8732013.992 9993.132010.76510005.422010.40310016.732010.43310028.042011.667
10039.482015.00510051.76 2019.5610055.41 2021.7310064.032028.86710071.742039.727
 10077.32045.83410086.732053.76810090.722058.17810100.972071.775 10105.12076.718
 10114.82084.47710128.392096.84910134.782100.77110154.492114.64710167.542125.868
10181.46 2135.3410212.592148.143 10232.82157.51210245.852165.28610250.932166.648
#Mann= 3 , 0 , 0
9905.184    0.12       09905.184    0.12       010250.93    0.12       0
#XS Ineff= 2 , 0
       0                               0
Bank Sta=9905.184,10250.93
Exp/Cntr=0.3,0.1

Type RM Length L Ch R = 1 ,20748.97,249.641800,249.641800,249.641800
XS GIS Cut Line= 6
637570.294019555800951.190536916637697.195591718800994.365454125
637822.925571688801024.131580825637856.347813902801036.069550406
637926.738421904801074.518711024638026.174621781801146.104051261
#Sta/Elev= 30
9749.1522218.2439767.1312208.6679773.7262203.8359795.7792179.0289817.0982163.757
9838.4162142.9539870.3942121.5079901.8272093.9939912.1812084.3189943.0172052.607
9953.2712039.5749963.5252020.6989984.0321998.4779994.2861990.13610004.511988.227
10057.751990.30210068.881995.19610080.012026.494 10091.4 2040.5310114.712066.378
10138.412091.15710150.532101.79410162.65 2114.6810174.772125.70410181.962134.092
10198.742145.43510212.12 2150.4410224.572150.72810237.022147.88310250.942141.133
#Mann= 3 , 0 , 0
9749.152  0.0508       09749.152  0.0508       010250.94  0.0508       0
#XS Ineff= 2 , 0
       0                               0
Bank Sta=9749.152,10250.94
Exp/Cntr=0.3,0.1

Type RM Length L Ch R = 1 ,20499.32,191.670100,191.670100,191.670100
XS GIS Cut Line= 6
637480.315828143800977.441554368  637525.4341415800978.747388766
637567.835262109801027.196972713637595.714035228801089.210990676
637621.191962892801196.173541052637643.540697076801254.187122879
#Sta/Elev= 30
9748.9112162.5649753.5972166.1419763.6012177.336 9783.612201.4379793.6142214.587
9806.2222223.1719818.9982212.5169832.1022192.9459836.1722187.7779844.2032178.989
9856.3052169.9429867.7312153.4049878.9662141.9649893.7392125.1199901.0872117.734
 9911.812108.5479922.5332097.6559933.0712091.6059943.4762083.5599953.8812070.352
9964.2852049.059  9974.52033.6949984.6941989.6849994.8871976.759 10005.1 1978.76
10015.361983.53210025.611984.40210067.51 1999.2410078.352007.57210099.312027.096
#Mann= 3 , 0 , 0
9748.911    0.12       09748.911    0.12       010099.31    0.12       0
#XS Ineff= 2 , 0
       0                               0
Bank Sta=9748.911,10099.31
Exp/Cntr=0.3,0.1

Type RM Length L Ch R = 1 ,20307.65,60.893700,60.893700,60.893700
XS GIS Cut Line= 2
637418.899139553801169.951888442637484.458038181801304.212920517
#Sta/Elev= 21
 9925.042087.8959930.6582083.5749938.9442064.3799941.7872052.9859952.9152014.533
9961.7351996.7989964.0441989.6769975.1721958.0539984.5261944.523  9986.31944.137
9997.4291943.60110007.321943.54710008.561943.52510019.691947.44310030.111952.087
10030.811952.35510041.941957.756 10052.91971.10510053.071971.403 10064.21993.065
10074.451989.294
#Mann= 3 , 0 , 0
 9925.04    0.12       0 9925.04    0.12       010074.45    0.12       0
#XS Ineff= 2 , 0
       0                               0
Bank Sta=9925.04,10074.45
Exp/Cntr=0.3,0.1

Type RM Length L Ch R = 1 ,20246.76,79.652100,79.652100,79.652100
XS GIS Cut Line= 6
637335.811617569801160.866151096637350.451324782801175.318285609
637374.242048654801209.396388919637387.623583724801237.401005856
 637395.70314055801260.923497559637410.729806874801302.861418423
#Sta/Elev= 28
9882.9581975.7059888.8421976.3659895.869 1977.419903.0771981.866 9903.53 1982.23
9911.4761987.2429915.3371990.2969927.5332007.2859928.9452008.8389939.7292017.229
9945.0911999.6669946.8491991.5589951.3011972.8599962.3841960.9399970.0431949.612
9973.4671943.5949976.1281938.6869984.1681924.7359994.7491918.2189998.7041917.679
    99991917.666   100011917.61710005.331918.23910015.951931.79310026.581944.945
10028.561945.491 10037.21946.67210045.551945.063
#Mann= 3 , 0 , 0
9882.958    0.12       09882.958    0.12       010045.55    0.12       0
#XS Ineff= 2 , 0
       0                               0
Bank Sta=9882.958,10045.55
Exp/Cntr=0.3,0.1

Type RM Length L Ch R = 1 ,20167.11,24.227400,24.227400,24.227400
XS GIS Cut Line= 4
637302.984441668801200.761923209637303.119813889801273.651930928
637358.271252394801315.450915918637409.012043774801313.654781714
#Sta/Elev= 28
 9904.441926.8449908.6791923.7629918.6791918.3749928.6791915.0029938.6791910.484
9948.679 1905.679958.6791907.6759968.6791899.0979977.3311873.6379979.5621866.442
 9979.691866.1399992.237 1854.529996.1181852.97710004.781853.52510012.67 1855.54
10017.331860.71310029.231873.26310029.881874.30910042.431899.41410045.791903.702
10046.53 1904.2410053.26 1909.9110059.281916.11110063.271920.26410073.281934.078
10083.281940.23410093.291942.847 10097.31943.649
#Mann= 3 , 0 , 0
 9904.44    0.12       0 9904.44    0.12       0 10097.3    0.12       0
#XS Ineff= 2 , 0
       09955.185                       0
Bank Sta=9904.44,10097.3
Exp/Cntr=0.3,0.1