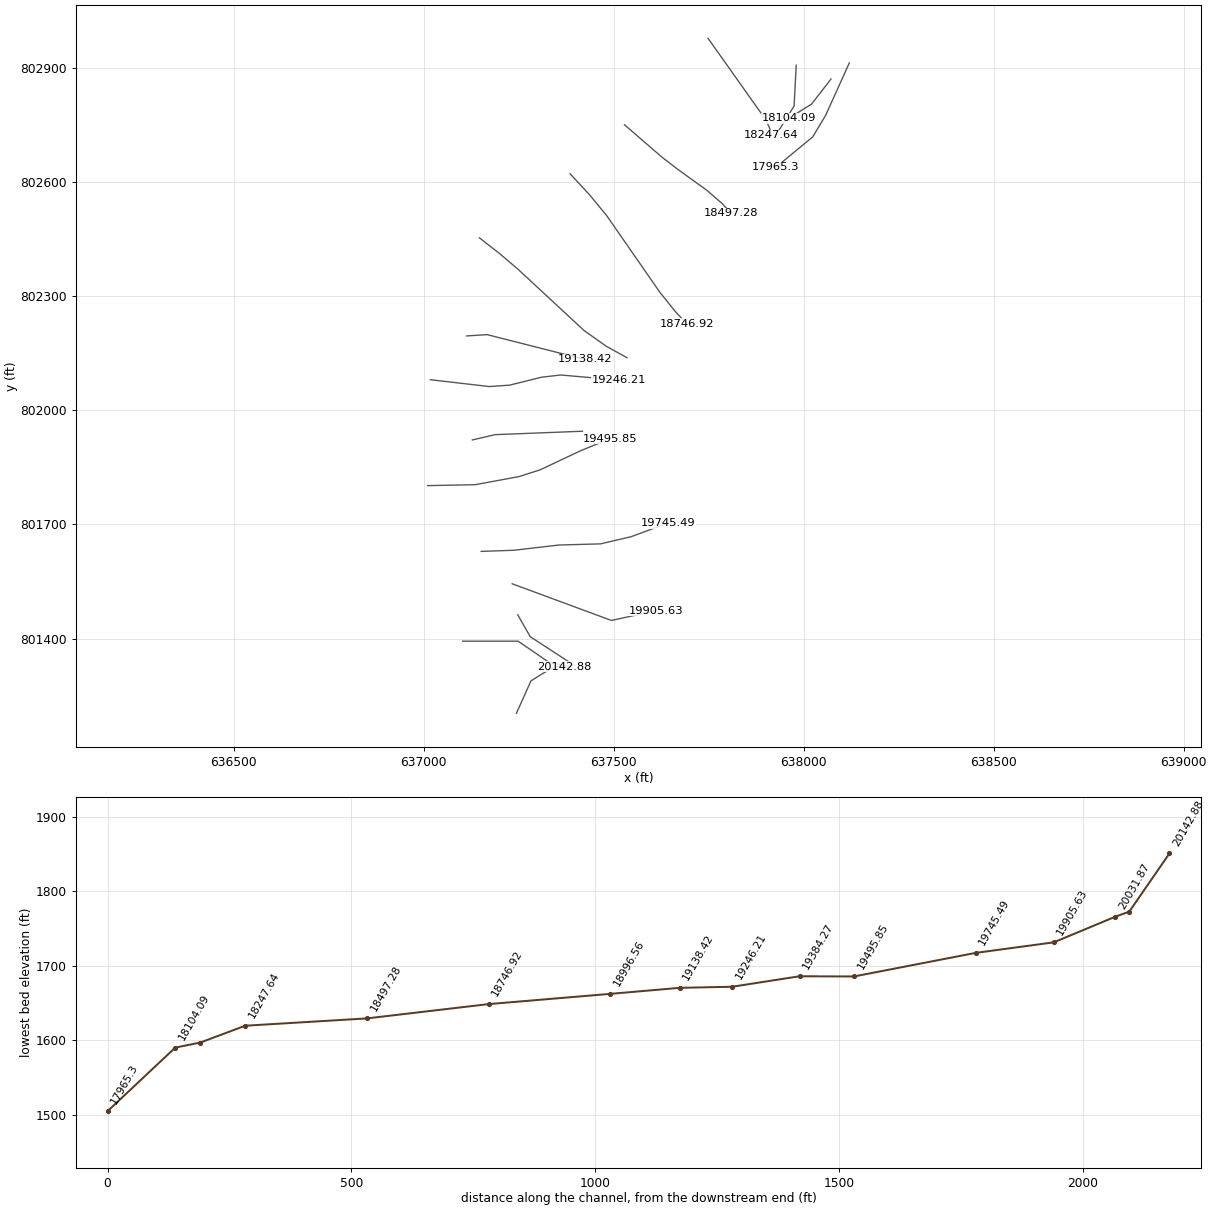
HEC-RAS study 12582_ras.prj: 12582

--- 12582_ras.g01 (geometry) --- (continued)

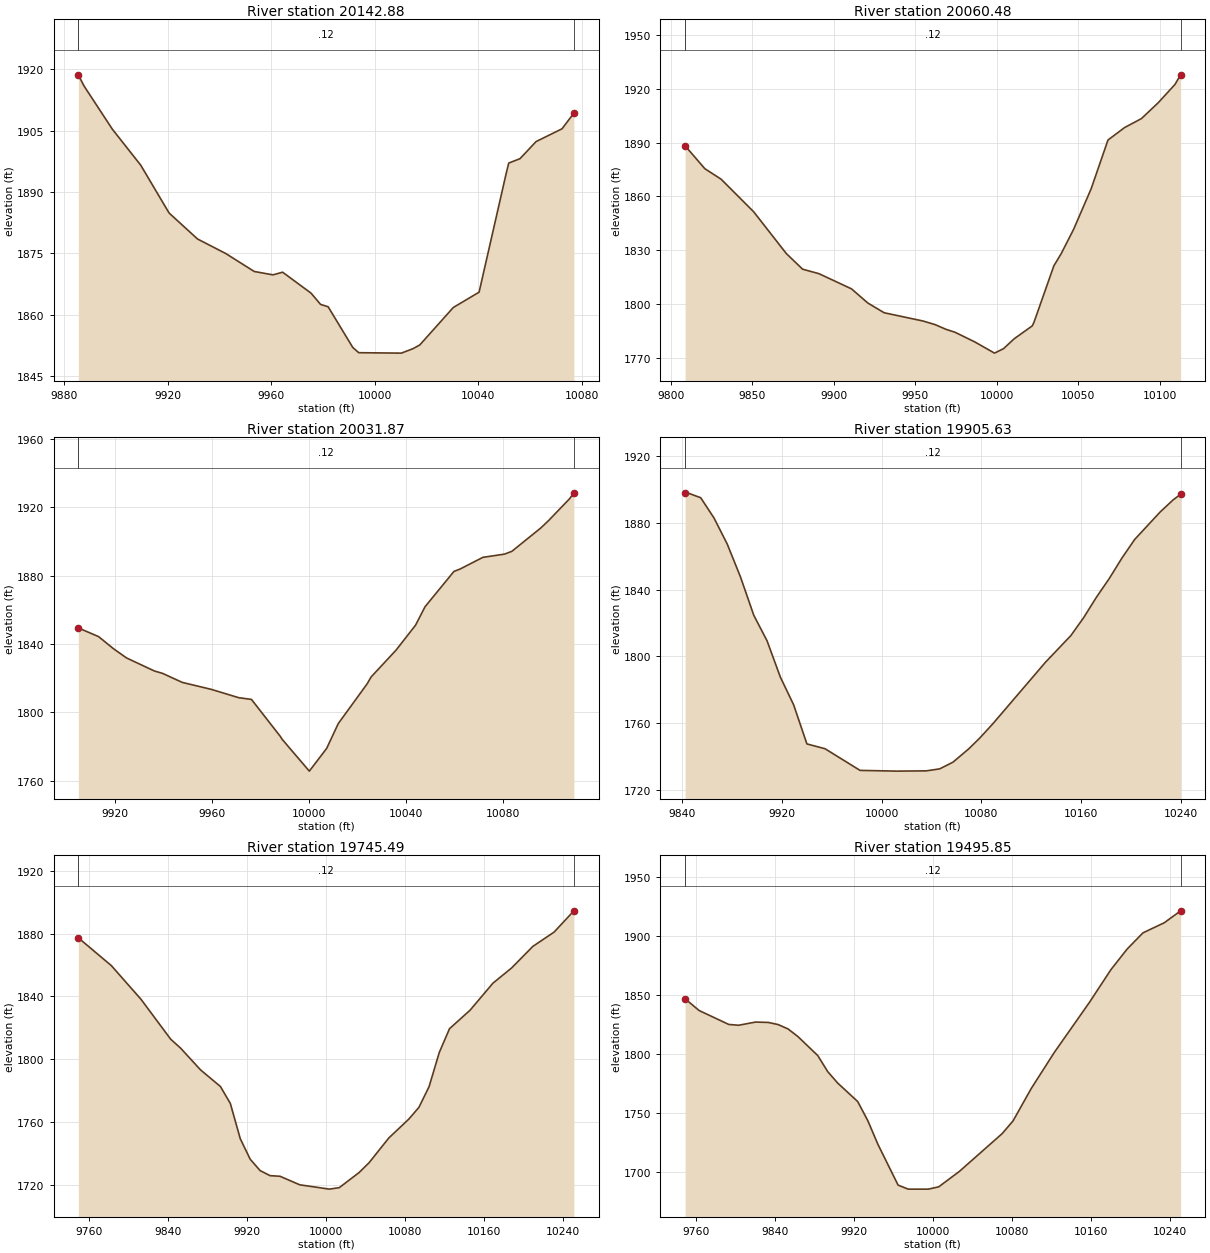
Type RM Length L Ch R = 1 ,20142.88,82.399000,82.399000,82.399000
XS GIS Cut Line= 5
637244.260578305801203.003292024637282.523705542801288.369953275
637312.740582824801307.415097743  637348.7832762801327.561232045
637369.558977187801326.302098647
#Sta/Elev= 26
9885.4891918.6789887.6781915.9679898.6361905.3779909.5951896.5729920.5531884.868
9931.5121878.524 9942.471874.9479953.4291870.5699960.6441869.7449964.3881870.393
9975.346 1865.289979.0391862.5199981.9661861.9369991.473 1851.999993.7871850.699
10010.231850.59510014.761851.68710017.351852.593 10030.3 1861.7610040.261865.509
 10050.81894.77610051.711897.09310056.051898.16410062.281902.35710072.291905.474
10076.861909.314
#Mann= 3 , 0 , 0
9885.489    0.12       09885.489    0.12       010076.86    0.12       0
#XS Ineff= 2 , 0
       0                               0
Bank Sta=9885.489,10076.86
Exp/Cntr=0.3,0.1

Type RM Length L Ch R = 1 ,20060.48,28.609500,28.609500,28.609500
XS GIS Cut Line= 4
637102.894786894801392.940305769637248.820006847801392.957400948
637327.963595033801338.637447447637388.416446507801324.619394943
#Sta/Elev= 30
9808.735 1888.19 9820.841875.399 9830.841869.535 9850.841851.325 9870.84 1828.03
 9880.841819.309 9890.841816.814 9910.841808.333 9920.841800.434 9930.841795.009
 9954.661790.4049962.1551788.3769968.7221785.7749974.2841784.1359986.4131778.748
9998.5421772.47510004.061774.95610010.671780.53110021.741787.721 10022.81789.804
10034.931821.15810039.41 1827.9310047.061841.55810057.871864.30810068.14 1891.39
10078.411898.38910088.671903.35310098.941912.178 10109.21922.36110112.711927.774
#Mann= 3 , 0 , 0
9808.735    0.12       09808.735    0.12       010112.71    0.12       0
#XS Ineff= 2 , 0
       0 9975.01                       0
Bank Sta=9808.735,10112.71
Exp/Cntr=0.3,0.1

Type RM Length L Ch R = 1 ,20031.87,126.241200,126.241200,126.241200
XS GIS Cut Line= 3
637247.817356169801462.272730887637280.596805453801404.796436206
637396.447461933801329.358799458
#Sta/Elev= 29
9904.9281849.4269913.3011844.3249919.4271837.2719924.8131831.8699936.3251824.231
9939.6121822.8779947.8371817.5579959.7981813.4919971.0951808.6289976.3491807.623
9988.2821785.9399989.0481784.23110000.221765.69510007.371778.98710012.151793.481
10024.081816.758 10025.71820.73710036.021836.47910044.031851.00810047.951861.812
10059.881882.45910062.35  1883.810071.811890.67710080.681892.55410083.751894.183
10095.681907.828   100991912.30410107.611925.01510109.341928.398
#Mann= 3 , 0 , 0
9904.928    0.12       09904.928    0.12       010109.34    0.12       0
#XS Ineff= 2 , 0
       09971.069                       0
Bank Sta=9904.928,10109.34
Exp/Cntr=0.3,0.1

Type RM Length L Ch R = 1 ,19905.63,160.144000,160.144000,160.144000
XS GIS Cut Line= 3
637233.260995239801543.960367665637494.372106344801447.432589874
   637611.038773801473.127034307
#Sta/Elev= 30
9842.0821898.0769843.9361898.0989854.5971895.1799865.2591883.078 9875.921867.406
9886.582 1847.659897.2431824.6879907.904 1809.379918.5661787.6459929.2271771.051
9939.8891747.5799954.4421744.6979982.5351731.71910012.121731.27110035.841731.434
 10046.51732.62610057.161736.648 10069.81744.61510078.491750.96410089.151759.654
10131.351796.48510151.83 1812.5510162.07 1823.2710172.311835.50210182.541846.617
10192.781858.96310203.021870.125 10223.51886.62110233.741893.75810239.931897.252
#Mann= 3 , 0 , 0
9842.082    0.12       09842.082    0.12       010239.93    0.12       0
#XS Ineff= 2 , 0
       0                               0
Bank Sta=9842.082,10239.93
Exp/Cntr=0.3,0.1

Type RM Length L Ch R = 1 ,19745.49,249.641300,249.641300,249.641300
XS GIS Cut Line= 6
637151.572581871 801629.19079694637237.868752976801632.187468712
637356.083206587801645.968595015637465.736879685801648.988707516
 637546.65343274801668.033850397637643.660241616801703.998619958
#Sta/Elev= 30
9749.0571877.3219782.4871859.6229812.5221838.166 9842.611812.7069852.6781806.999
9872.8131793.1689892.9481782.5819903.0161771.7749913.0841749.2759923.1521736.184
9933.2191728.9399943.2871725.7339953.3551725.3279973.3621719.89310003.371717.141
10013.371718.08810033.411727.70510043.451733.91110063.531749.74810083.881761.839
10094.061769.31810104.291782.46810114.651804.27710125.021819.42310145.741831.136
10168.931848.383   101881858.18210209.371871.85610230.881880.95110250.94 1894.53
#Mann= 3 , 0 , 0
9749.057    0.12       09749.057    0.12       010250.94    0.12       0
#XS Ineff= 2 , 0
       0                               0
Bank Sta=9749.057,10250.94
Exp/Cntr=0.3,0.1

Type RM Length L Ch R = 1 ,19495.85,111.573500,111.573500,111.573500
XS GIS Cut Line= 6
637010.809477839 801802.25696353637135.524541736801804.631338973
637251.376424208801826.040498306637306.796198624801843.861047492
637414.538089842801894.575498599637490.333212273801925.471199314
#Sta/Elev= 30
9749.0531846.8299763.245 1836.889793.2491825.079 9803.251824.3769820.4831827.085
9833.279 1826.77  9843.31824.9649853.322 1821.289863.343 1814.799883.4661798.671
9893.5711785.0399903.677 1775.359923.8891759.728 9934.091743.5949944.321 1723.54
9964.784 1688.919975.016  1685.5 9995.541685.49810005.961687.44910026.781700.447
10070.151732.505 10081.21743.29110099.661770.78610123.141801.51310158.571843.745
 10180.41871.54810196.721888.907 10212.81902.688 10234.41911.25910250.961921.357
#Mann= 3 , 0 , 0
9749.053    0.12       09749.053    0.12       010250.96    0.12       0
#XS Ineff= 2 , 0
       0                               0
Bank Sta=9749.053,10250.96
Exp/Cntr=0.3,0.1

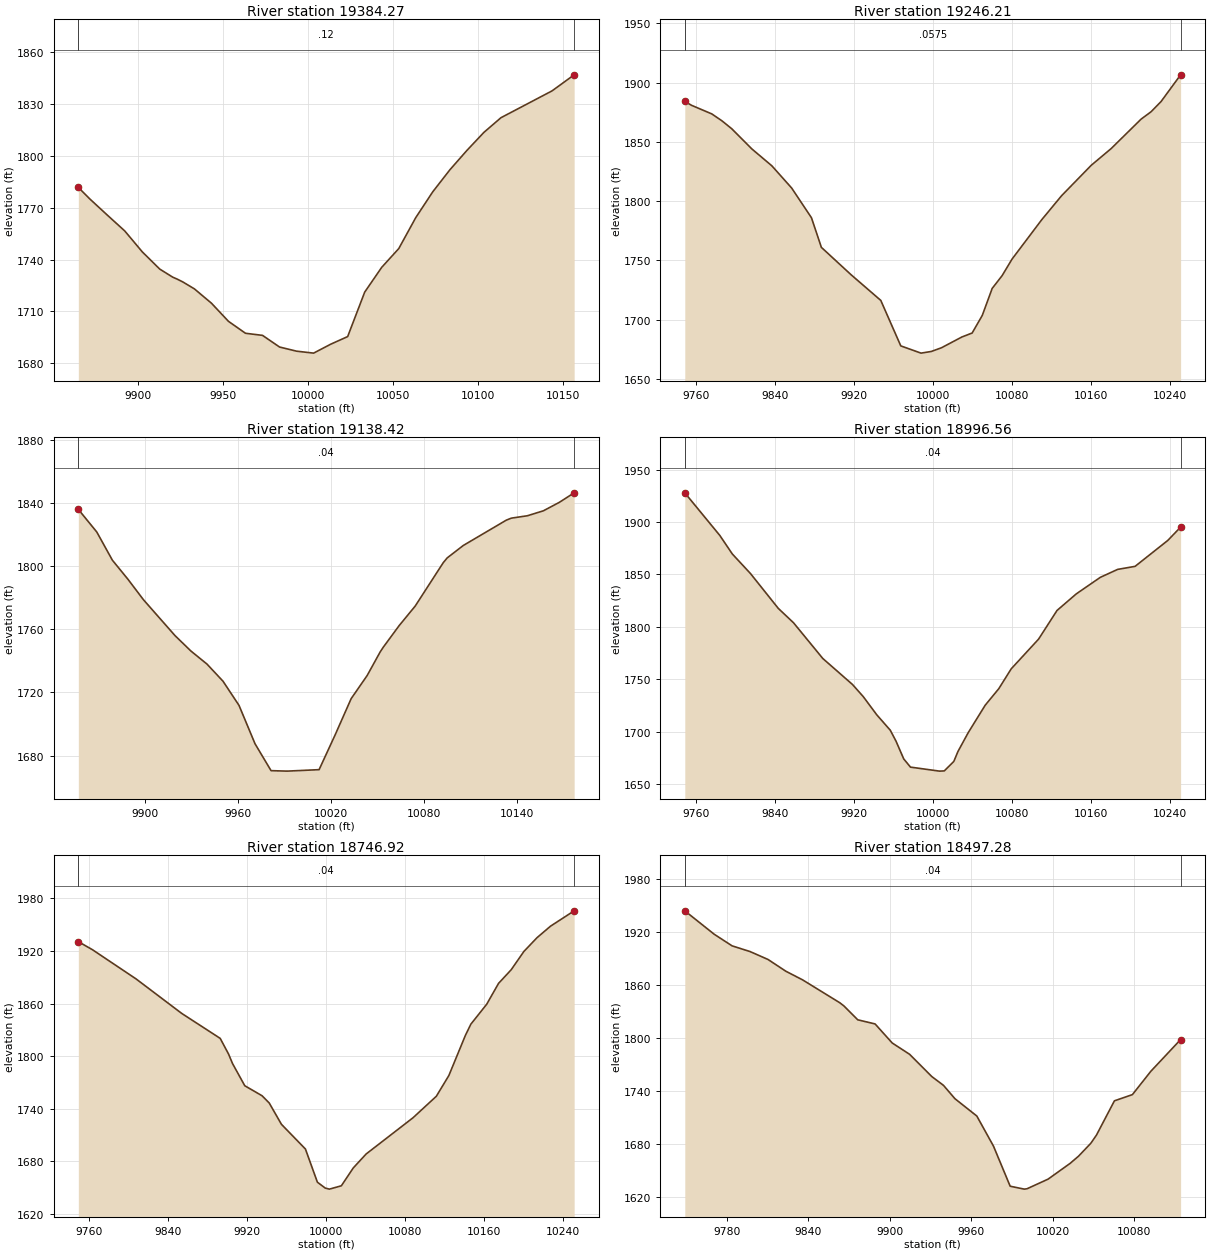
Type RM Length L Ch R = 1 ,19384.27,138.067700,138.067700,138.067700
XS GIS Cut Line= 3
637128.399884135801922.432589859637188.122106373801936.321478769
637417.983217448 801945.34925653
#Sta/Elev= 30
9865.2251781.7569872.0021775.0499882.2681765.7099892.5351756.5129902.8021744.431
9913.069 1734.459920.7071729.7679923.3361728.6319926.5411727.0549933.425 1722.99
9943.4321714.706 9953.441704.1959963.4481697.2789973.4551696.0599983.4631689.308
9993.4711686.90710003.481685.77410013.491690.92410023.491695.351 10033.51721.113
10043.511735.47610053.521746.32810063.521764.28510073.531779.26210083.541791.936
10093.551803.16710103.561813.63610113.561822.12410143.591837.66610156.581846.964
#Mann= 3 , 0 , 0
9865.225    0.12       09865.225    0.12       010156.58    0.12       0
#XS Ineff= 2 , 0
       0                               0
Bank Sta=9865.225,10156.58
Exp/Cntr=0.3,0.1

Type RM Length L Ch R = 1 ,19246.21,107.784200,107.784200,107.784200
XS GIS Cut Line= 6
637017.960104367802080.917600926637173.032302162802062.869336388
   637226.386897 802066.57321809637310.461185458802087.447453534
637361.053559457802093.312308094637514.638843853802079.749481967
#Sta/Elev= 30
9749.0811884.0929756.2081880.7279776.4551873.5739786.5781867.8149796.7011860.994
9816.9481844.0329837.1951829.7869857.2391811.0379877.2791785.9669887.2991760.984
9917.3391737.8939947.4381716.2119967.6791677.826 9988.171671.7179998.5591673.119
10008.921676.26610029.581685.35510039.911688.69510050.121703.47710060.191726.323
10070.261737.13710080.331751.12510110.431784.39110130.441804.57110160.511830.281
10180.621844.345 10210.91869.17810220.991875.39710231.081883.999 10250.91906.569
#Mann= 3 , 0 , 0
9749.081  0.0575       09749.081  0.0575       0 10250.9  0.0575       0
#XS Ineff= 2 , 0
       0                               0
Bank Sta=9749.081,10250.9
Exp/Cntr=0.3,0.1

Type RM Length L Ch R = 1 ,19138.42,141.857100,141.857100,141.857100
XS GIS Cut Line= 3
637113.122106373802196.043700978   637167.288773802199.515923217
637424.233217448802134.238145441
#Sta/Elev= 30
 9857.371835.8239869.2721821.4839879.2931803.6929889.3131791.6299899.3341778.642
9919.6041756.0139929.9221746.1899940.2391737.9579950.5571727.1239960.875 1711.82
9971.1921687.545 9981.511670.5439991.8281670.24210012.461671.17110022.781693.154
 10033.11716.06710043.421730.72410051.821745.67910053.731748.53210064.051762.323
10074.371774.65910092.441802.117   100951805.13610105.321812.96510133.051829.005
10136.271830.26610146.59 1831.7710156.911834.89910167.231840.27810176.751846.284
#Mann= 3 , 0 , 0
 9857.37    0.04       0 9857.37    0.04       010176.75    0.04       0
#XS Ineff= 2 , 0
       0                               0
Bank Sta=9857.37,10176.75
Exp/Cntr=0.3,0.1

Type RM Length L Ch R = 1 ,18996.56,249.641200,249.641200,249.641200
XS GIS Cut Line= 6
637147.081258621802454.121976446637199.516570631802413.156564968
637247.035422407802372.890281573637422.094702385802210.547472254
637479.570905281802169.646802606637535.307446936802138.682365934
#Sta/Elev= 30
9749.0171927.8519784.4461887.2029797.1361869.4729815.5581850.7459843.6431817.565
9859.111 1803.789888.7211769.7119918.7871744.8739929.6981733.2839943.357 1715.94
9957.0161701.2469962.8281690.8299970.6751673.7959977.5091665.99210006.851662.182
10011.721662.39910021.371671.46310025.51 1680.8510035.881698.826 10053.11725.064
 10066.91740.89810079.441759.797 10107.21788.232 10125.81815.52210145.35 1831.39
10169.741847.213 10187.21854.75710204.851857.65110237.951882.37910250.961895.113
#Mann= 3 , 0 , 0
9749.017    0.04       09749.017    0.04       010250.96    0.04       0
#XS Ineff= 2 , 0
       0                               0
Bank Sta=9749.017,10250.96
Exp/Cntr=0.3,0.1

Type RM Length L Ch R = 1 ,18746.92,249.641300,249.641300,249.641300
XS GIS Cut Line= 6
637385.318683224802622.978831741637436.560179541802567.608148468
637481.703054884802512.809431073637621.555914554802311.165441539
637662.167496445802260.521787484637692.943086261802227.482626649
#Sta/Elev= 30
9749.027 1930.559763.2811921.403 9807.451888.1029853.7611848.702 9892.631820.309
 9901.061802.5349905.1371791.5749917.5171766.3169934.9841754.9219942.2781746.628
9954.6531722.3069978.9191694.1659991.0521656.313    99991649.61810003.211648.439
10015.311652.256 10027.41672.66110040.341688.44610087.87 1729.8410111.451754.306
10124.161778.02310140.891823.78310146.391836.49210162.381859.13510174.431882.985
10187.25 1898.5710200.061919.37510213.351935.05710227.021948.18910250.961965.699
#Mann= 3 , 0 , 0
9749.027    0.04       09749.027    0.04       010250.96    0.04       0
#XS Ineff= 2 , 0
       0                               0
Bank Sta=9749.027,10250.96
Exp/Cntr=0.3,0.1

Type RM Length L Ch R = 1 ,18497.28,249.641200,249.641200,249.641200
XS GIS Cut Line= 6
637528.644699757 802751.66354476637627.384178411802666.332688801
637671.033470757802632.749877429637745.368075383802579.294338138
637786.013436767802544.086185003637808.974864852802518.776145724
#Sta/Elev= 30
9749.0251944.5119770.6421918.0299783.8591904.8279797.0751898.3769810.2921889.415
9823.5091876.0149835.6851866.374 9863.161840.3719866.2721836.6579876.3761821.048
9889.1371816.3949901.7541794.7949914.5111782.0459930.9111756.7599939.4731746.846
9947.9451731.6779964.0411712.0769976.3241677.9579988.6081632.542    99991629.255
   100011629.65210016.531640.58210032.721658.40210038.91 1666.5310047.991681.189
10052.141690.45810065.371729.286 10078.61736.317 10092.21762.77710114.111798.685
#Mann= 3 , 0 , 0
9749.025    0.04       09749.025    0.04       010114.11    0.04       0
#XS Ineff= 2 , 0
       0                               0
Bank Sta=9749.025,10114.11
Exp/Cntr=0.3,0.1

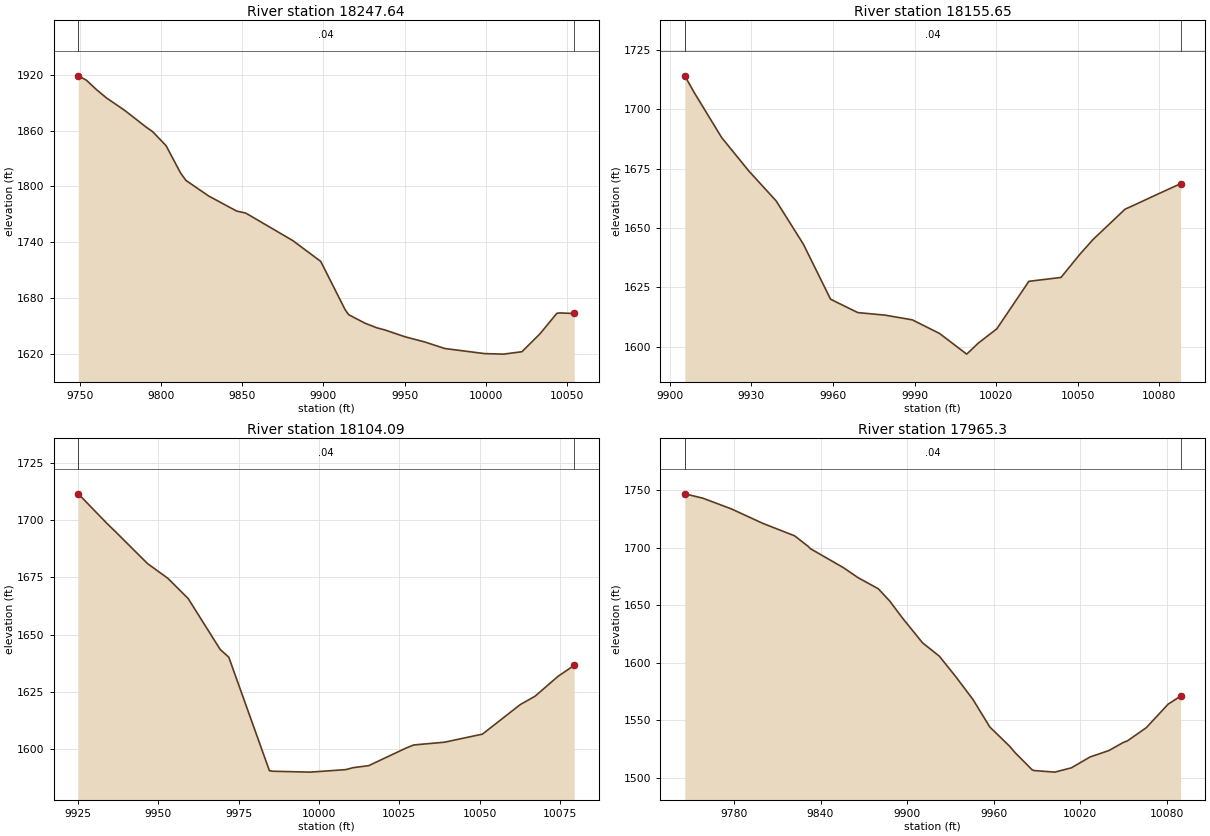
Type RM Length L Ch R = 1 ,18247.64,91.994500,91.994500,91.994500
XS GIS Cut Line= 6
637748.488626046  802979.0735494637894.209052762802773.498441878
637902.396787941802760.193730583637910.054591587802744.071960488
637913.025587348802733.402569382637913.697026222802724.428982503
#Sta/Elev= 30
9749.0131919.198 9754.011914.4529760.2551904.2599766.277 1895.48 9777.521882.075
9790.8121863.9549794.7841859.0919803.0791843.9949812.0491814.4239815.3471806.504
9829.3141789.7619846.5791773.5229852.1481771.3729881.1081741.7969898.3731719.324
9913.4851667.0739915.6381661.8679925.7521652.6649932.9031647.797 9938.021645.396
9950.287 1638.119962.5541632.4849974.8211625.4699999.203    162010010.981619.417
10022.371621.99910033.441641.22310043.891663.40310045.551663.79310054.541663.196
#Mann= 3 , 0 , 0
9749.013    0.04       09749.013    0.04       010054.54    0.04       0
#XS Ineff= 2 , 0
       0                               0
Bank Sta=9749.013,10054.54
Exp/Cntr=0.3,0.1

Type RM Length L Ch R = 1 ,18155.65,51.556800,51.556800,51.556800
XS GIS Cut Line= 3
637980.483217448802908.543700993637974.927661926802800.904812083
637935.344328552802737.710367665
#Sta/Elev= 24
 9905.481714.0199909.0291706.8259919.0421688.0349929.055 1673.939939.0691661.394
9949.0821643.1899959.0951619.9959969.1091614.3759979.1221613.3029989.1351611.325
9999.1491605.60210009.161596.89210011.861599.80910013.261601.38810020.23 1607.54
10031.961627.43610032.031627.53510043.831629.162 10050.81638.94710055.631645.142
10067.431657.93410069.641659.03910079.23 1664.1310087.831668.631
#Mann= 3 , 0 , 0
 9905.48    0.04       0 9905.48    0.04       010087.83    0.04       0
#XS Ineff= 2 , 0
       0                               0
Bank Sta=9905.48,10087.83
Exp/Cntr=0.3,0.1

Type RM Length L Ch R = 1 ,18104.09,138.785900,138.785900,138.785900
XS GIS Cut Line= 3
638072.039003372802872.026369527638021.066503823802806.218590274
637960.774405509802768.559803292
#Sta/Elev= 24
9925.1321711.5289934.0191698.6339936.6261695.0939946.6681681.0729952.9571674.691
9959.3171665.8189969.287 1643.579971.966 1640.199984.6151590.6339985.6171590.401
9997.2641590.01210001.951590.46910008.371591.10910010.671591.95310015.521592.841
10027.311600.63710029.551601.879 10039.11603.07310048.421605.868 10050.91606.588
10062.691619.502 10067.31623.16810074.481631.88410079.461636.622
#Mann= 3 , 0 , 0
9925.132    0.04       09925.132    0.04       010079.46    0.04       0
#XS Ineff= 2 , 0
       0                               0
Bank Sta=9925.132,10079.46
Exp/Cntr=0.3,0.1

Type RM Length L Ch R = 1 , 17965.3,216.945300,216.945300,216.945300
XS GIS Cut Line= 4
638120.193508953802914.351662233638057.987466872 802776.58875297
638023.920856088802719.811068326637926.650559127802639.500720561
#Sta/Elev= 30
9745.9781746.9839758.5971743.1529778.1831733.8929800.1271721.2249822.072 1710.41
9831.4951701.1979833.0441699.2149855.7951682.761 9865.961674.0469880.0941664.294
9887.9051653.7059897.1341638.3219910.648 1617.339922.377  1605.69933.9721587.382
9945.6341567.9259957.2961543.9989970.9041527.3989974.9161521.509 9986.611506.738
9987.8841506.09510002.32 1504.7110013.821508.46110026.791517.93310039.761523.473
10049.441530.30110052.721531.98610065.691543.38310080.851563.88610089.491570.858
#Mann= 3 , 0 , 0
9745.978    0.04       09745.978    0.04       010089.49    0.04       0
#XS Ineff= 2 , 0
       0                               0
Bank Sta=9745.978,10089.49
Exp/Cntr=0.3,0.1