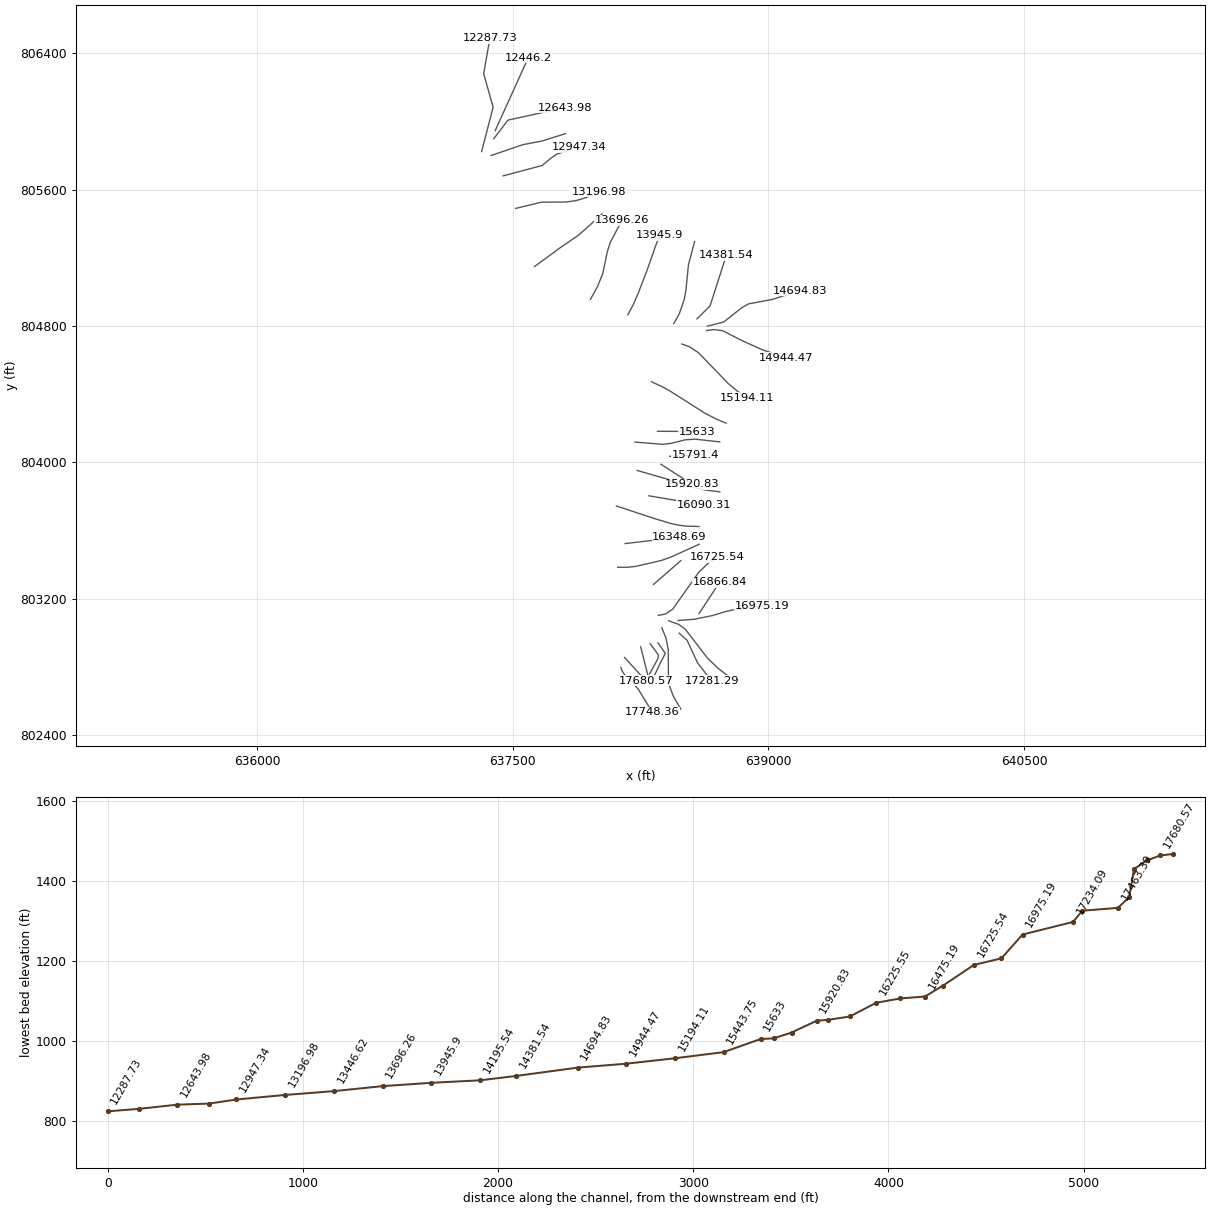
HEC-RAS study 12582_ras.prj: 12582

--- 12582_ras.g01 (geometry) --- (continued)

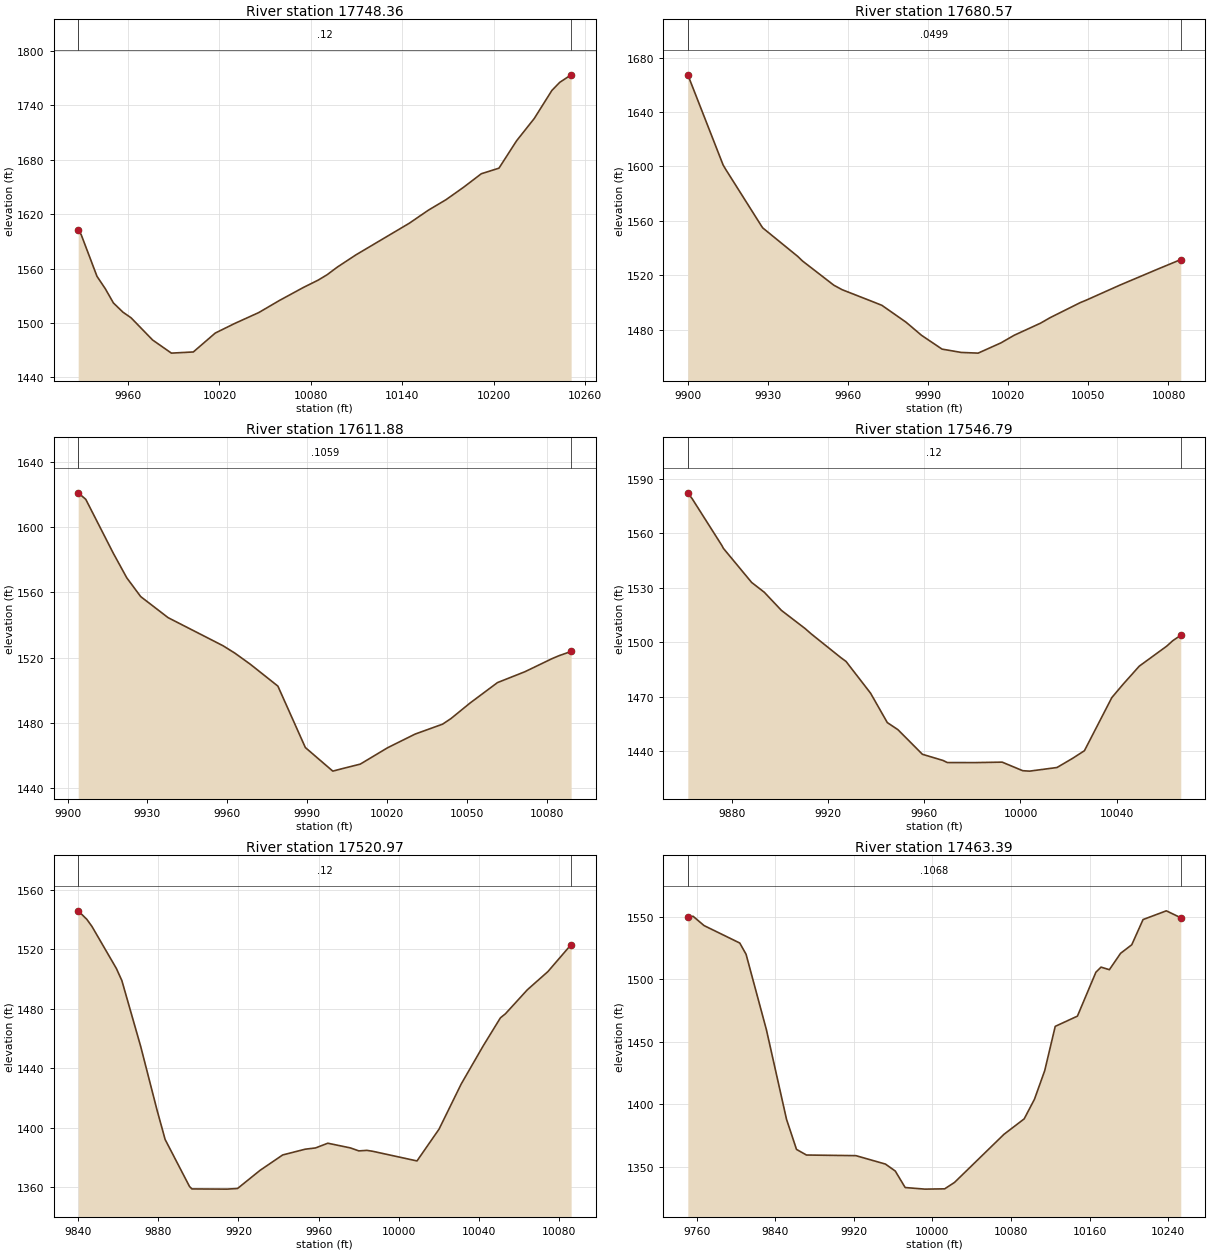
Type RM Length L Ch R = 1 ,17748.36,67.786600,67.786600,67.786600
XS GIS Cut Line= 6
638134.931614841802796.888021766638139.709847251802779.721963385
638156.404031265802753.686521557638205.110529627802706.437138869
638236.379964449802668.886826056 638318.78851903802534.081228608
#Sta/Elev= 30
9927.2931602.3039929.2531597.5219939.633 1551.519945.1121537.7779950.4241522.149
9956.6611512.0279962.0211505.7699976.1451481.335 9988.491466.84310002.891468.137
10017.291488.97210029.961499.45310045.881511.58410059.461524.92410075.09 1539.18
10084.921547.40110090.721553.26510097.541561.81710109.541575.05810144.671610.026
10157.211624.44210168.791635.99110180.381649.77510191.961664.60110203.541670.733
10215.121700.941 10226.71725.47310238.291756.42810243.421765.30710250.931773.639
#Mann= 3 , 0 , 0
9927.293    0.12       09927.293    0.12       010250.93    0.12       0
#XS Ineff= 2 , 0
       0                               0
Bank Sta=9927.293,10250.93
Exp/Cntr=0.3,0.1

Type RM Length L Ch R = 1 ,17680.57,68.691800,68.691800,68.691800
XS GIS Cut Line= 2
638156.108695537802855.490662023638280.315382421802718.813424245
#Sta/Elev= 28
9899.9181667.3369900.581 1664.069913.1381601.1469914.0931597.9649927.6051556.003
9928.0071554.8719941.1181533.9399942.8761530.611 9954.631512.8059957.7451509.501
9968.143 1501.529972.6141498.0519981.6551485.6699987.4831475.9919995.1671465.865
10002.351463.42710008.681462.91710017.221470.43210022.191476.03910032.09 1484.95
 10035.71489.01210046.961500.02110049.221501.85210061.831512.90310062.731513.649
10076.241524.848 10076.71525.212 10084.61531.638
#Mann= 3 , 0 , 0
9899.918  0.0499       09899.918  0.0499       0 10084.6  0.0499       0
#XS Ineff= 2 , 0
       0                               0
Bank Sta=9899.918,10084.6
Exp/Cntr=0.3,0.1

Type RM Length L Ch R = 1 ,17611.88,65.090600,65.090600,65.090600
XS GIS Cut Line= 2
638250.507742614802917.766325802638296.100076705802738.160161316
#Sta/Elev= 25
9903.9551621.0169906.8091617.0299917.1261584.1219922.213 1568.999927.4431557.499
 9937.761544.5799948.0781535.9899958.3951527.3929962.8561522.8589968.7121515.996
9979.0291502.6579989.3461465.0589999.6631450.612 10003.51452.24610009.981454.894
 10020.31464.95810030.611473.29910040.931479.36710044.141482.85410051.251492.292
10061.571504.82310071.88 1511.47 10082.21519.57610084.791521.34410089.261523.901
#Mann= 3 , 0 , 0
9903.955  0.1059       09903.955  0.1059       010089.26  0.1059       0
#XS Ineff= 2 , 0
       0                               0
Bank Sta=9903.955,10089.26
Exp/Cntr=0.3,0.1

Type RM Length L Ch R = 1 ,17546.79,25.814400,25.814400,25.814400
XS GIS Cut Line= 4
 638306.29674539802936.466950402638355.102919519802869.358460963
638350.928707242802846.560840145638303.406906128802759.865662426
#Sta/Elev= 30
9861.6451582.3859863.4591579.1479875.8231553.3499876.4421551.7989888.1881533.025
9893.4441527.6259900.5531517.6549910.4451507.6059912.9181504.7369925.2831491.611
9927.4471489.5129937.648 1472.039944.6241455.8089949.0551451.8949959.2211438.349
9967.8011434.9489969.5811433.8029980.9841433.7719992.3881434.02810000.94 1429.31
10003.791429.077 10015.21431.07210021.74 1436.17 10026.61440.321   100381469.593
10042.551476.73210049.411486.90410060.811497.90710063.351500.92810066.671503.914
#Mann= 3 , 0 , 0
9861.645    0.12       09861.645    0.12       010066.67    0.12       0
#XS Ineff= 2 , 0
       09953.712                       0
Bank Sta=9861.645,10066.67
Exp/Cntr=0.3,0.1

Type RM Length L Ch R = 1 ,17520.97,57.587200,57.587200,57.587200
XS GIS Cut Line= 4
638352.534173489802940.641162634638395.239575893802879.312351733
638363.130250782802817.662447572638320.103755176802725.187591359
#Sta/Elev= 30
9839.9391545.7069844.2541539.9929846.8131535.2269858.9991507.0079861.754 1498.85
9871.1841454.4939879.2531412.209 9883.371392.0789895.5551360.4889896.753 1358.86
9914.2521358.7279919.5341359.1519930.8091371.3659942.0841381.6869953.3591385.563
9958.4861386.4019964.6341389.5729975.9091386.4269980.1341384.4129984.1821384.769
9987.1191384.13410009.181377.66710020.211399.06610031.241429.30710042.271455.019
10050.871473.849 10053.31476.45710064.32 1492.6810074.571504.88210086.181523.017
#Mann= 3 , 0 , 0
9839.939    0.12       09839.939    0.12       010086.18    0.12       0
#XS Ineff= 2 , 0
       09947.919                       0
Bank Sta=9839.939,10086.18
Exp/Cntr=0.3,0.1

Type RM Length L Ch R = 1 ,17463.39,182.101700,182.101700,182.101700
XS GIS Cut Line= 6
638374.722771992803029.795007248638398.535697526802970.812086854
 638412.31256627802901.633934524638413.573323655802703.450978181
 638442.49532462802627.033870103638486.254922093802552.599327324
#Sta/Elev= 30
9751.0651549.9399756.4321550.5539767.6261543.0879803.9551529.134 9810.381520.113
9831.0661459.7779851.5651388.0389861.7021364.0189871.8391359.5219922.1631359.023
9952.1961352.2899962.254 1346.719972.3131333.5129992.4291332.23710012.53 1332.47
10022.561337.61510072.871376.08210093.451388.45210103.911404.11710114.361427.048
10125.061462.45710147.641470.63710166.451505.77510171.671509.84910180.17  1507.8
10191.571520.89710202.97 1527.7610214.451547.91410238.151554.89910252.841549.367
#Mann= 3 , 0 , 0
9751.065  0.1068       09751.065  0.1068       010252.84  0.1068       0
#XS Ineff= 2 , 0
       09938.425                       0
Bank Sta=9751.065,10252.84
Exp/Cntr=0.3,0.1

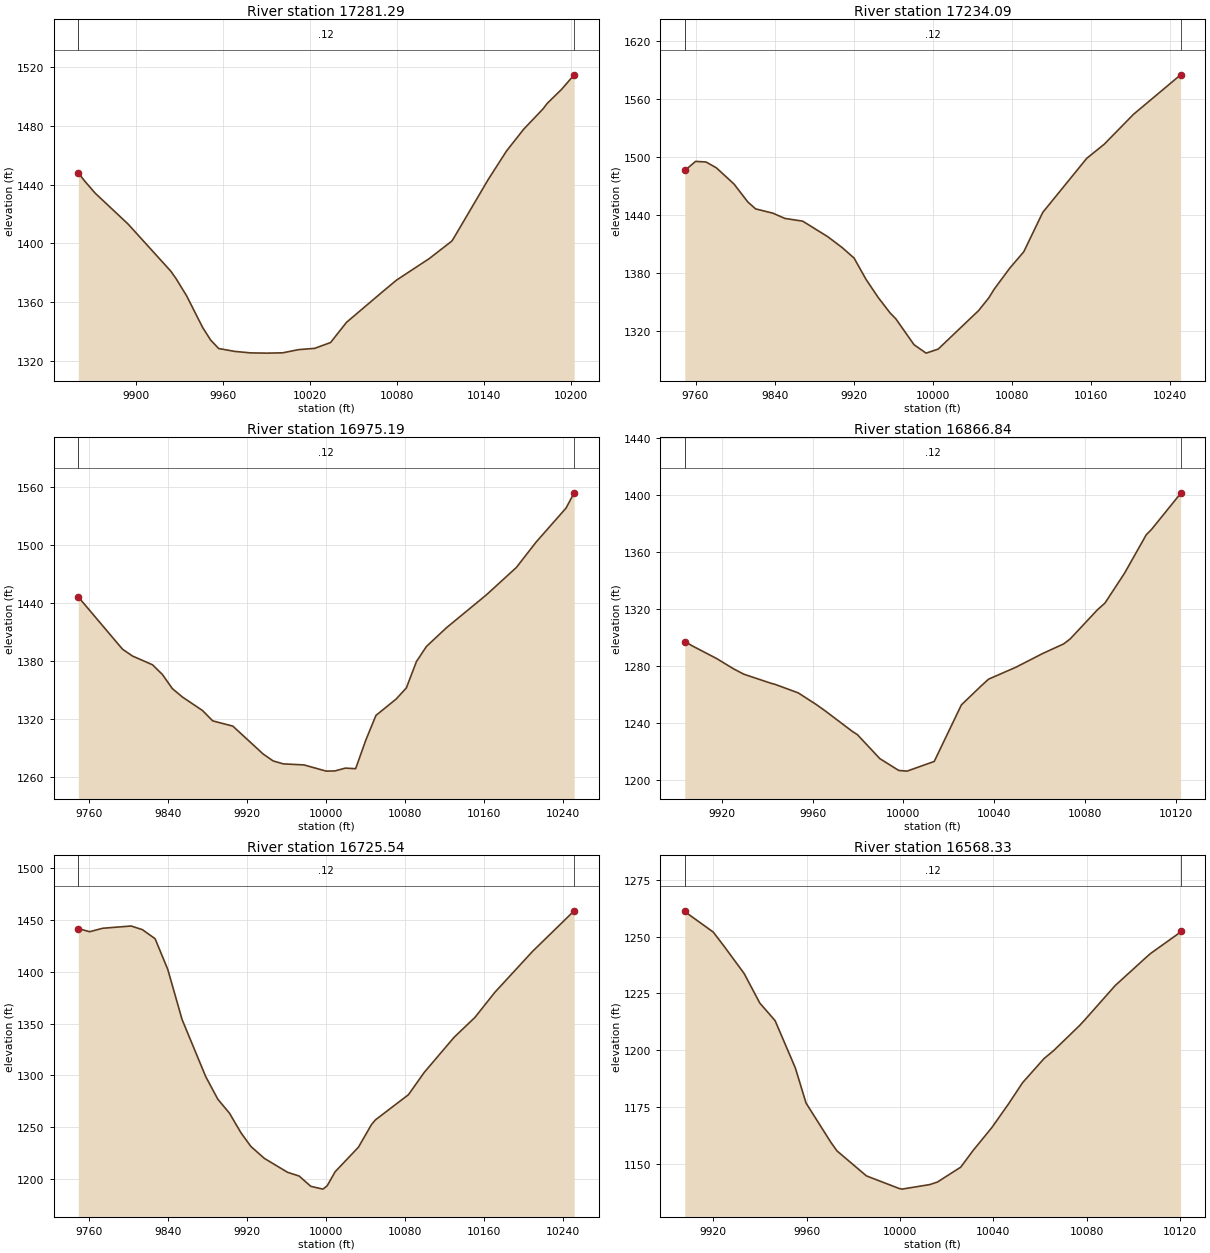
Type RM Length L Ch R = 1 ,17281.29,47.199800,47.199800,47.199800
XS GIS Cut Line= 4
638476.397034138802997.898306876638522.680161148802956.450730473
638584.851525754802823.127692968638666.365092725802718.127166063
#Sta/Elev= 30
9859.9371447.9999864.2811442.5299871.4851434.2989894.2611413.1769923.6671381.168
9927.555 1375.73  9934.71364.1989945.7341342.6919951.2161334.1839956.7681328.358
9967.8021326.3979978.8361325.376 9989.871325.214 10000.91325.41410011.941327.594
10022.971328.454   10034 1332.4410045.041346.23210069.411366.64610079.461374.931
10102.031389.58810117.441401.37810118.341402.49910142.761443.47410155.421462.966
10167.26 1477.7910180.741491.79210183.57 1495.46 10193.41504.941 10202.11514.867
#Mann= 3 , 0 , 0
9859.937    0.12       09859.937    0.12       0 10202.1    0.12       0
#XS Ineff= 2 , 0
       0                               0
Bank Sta=9859.937,10202.1
Exp/Cntr=0.3,0.1

Type RM Length L Ch R = 1 ,17234.09,258.899400,258.899400,258.899400
XS GIS Cut Line= 6
638414.589953801803070.743123766638474.431237892803049.073846656
 638511.81686724 803021.94887256638645.256338079802848.449145827
638705.296114494802791.566196398638776.451415474802736.712995529
#Sta/Elev= 30
9749.1171486.4199760.0461495.8479770.545 1495.229781.0441489.2059798.942 1472.37
9812.8721453.8719820.7641446.6689838.3191442.2099850.4141436.7939868.4981433.935
9893.8521417.8349908.3071406.6689920.4541395.7359932.6011373.5859944.7481355.095
9956.8951338.9429962.6111332.9759981.1891305.9569993.3361297.31510005.591301.486
10046.471341.364 10056.91354.655 10062.21363.46510077.931385.17510092.17  1402.2
10111.371442.95310155.93    149910173.571513.55810203.271544.58910250.951585.461
#Mann= 3 , 0 , 0
9749.117    0.12       09749.117    0.12       010250.95    0.12       0
#XS Ineff= 2 , 0
       0                               0
Bank Sta=9749.117,10250.95
Exp/Cntr=0.3,0.1

Type RM Length L Ch R = 1 ,16975.19,108.342900,108.342900,108.342900
XS GIS Cut Line= 6
638470.199418705803072.360300548 638565.87747347803079.803668267
638673.004895775 803101.54112592 638746.89095539803124.192505102
638801.133720091803136.643461687 638963.17190588803158.521503915
#Sta/Elev= 30
9749.0761446.3749793.8951392.1529803.9671385.1389824.1151376.1189834.1891366.034
9844.2631351.3649854.4551342.6719874.8631328.6129885.0671317.9719905.4741312.504
9936.0861283.648 9946.291276.4029956.5471273.3559977.4931272.282 9999.98 1265.84
10008.861266.05710019.311268.95910029.771268.39110040.061297.98310050.321323.591
10070.841340.644 10081.11352.10110091.311379.41810101.441395.093 10121.71414.488
10162.211448.66810192.46 1476.9710212.571503.45110242.741538.53810250.961554.362
#Mann= 3 , 0 , 0
9749.076    0.12       09749.076    0.12       010250.96    0.12       0
#XS Ineff= 2 , 0
       0                               0
Bank Sta=9749.076,10250.96
Exp/Cntr=0.3,0.1

Type RM Length L Ch R = 1 ,16866.84,141.298400,141.298400,141.298400
XS GIS Cut Line= 2
 638593.14104104803113.260727912638713.339012653 803295.63006416
#Sta/Elev= 30
9903.6931297.2519907.071 1294.199917.7531285.3459925.242 1278.119929.7291274.389
9941.7061268.0359943.414 1267.329953.683 1261.329961.5851253.1969965.6591248.583
9977.6361234.1889979.7571232.0369989.6121215.2669997.9281206.99510001.591206.515
10013.571213.29610025.541252.93210034.271266.25410037.521270.945 10049.5 1279.25
10061.471289.00710070.61 1295.6510073.451299.10310085.431319.47610088.791324.255
 10097.41345.14510106.961372.04810109.38 1375.9910121.361399.56910122.111401.456
#Mann= 3 , 0 , 0
9903.693    0.12       09903.693    0.12       010122.11    0.12       0
#XS Ineff= 2 , 0
       0                               0
Bank Sta=9903.693,10122.11
Exp/Cntr=0.3,0.1

Type RM Length L Ch R = 1 ,16725.54,157.219500,157.219500,157.219500
XS GIS Cut Line= 6
638353.624881463803101.971137771638397.634583114803110.915586974
 638439.27395128803139.778832201638592.349367911803356.779831924
 638647.87564169803409.333334978638700.337536551803444.662937086
#Sta/Elev= 30
9749.1531441.7879760.5971438.7429773.8011442.0699802.5971444.2499814.016 1440.71
9826.8531431.966 9839.69  1402.39854.1031354.0129878.0511298.7929890.3331276.868
 9902.091263.4119913.8461244.307 9923.731231.287 9937.36 1219.749960.873 1206.26
 9972.63 1202.639984.4311192.6869996.7151189.988   100011193.21910009.021206.746
10032.631230.52110045.881252.43610049.84 1256.9210083.231281.21810099.351302.938
10129.481336.741 10150.61355.99510170.591380.06310208.781419.67510250.951458.916
#Mann= 3 , 0 , 0
9749.153    0.12       09749.153    0.12       010250.95    0.12       0
#XS Ineff= 2 , 0
       0                               0
Bank Sta=9749.153,10250.95
Exp/Cntr=0.3,0.1

Type RM Length L Ch R = 1 ,16568.33,93.132600,93.132600,93.132600
XS GIS Cut Line= 2
638325.804173142803283.886584193638486.068135291803423.426758125
#Sta/Elev= 30
9907.7661261.3499909.4611259.7579919.9591251.996 9924.691245.6339933.2181233.706
9939.919 1220.719946.4781212.9569955.1471192.1289959.7371176.6639970.3761159.358
9972.9961155.5849985.6041144.5839999.515 1139.0710000.831138.74310012.771140.752
10016.061141.87510026.031148.42710031.291155.71710039.291165.77110046.52  1176.3
10052.55 1185.6610061.751196.28710065.811199.73810076.98 1210.8410079.07 1213.16
 10092.21228.40110105.591240.94710107.431242.58310118.851250.96710120.271252.267
#Mann= 3 , 0 , 0
9907.766    0.12       09907.766    0.12       010120.27    0.12       0
#XS Ineff= 2 , 0
       0                               0
Bank Sta=9907.766,10120.27
Exp/Cntr=0.3,0.1

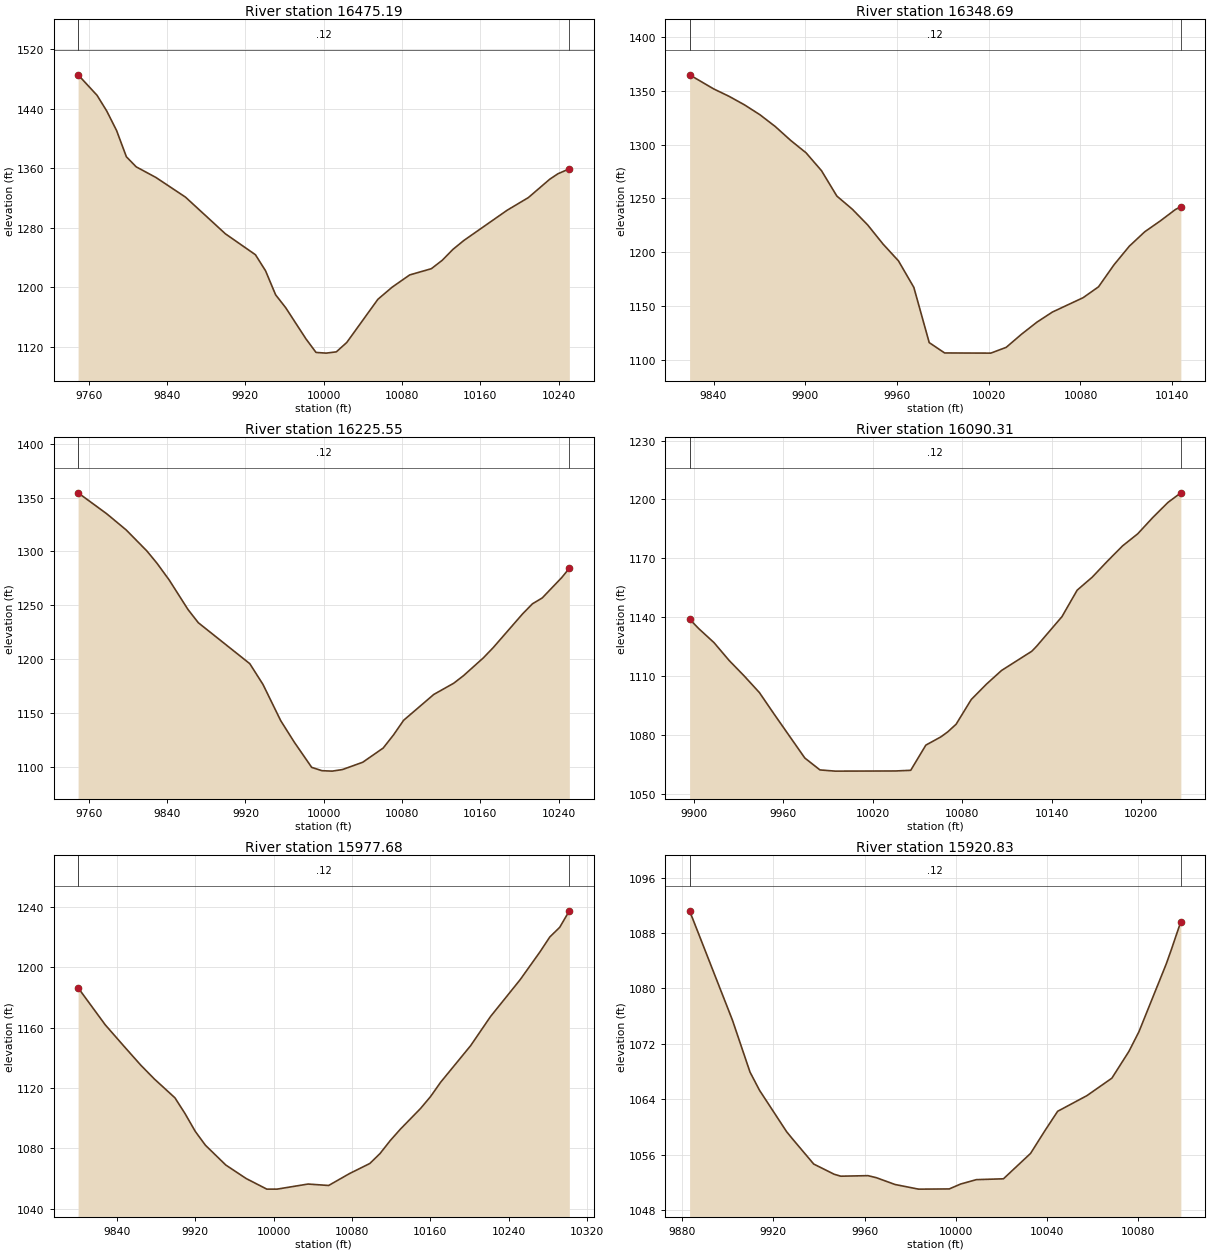
Type RM Length L Ch R = 1 ,16475.19,126.498000,126.498000,126.498000
XS GIS Cut Line= 6
638115.655586647803384.637312158638175.907902048803384.891431714
638222.767962405803390.241964708 638370.67449193 803424.15482676
638431.350186216803445.930601281638593.552314322803519.618364233
#Sta/Elev= 30
9749.0731485.2689768.4171457.7669778.4171436.4559788.4171410.3249798.4171375.142
9808.4181361.6269828.5421347.3719858.7641320.943 9899.521271.673 9930.251243.527
9940.5631221.9829950.8771189.659 9961.191172.2789981.8171130.535 9992.131112.252
10002.431111.31510012.881113.02510023.511125.58110055.381183.706   100701200.037
10087.841216.39810109.961224.75910121.011235.99110132.07 1250.7910143.121262.649
10187.341303.27810209.061320.30710230.791344.86610239.121352.21110250.941359.005
#Mann= 3 , 0 , 0
9749.073    0.12       09749.073    0.12       010250.94    0.12       0
#XS Ineff= 2 , 0
       0                               0
Bank Sta=9749.073,10250.94
Exp/Cntr=0.3,0.1

Type RM Length L Ch R = 1 ,16348.69,123.143200,123.143200,123.143200
XS GIS Cut Line= 2
 638159.32307449803523.591734484638478.469412923803560.894553244
#Sta/Elev= 30
9824.3391364.6189840.1231351.5329850.1911344.6559860.2591336.7599870.3271327.628
9880.395 1316.659890.4631303.7879900.5311292.2689910.5991275.7599920.6671252.163
9930.7351240.0499940.8031225.4399950.8711207.664 9960.941192.1189971.0081167.518
9981.0761116.2769991.144 1106.6910021.35 1106.5310031.421111.88910041.481124.105
10051.551135.28810061.621144.60310081.761157.96310091.821168.03610101.891188.358
10111.961205.71510122.031219.048 10132.11229.02610142.16 1239.7710145.661242.274
#Mann= 3 , 0 , 0
9824.339    0.12       09824.339    0.12       010145.66    0.12       0
#XS Ineff= 2 , 0
       0                               0
Bank Sta=9824.339,10145.66
Exp/Cntr=0.3,0.1

Type RM Length L Ch R = 1 ,16225.55,135.245100,135.245100,135.245100
XS GIS Cut Line= 6
638108.356541173803744.181106325638340.058951955803667.752180962
638430.997839335803640.753501735638470.421880514803632.347937972
638512.114990203803626.575107586638592.726818205803623.829830389
#Sta/Elev= 30
 9749.011354.5049778.3181334.9949798.1251320.0169819.1851300.5569829.7151288.938
9842.1641273.3779861.3051246.0319871.835 1233.779924.4851195.6479937.9321176.367
9956.0751142.6749969.855 1122.819987.6651099.3339998.1631096.22410008.591095.825
10019.021097.25910039.881104.08910060.741117.28810071.171129.336 10081.61143.067
 10112.4 1167.0810132.791177.51810142.881184.62110163.071201.09510173.151210.623
10203.221242.03310213.231251.34410223.231256.78610243.231275.80910250.95 1284.36
#Mann= 3 , 0 , 0
 9749.01    0.12       0 9749.01    0.12       010250.95    0.12       0
#XS Ineff= 2 , 0
       0                               0
Bank Sta=9749.01,10250.95
Exp/Cntr=0.3,0.1

Type RM Length L Ch R = 1 ,16090.31,112.628200,112.628200,112.628200
XS GIS Cut Line= 2
638298.863248467803804.053668246638623.535930395803748.790233016
#Sta/Elev= 30
9897.2681138.9579903.4931134.0949913.6361127.023 9923.781117.9359933.9241110.005
9944.0681101.5729954.2121090.3049974.4991068.2419984.6431062.1729994.7871061.554
10035.361061.63310045.511061.96910055.651074.79710065.791079.03810070.411081.601
10075.94 1085.4510086.081098.02410096.231105.83310106.371112.81910126.661122.617
10130.011125.25710146.941140.29710157.09 1153.7510167.231160.40110177.38 1168.53
10187.521176.30110197.661182.44310207.811190.77310217.95 1198.4410226.611203.345
#Mann= 3 , 0 , 0
9897.268    0.12       09897.268    0.12       010226.61    0.12       0
#XS Ineff= 2 , 0
       0                               0
Bank Sta=9897.268,10226.61
Exp/Cntr=0.3,0.1

Type RM Length L Ch R = 1 ,15977.68,56.851000,56.851000,56.851000
XS GIS Cut Line= 6
638229.942397486803952.698374406638394.301762417803905.426022885
638502.774093346803869.306169995638551.553235641803855.119784143
638627.246390349803838.663328745 638714.79648233803827.034780562
#Sta/Elev= 30
9800.1961186.2939828.0471161.674 9847.081147.5939864.2251135.0829878.2961125.795
9899.107 1113.489909.5121102.9619919.9181091.2189930.3231082.0429951.1341068.956
9971.953 1060.029993.0061053.01710003.531053.01910035.111056.376 10056.21055.433
10077.331063.24710098.281070.00410108.691076.57410119.11 1085.1410129.521092.734
10150.111106.41610160.341114.30910170.581123.73310201.281147.99810221.631167.295
10251.891191.67210272.071210.01310282.161219.91210292.251226.28210302.131237.227
#Mann= 3 , 0 , 0
9800.196    0.12       09800.196    0.12       010302.13    0.12       0
#XS Ineff= 2 , 0
       0                               0
Bank Sta=9800.196,10302.13
Exp/Cntr=0.3,0.1

Type RM Length L Ch R = 1 ,15920.83,129.428200,129.428200,129.428200
XS GIS Cut Line= 2
638369.201466471803989.345016688638550.451466441803872.678350016
#Sta/Elev= 28
9883.2361091.1969902.0251075.446 9909.741067.9529913.9171065.325 9925.811059.354
9928.2161058.3859937.7021054.6919946.6921053.2189949.5951052.9419961.4871053.019
9965.1681052.727 9973.381051.7449983.6431051.0789985.2721051.0779997.1651051.105
10002.121051.80710009.061052.44410020.951052.56610032.841056.22510039.071059.465
10044.731062.29710057.551064.54910068.521067.07110076.021070.94410080.411073.777
10092.311083.479 10094.51085.49410098.791089.645
#Mann= 3 , 0 , 0
9883.236    0.12       09883.236    0.12       010098.79    0.12       0
#XS Ineff= 2 , 0
       0                               0
Bank Sta=9883.236,10098.79
Exp/Cntr=0.3,0.1

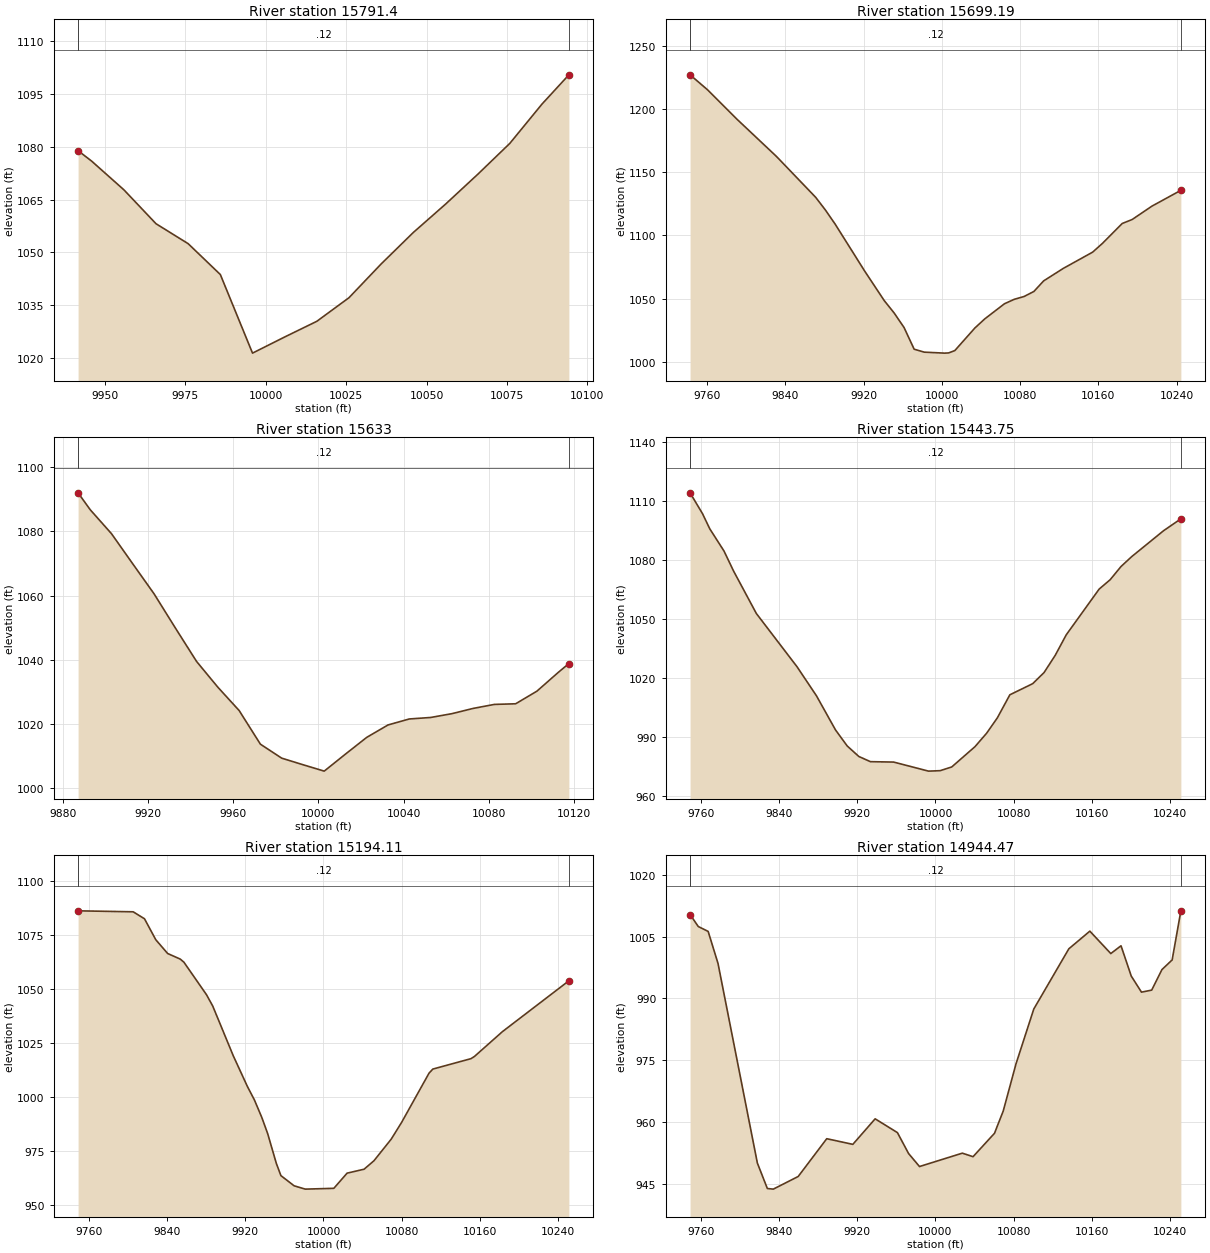
Type RM Length L Ch R = 1 , 15791.4,92.207400,92.207400,92.207400
XS GIS Cut Line= 2
638420.763966471804035.699183345638573.368133128804040.907516688
#Sta/Elev= 17
9941.5891078.8789945.8271075.8979955.8331067.7789965.8391058.1419975.8451052.479
 9985.851043.7219995.8561021.42410005.861026.00110015.871030.45710025.871037.152
10035.881046.73310045.891055.66710055.891063.687 10065.91072.147 10075.91080.941
10085.911092.09210094.28  1100.4
#Mann= 3 , 0 , 0
9941.589    0.12       09941.589    0.12       010094.28    0.12       0
#XS Ineff= 2 , 0
       0                               0
Bank Sta=9941.589,10094.28
Exp/Cntr=0.3,0.1

Type RM Length L Ch R = 1 ,15699.19,66.193000,66.193000,66.193000
XS GIS Cut Line= 6
638217.436572042804119.337810801638379.726970405804106.174551561
638432.718890797804112.186364108638510.149284524804132.243863358
638570.470366058804136.418799747638714.283338188804120.260609559
#Sta/Elev= 30
9742.5731226.9529760.3381215.1969790.664 1191.779830.8771162.4689870.9231130.205
9880.9241120.1299890.9261108.9319921.0261071.9329941.1541048.4499951.2181038.726
9961.3471027.2399971.6941010.0799982.0411007.75310002.851006.98410006.931007.147
10013.29 1009.0110033.761026.832 10043.91034.06610064.041046.01410074.06 1049.52
10084.061051.74310094.07  1055.710104.081064.08310124.121073.93110154.181086.805
10164.221093.73510184.441109.47110194.551112.57510214.771123.14810244.381135.665
#Mann= 3 , 0 , 0
9742.573    0.12       09742.573    0.12       010244.38    0.12       0
#XS Ineff= 2 , 0
       0                               0
Bank Sta=9742.573,10244.38
Exp/Cntr=0.3,0.1

Type RM Length L Ch R = 1 ,   15633,189.247800,189.247800,189.247800
XS GIS Cut Line= 2
638349.291133106804182.608199537638580.015975177804181.226613685
#Sta/Elev= 25
9887.0121092.0149892.721 1086.759902.7211079.2919912.7221069.9049922.7221060.576
9932.7221049.9569942.7221039.4999952.7221031.4819962.7221024.2259972.7231013.744
9982.7231009.3949992.7231007.34910002.721005.35110012.721010.65610022.721015.869
10032.72 1019.7310042.721021.59310052.721022.05610062.721023.23810072.721024.877
10082.721026.12710092.721026.32210102.721030.25610112.731036.08510117.741038.849
#Mann= 3 , 0 , 0
9887.012    0.12       09887.012    0.12       010117.74    0.12       0
#XS Ineff= 2 , 0
       0                               0
Bank Sta=9887.012,10117.74
Exp/Cntr=0.3,0.1

Type RM Length L Ch R = 1 ,15443.75,249.641200,249.641200,249.641200
XS GIS Cut Line= 6
638313.338400935804473.288429593638371.461331628804447.079977463
638423.107685632804418.518299568638629.757318849804287.318835945
638691.326218897804255.863013226638751.266413811804230.187258643
#Sta/Elev= 30
9749.0461114.2269761.8381103.563 9769.211095.9159783.7781084.5999793.537 1074.45
9816.8481052.8359858.4291025.7669878.3341010.9629897.839 993.5799909.723985.4795
9921.607980.12369933.491  977.489957.259977.2691 9992.91972.665210004.78972.8954
10016.67974.791510040.46985.126110052.36991.973710063.33999.795410076.081011.492
10099.411017.14410111.071022.81210122.511031.59810133.741041.99310167.431065.279
10178.651070.02110189.761076.74810200.631081.75310233.271094.95310250.971100.992
#Mann= 3 , 0 , 0
9749.046    0.12       09749.046    0.12       010250.97    0.12       0
#XS Ineff= 2 , 0
       0                               0
Bank Sta=9749.046,10250.97
Exp/Cntr=0.3,0.1

Type RM Length L Ch R = 1 ,15194.11,249.641300,249.641300,249.641300
XS GIS Cut Line= 6
638492.794747272804694.369800542 638535.32412159804679.438441085
638589.472884623804643.878715128638764.572373149804462.653655831
638819.691820647804416.687056201638876.166648245804379.000746302
#Sta/Elev= 30
 9749.081086.2939805.4181085.8389816.9831082.6179828.5481072.8959840.6851066.522
9853.5191063.9489857.2671062.5229880.3771047.4529886.7791042.1889907.748 1019.17
9922.1971004.9499929.338998.75679937.007990.52539942.895983.17489951.817969.2917
9956.452963.67279970.009958.93629981.437957.405810010.59957.777210024.13964.8003
10041.52966.626910051.61970.552410069.26980.558110079.78988.228910107.951011.125
10111.811013.00210150.871017.83410154.431018.87710183.021030.35910250.921053.888
#Mann= 3 , 0 , 0
 9749.08    0.12       0 9749.08    0.12       010250.92    0.12       0
#XS Ineff= 2 , 0
       0                               0
Bank Sta=9749.08,10250.92
Exp/Cntr=0.3,0.1

Type RM Length L Ch R = 1 ,14944.47,249.641200,249.641200,249.641200
XS GIS Cut Line= 6
638636.655780953804773.919025494638681.424464066804779.630146324
638731.650165615804772.811569558 638849.96557136804712.203191693
638961.638184424804662.181026383639103.526350081804612.702219432
#Sta/Elev= 30
9749.1411010.3219757.5531007.4169767.6341006.2329777.715998.47459817.954950.1039
9828.162943.93579834.251943.78759859.702  946.859888.895956.00439915.584954.6364
9938.371960.82259961.157957.4809 9972.55952.41719983.712949.2606 10027.5952.5028
10038.46951.6467 10060.4957.318110069.34962.715810082.33974.095110100.57 987.428
10136.411002.01510157.891006.29910179.311000.86510189.771002.75410200.22995.4183
10210.68 991.51610221.13 992.00910231.59996.981510242.04999.321110250.961011.221
#Mann= 3 , 0 , 0
9749.141    0.12       09749.141    0.12       010250.96    0.12       0
#XS Ineff= 2 , 0
       0                               0
Bank Sta=9749.141,10250.96
Exp/Cntr=0.3,0.1

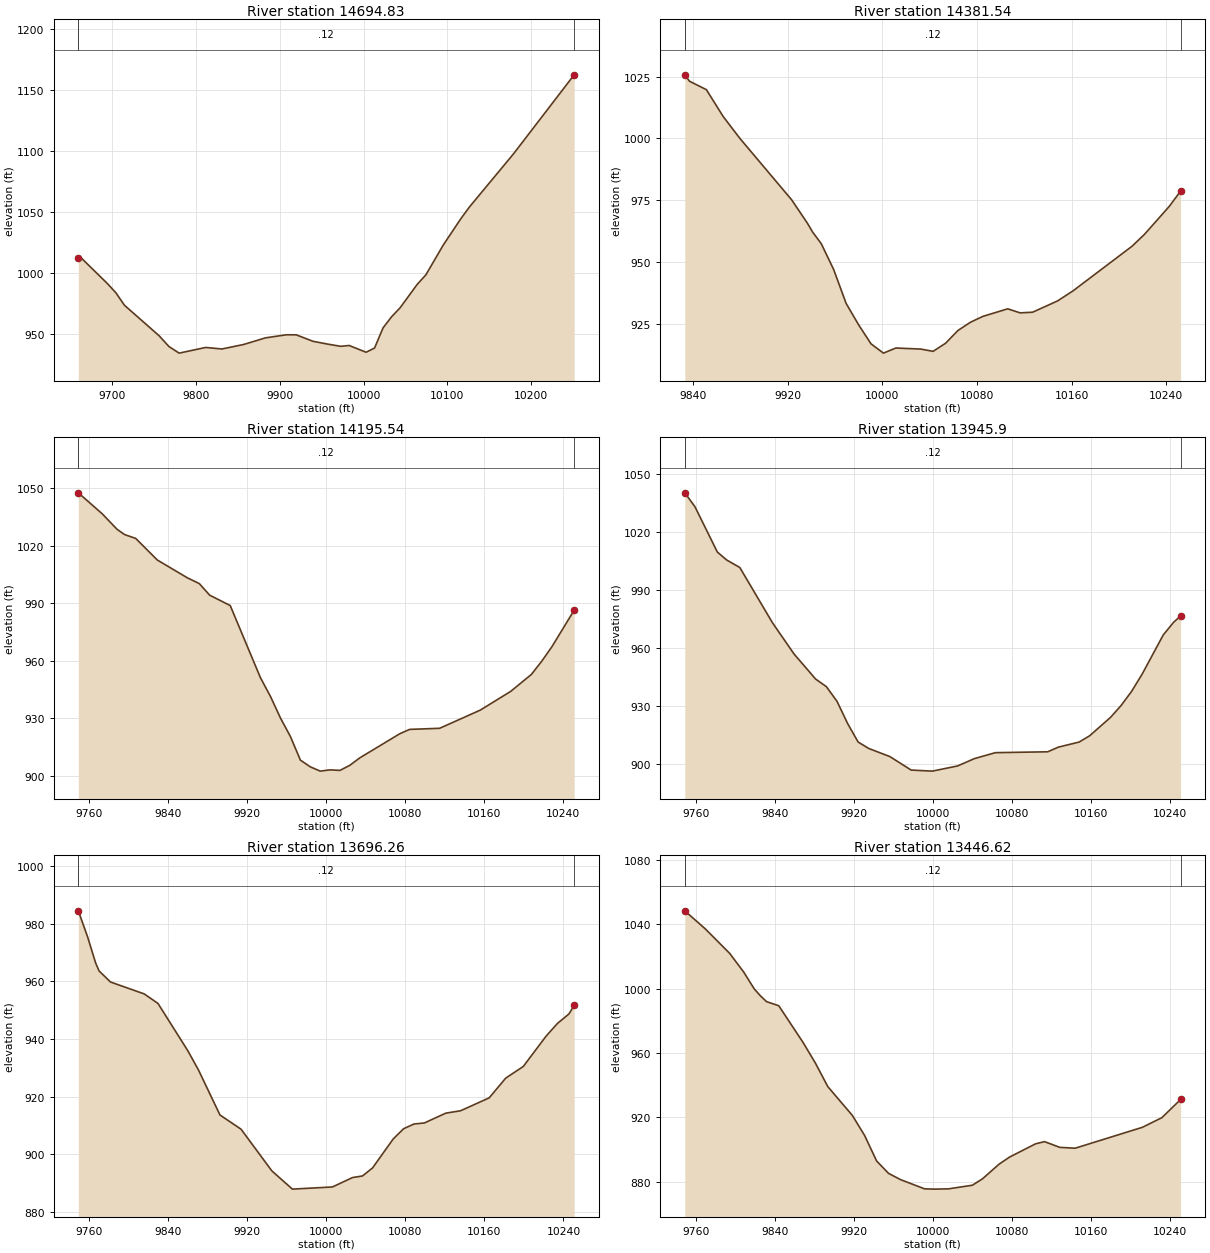
Type RM Length L Ch R = 1 ,14694.83,313.282800,313.282800,313.282800
XS GIS Cut Line= 6
638641.673308611804799.453787372638737.979539692804823.856922612
638843.256741226804907.259516865638882.838512152804930.042820886
639022.924677491804956.082678944639183.162902683805008.179389417
#Sta/Elev= 30
 9660.211012.1269663.6421012.006 9694.59991.18059704.906983.48369715.222973.1939
9756.486948.21469768.121939.43169780.316933.98679811.962938.62939831.331 937.383
9857.286941.09149883.241946.51019908.187949.02079919.867948.97619939.712943.7009
9957.662941.3283 9972.82939.5704 9982.89940.245510003.04  934.7110013.15938.1447
10023.26954.658510033.39 963.75110043.62971.166910064.09 990.42810074.32998.1537
10095.021022.57810115.891044.08710126.321053.86210178.781097.36610250.971162.077
#Mann= 3 , 0 , 0
 9660.21    0.12       0 9660.21    0.12       010250.97    0.12       0
#XS Ineff= 2 , 0
       0                               0
Bank Sta=9660.21,10250.97
Exp/Cntr=0.3,0.1

Type RM Length L Ch R = 1 ,14381.54,185.999700,185.999700,185.999700
XS GIS Cut Line= 3
638580.757561743  804842.2016799638657.703768283804918.079189166
638752.817829192805214.108345032
#Sta/Elev= 30
9833.1261025.6929837.1111023.1099851.3531019.7149865.5951008.8459879.838999.9434
 9923.35975.28869936.806965.75489941.191962.20419948.461957.52929958.964947.0759
9969.468933.41929979.971924.83139990.475917.128910000.98913.364410011.48915.4264
10032.49915.002410042.99914.0874 10053.5917.3524   10064922.5201 10074.5925.8202
10085.01928.190610106.01931.248610116.52929.615210127.02929.873910148.03934.4044
10161.19938.489810211.05956.502410221.55961.284810242.56972.611410252.13978.7693
#Mann= 3 , 0 , 0
9833.126    0.12       09833.126    0.12       010252.13    0.12       0
#XS Ineff= 2 , 0
       0                               0
Bank Sta=9833.126,10252.13
Exp/Cntr=0.3,0.1

Type RM Length L Ch R = 1 ,14195.54,249.641300,249.641300,249.641300
XS GIS Cut Line= 6
638444.560307852804814.837300219638476.316379497804870.022431458
638505.855096604804955.617270611638516.066674992805009.656048228
638530.856553291805159.398127054638567.172584747805296.458410233
#Sta/Elev= 30
9749.1031047.4879773.3411036.5229788.3741028.4399795.9211025.7299807.1971023.714
9828.9521012.4919859.1541003.2619871.5561000.1539881.987994.13639902.849 988.709
9933.395951.11849943.572941.31379953.749929.99249963.846920.32619973.874908.0959
9983.901904.60029993.929902.367410003.95903.024710013.97902.744110023.99905.4389
10034.02909.297310074.31921.818810084.41 924.12710114.81924.704210155.83934.1547
10186.69943.9408 10207.6952.770510218.05959.625110228.51967.310910250.94986.2673
#Mann= 3 , 0 , 0
9749.103    0.12       09749.103    0.12       010250.94    0.12       0
#XS Ineff= 2 , 0
       0                               0
Bank Sta=9749.103,10250.94
Exp/Cntr=0.3,0.1

Type RM Length L Ch R = 1 , 13945.9,249.641200,249.641200,249.641200
XS GIS Cut Line= 6
638174.906005954804866.004374822638205.219961618804922.095791578
638237.686308972804996.399826049638287.200885575805124.740791034
638336.702989252805266.295295793638361.182132333805331.432412558
#Sta/Elev= 30
9749.0391040.2149759.2651033.0719781.9991009.5699791.3031005.5079804.7321001.564
9837.793972.98899859.619956.82859881.445943.86489892.358939.90749903.112932.3491
9914.086920.62219924.567911.23169935.295907.91949956.751903.69789978.206896.7412
9999.661896.197510025.21898.884710042.32902.6901 10063.5905.747810116.47906.2009
10127.07908.588610148.25911.242510158.85914.471810180.04924.015810190.71930.1402
10201.39937.488810212.07946.418710233.44966.707510244.12973.349410250.99 976.463
#Mann= 3 , 0 , 0
9749.039    0.12       09749.039    0.12       010250.99    0.12       0
#XS Ineff= 2 , 0
       0                               0
Bank Sta=9749.039,10250.99
Exp/Cntr=0.3,0.1

Type RM Length L Ch R = 1 ,13696.26,249.641300,249.641300,249.641300
XS GIS Cut Line= 6
637956.239685803804956.766253679637997.139882383 805031.67083371
638027.131042848805104.322682898638055.269379545805237.690839979
638072.260934616805290.565545435638139.715265823805419.587644234
#Sta/Elev= 30
9749.066984.49229758.567 975.3279766.627966.33049770.105963.60969781.643959.7781
9815.777955.64469829.684952.33549859.976935.86859870.921929.06429892.401913.6237
9913.775908.67429944.945894.2057 9965.72887.878910006.23888.631510026.54891.8914
10036.69892.457110046.84895.242310067.75905.295110078.25908.844510088.76910.4844
10099.26910.845310120.96914.251210135.95915.089110164.88919.560310181.61926.4162
10199.35930.444710222.46 940.98610234.02945.414610245.57948.677510250.87951.6443
#Mann= 3 , 0 , 0
9749.066    0.12       09749.066    0.12       010250.87    0.12       0
#XS Ineff= 2 , 0
       0                               0
Bank Sta=9749.066,10250.87
Exp/Cntr=0.3,0.1

Type RM Length L Ch R = 1 ,13446.62,249.641200,249.641200,249.641200
XS GIS Cut Line= 6
637628.295945926805149.719019206637778.481172168805259.963836811
637831.120700743805295.803409894637881.589679809805330.593616145
637933.165588709805374.665146826638023.531002251805457.828835553
#Sta/Elev= 30
9749.0131048.3099769.7341037.1249794.5451021.8119808.6351010.2939819.355999.7824
9825.534995.5307 9831.76991.90779844.165989.34649868.975966.3271 9881.38953.5771
9893.785939.12619918.595921.2631    9931908.83019943.204892.92279955.302885.2207
  9967.4 881.3589991.595875.6551   10001875.446510015.93875.608210040.18877.8719
10050.42881.869510067.09890.902810077.94895.420610104.25903.623810113.27904.9321
10128.64 901.38910144.23 900.87110212.18913.826310232.01919.839710250.95931.1432
#Mann= 3 , 0 , 0
9749.013    0.12       09749.013    0.12       010250.95    0.12       0
#XS Ineff= 2 , 0
       0                               0
Bank Sta=9749.013,10250.95
Exp/Cntr=0.3,0.1

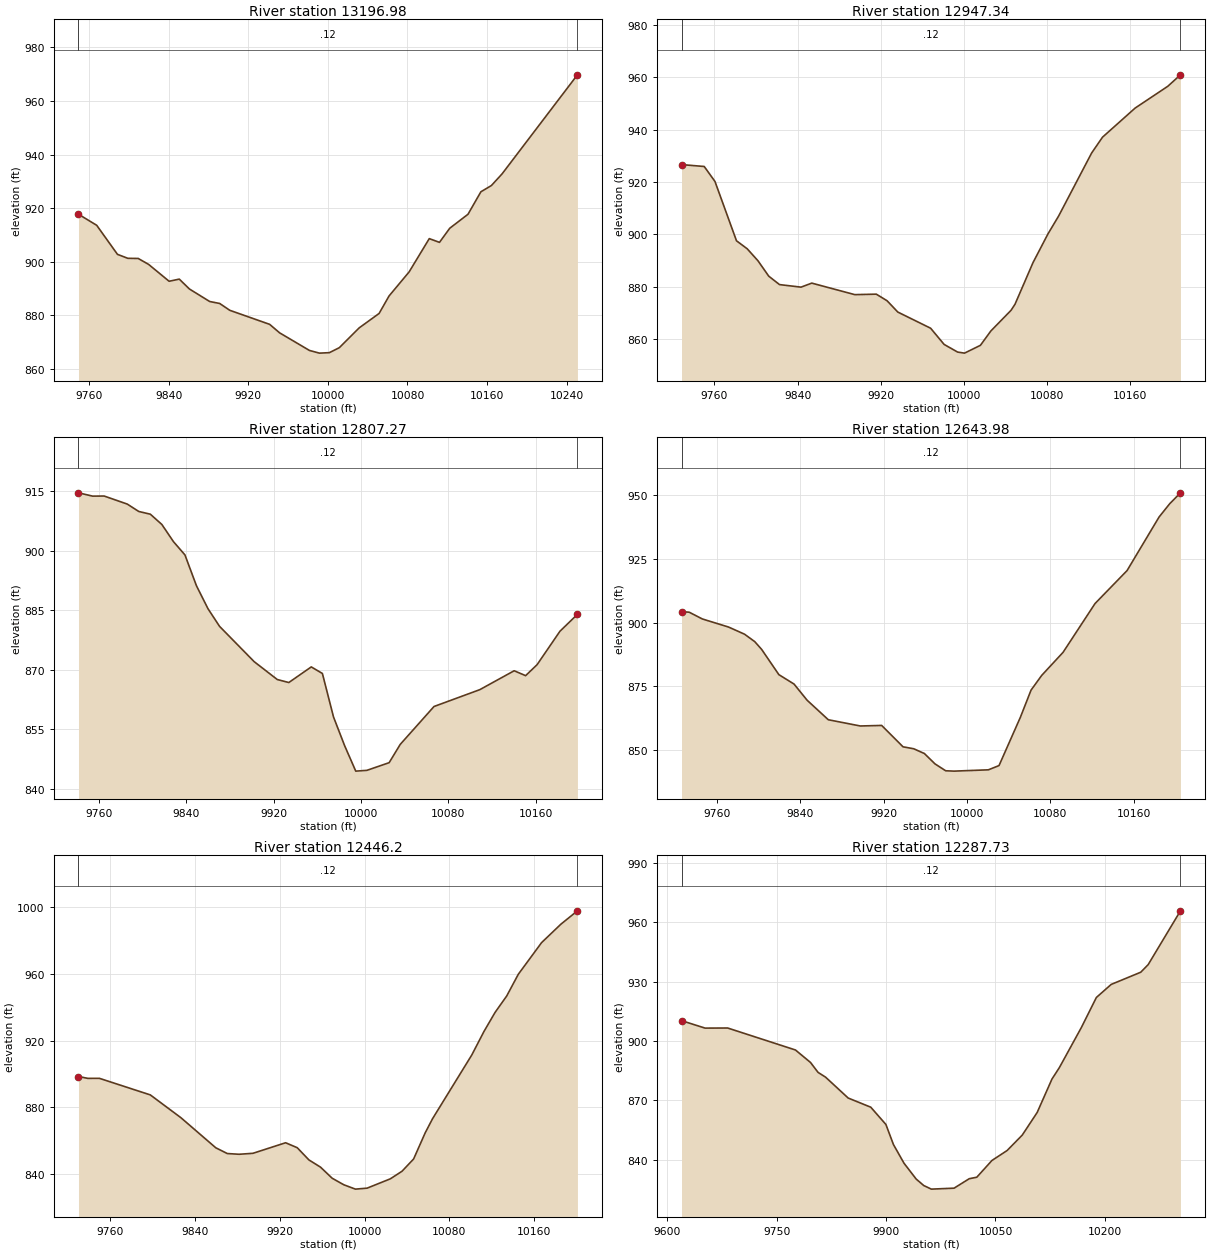
Type RM Length L Ch R = 1 ,13196.98,249.641300,249.641300,249.641300
XS GIS Cut Line= 6
637517.424711771805490.414756693 637667.21516366805526.782598335
 637809.13445818 805527.79791375637869.105560481805535.488892302
637930.502208172805553.950952521638003.246219235805588.744805717
#Sta/Elev= 30
 9749.08917.7241 9767.42913.5853 9788.29902.74559798.725901.2651 9809.16901.2081
9819.595898.99969840.244 892.6989850.463893.50029860.682889.80879881.021885.1466
9891.131884.4043 9901.24881.86119941.344876.61629951.365873.44929981.395866.8698
9991.402865.871410001.41866.044510011.41867.899510031.42875.299610051.44880.6778
10061.47887.215110081.63896.186910101.91908.616510112.17907.219210122.51912.4945
10140.86917.709710153.82926.100510164.41928.437110175.12932.777810250.93969.7605
#Mann= 3 , 0 , 0
 9749.08    0.12       0 9749.08    0.12       010250.93    0.12       0
#XS Ineff= 2 , 0
       0                               0
Bank Sta=9749.08,10250.93
Exp/Cntr=0.3,0.1

Type RM Length L Ch R = 1 ,12947.34,140.065600,140.065600,140.065600
XS GIS Cut Line= 6
637443.890253605805681.361671161637673.095710993805742.450391445
637719.175460099805781.611772269637757.055023462805808.380444329
637808.473586917805825.458893376637886.598586918805849.764448958
#Sta/Elev= 30
9728.329926.60139750.175925.87389760.524920.14729781.223897.49379791.572 894.421
9801.921889.8426 9812.27883.97369822.619880.75839843.317879.78469853.666881.3182
9895.062876.92029915.761877.1018 9926.11874.58499936.459870.2601 9968.01864.0904
9981.005857.8971    9994854.977310000.64854.576710015.91857.554810026.02863.0626
 10045.4870.940410049.22873.259310066.55889.170610080.78900.022110091.31907.0448
10122.92 931.01710133.42937.078110164.84948.205710196.26956.5286 10208.4960.8902
#Mann= 3 , 0 , 0
9728.329    0.12       09728.329    0.12       0 10208.4    0.12       0
#XS Ineff= 2 , 0
       0                               0
Bank Sta=9728.329,10208.4
Exp/Cntr=0.3,0.1

Type RM Length L Ch R = 1 ,12807.27,163.297200,163.297200,163.297200
XS GIS Cut Line= 4
637372.754461763805800.763888892637560.016413773 805864.50587877
637673.037491257805886.168251915637810.254461767805929.236111108
#Sta/Elev= 30
9741.423914.54039754.358913.70889764.922 913.7339786.049 911.7079796.612909.8394
9807.176909.15819817.739 906.5659828.302902.25739838.866898.89349849.429891.1014
9859.993885.32329870.556880.88319902.247871.98689923.373  867.499933.937866.7308
9954.492870.66689964.674869.01549974.856858.05419985.038850.8126 9995.22844.4023
 10005.4844.598510025.77846.530410035.95851.144210066.85860.689110108.78864.9348
10140.22869.6986 10150.7868.463910161.18871.224510182.14879.658610198.13883.9183
#Mann= 3 , 0 , 0
9741.423    0.12       09741.423    0.12       010198.13    0.12       0
#XS Ineff= 2 , 0
       0                               0
Bank Sta=9741.423,10198.13
Exp/Cntr=0.3,0.1

Type RM Length L Ch R = 1 ,12643.98,197.778700,197.778700,197.778700
XS GIS Cut Line= 3
637388.388563137805899.129671753637471.721896486806008.504671822
637805.055229795806081.421338457
#Sta/Elev= 30
9726.056904.31759733.436904.10789746.008901.45759771.151898.28219786.466895.4803
9796.295892.55869802.967889.47479819.467879.5765 9834.01  875.889846.582869.5178
9866.915861.85479897.625859.40469918.098859.61989938.571851.22569948.807850.4598
9959.043848.5988 9969.28844.50949979.516841.80559987.545841.669710020.46842.1798
 10030.7843.854810051.17 862.80810061.41873.484410071.64879.278510092.12888.3309
10122.83907.518510153.54920.458410184.25941.500810194.48 946.73410204.78 951.009
#Mann= 3 , 0 , 0
9726.056    0.12       09726.056    0.12       010204.78    0.12       0
#XS Ineff= 2 , 0
       0                               0
Bank Sta=9726.056,10204.78
Exp/Cntr=0.3,0.1

Type RM Length L Ch R = 1 , 12446.2,158.471600,158.471600,158.471600
XS GIS Cut Line= 2
637397.015253604805946.986671174637591.459698053806375.806115598
#Sta/Elev= 30
9729.986898.52089738.785897.40999749.765897.42299797.751887.52169826.625873.8903
9859.565855.88779870.395852.44539881.525852.0129 9894.61852.58619925.445858.8967
9936.425855.93529947.405848.64719958.385844.30869969.365837.68459980.345833.7692
9991.325831.161810002.31831.741710024.27837.324110035.25841.832910046.23  849.18
10057.21864.889410064.11873.280910101.13911.391710112.54925.351910123.09936.8439
10134.07946.668310145.05959.685810167.01978.607910185.19989.601410200.83997.6161
#Mann= 3 , 0 , 0
9729.986    0.12       09729.986    0.12       010200.83    0.12       0
#XS Ineff= 2 , 0
       0                               0
Bank Sta=9729.986,10200.83
Exp/Cntr=0.3,0.1

Type RM Length L Ch R = 1 ,12287.73,242.154900,242.154900,242.154900
XS GIS Cut Line= 4
 637317.15414247805823.722782284637384.862475813806084.139448936
637329.306920232806280.320004474637365.765253602806488.653337839
#Sta/Elev= 30
9619.333910.3016 9651.65906.52469682.647906.57319775.639895.45559796.304889.1389
9806.637884.12789816.969881.70739847.967871.14679878.964866.51199899.695857.7866
9910.088847.60799924.604838.14249941.268830.15169951.661826.87729962.055 825.064
9993.234825.548310014.02 830.33210024.41831.0897 10045.2839.564210065.99844.5922
10086.77852.404210107.21863.830610127.51880.736710137.66886.528710168.12907.0048
10188.42922.010110208.73928.617810249.33 934.79810259.49938.6315 10303.8965.8559
#Mann= 3 , 0 , 0
9619.333    0.12       09619.333    0.12       0 10303.8    0.12       0
#XS Ineff= 2 , 0
       0                               0
Bank Sta=9619.333,10303.8
Exp/Cntr=0.3,0.1