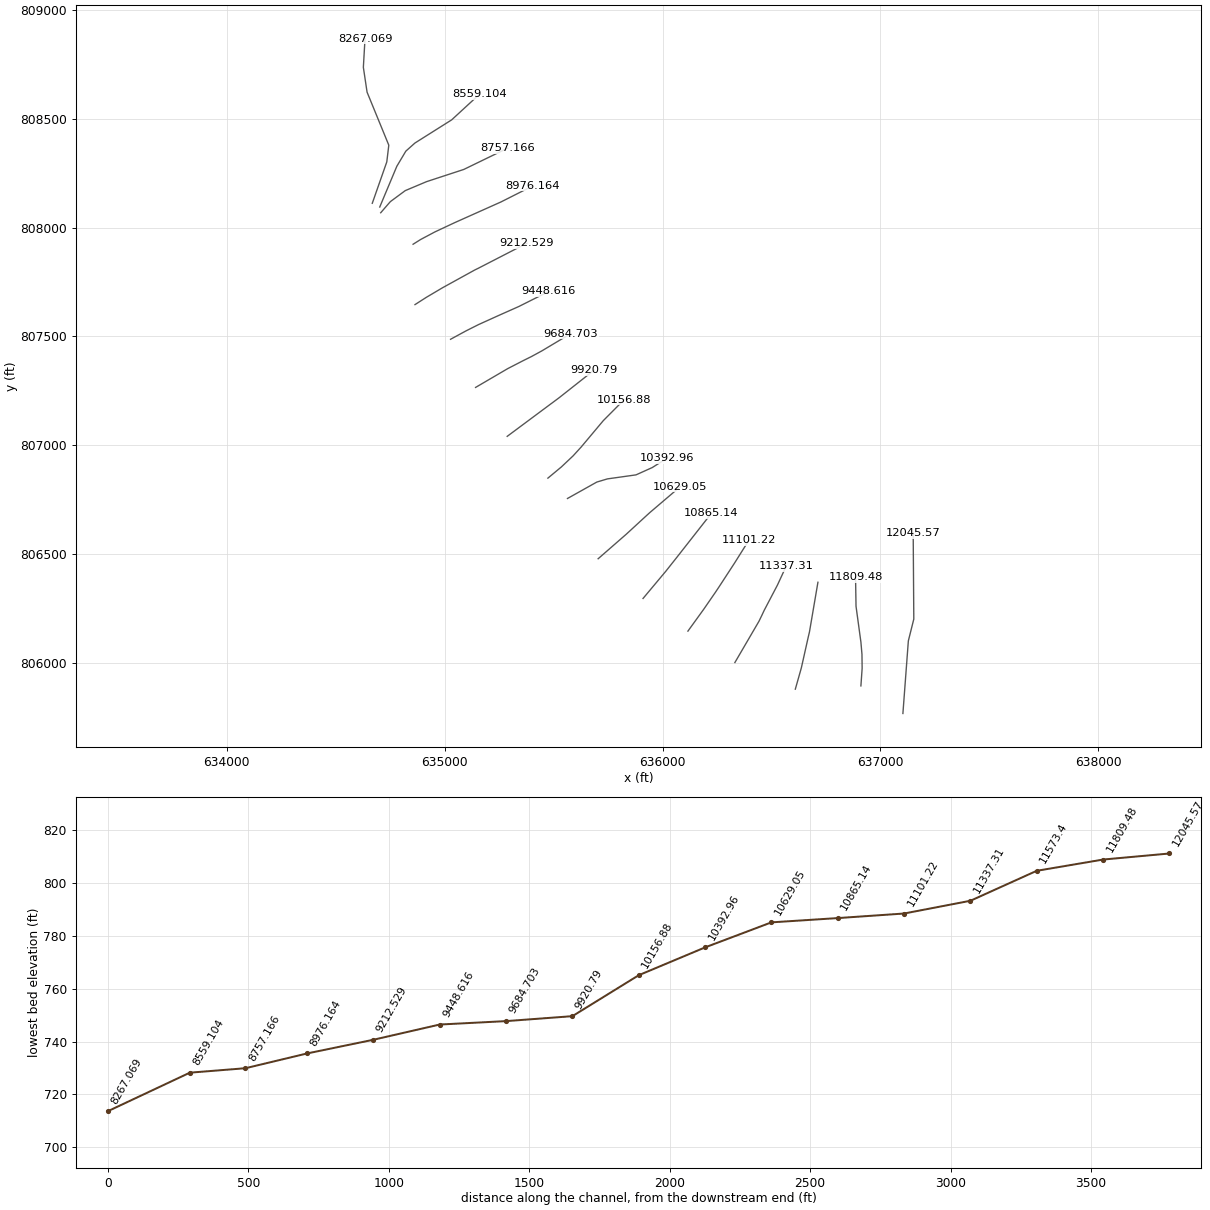
HEC-RAS study 12582_ras.prj: 12582

--- 12582_ras.g01 (geometry) --- (continued)

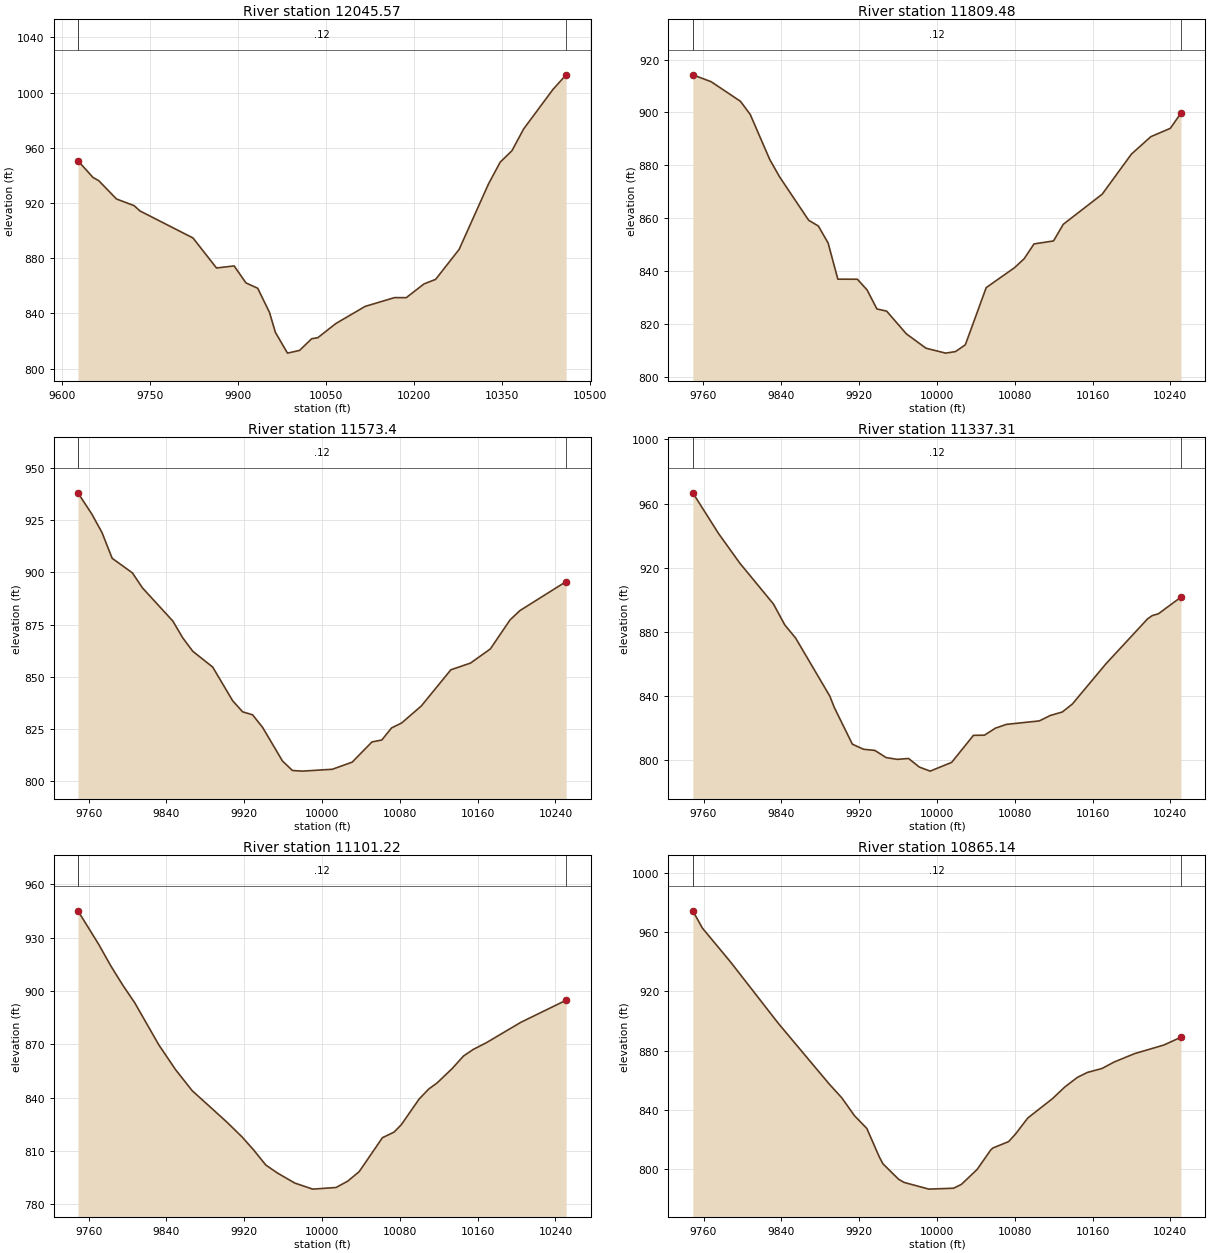
Type RM Length L Ch R = 1 ,12045.57,236.086800,236.086800,236.086800
XS GIS Cut Line= 4
637102.918031365805769.556115597637127.918031364806102.889448945
637152.918031365806202.889448936637150.140253574806597.333893388
#Sta/Elev= 30
9627.243950.56899652.758938.54669662.786 936.1119692.871922.88259722.955918.0529
9732.983 914.1979823.236894.63049863.348872.86559893.432874.35969913.488862.0628
9933.545858.15689953.601 840.6979963.688826.18879984.303 811.16110004.92813.1502
10025.53 821.62110035.84 822.322 10066.7832.6105 10116.7845.0511 10166.7851.3874
 10186.7851.3632 10216.7861.2779 10236.7864.624610276.71886.329110326.71933.7235
10346.71 949.58310366.71957.844910386.71973.661910436.711002.33110459.041012.854
#Mann= 3 , 0 , 0
9627.243    0.12       09627.243    0.12       010459.04    0.12       0
#XS Ineff= 2 , 0
       0                               0
Bank Sta=9627.243,10459.04
Exp/Cntr=0.3,0.1

Type RM Length L Ch R = 1 ,11809.48,236.086700,236.086700,236.086700
XS GIS Cut Line= 6
636910.123293732805896.117154474636915.811185755   805976.599871
636915.019954052806040.754456842636910.220874667806096.615275405
636887.744861289806261.701505072636885.560243285806395.977210545
#Sta/Elev= 30
9749.058 914.2349767.988911.61259798.062904.19959808.087899.23089828.137882.1919
9838.142875.67589868.144859.17939878.145 856.9829888.146850.55759898.162836.8656
9918.235836.84529928.272832.76419938.309825.59269948.346824.76339968.554816.1801
9988.774810.727710009.01808.863810019.13809.452210029.25812.0305 10050.7833.6706
 10079.7841.182310089.76844.614810099.82850.209710119.92851.344810129.93857.6409
10169.97869.054810199.99884.216610219.99890.827810239.99893.976210250.97899.7622
#Mann= 3 , 0 , 0
9749.058    0.12       09749.058    0.12       010250.97    0.12       0
#XS Ineff= 2 , 0
       0                               0
Bank Sta=9749.058,10250.97
Exp/Cntr=0.3,0.1

Type RM Length L Ch R = 1 , 11573.4,236.086800,236.086800,236.086800
XS GIS Cut Line= 6
636609.134098211805881.171045167636636.776141007805978.805366933
636669.246166805806123.708467186636669.738043045806125.647038248
636674.075231942806144.047288745636712.913129023806371.841303136
#Sta/Elev= 30
9749.032938.23659763.404927.95589773.797919.1335 9784.19906.81169804.976899.8177
9815.369892.59759846.549 876.6939856.852868.5655  9867.1862.15719887.596854.5736
9908.092838.4145 9918.34833.08329928.588831.65829938.836825.65449959.332809.4681
 9969.58804.91439979.828804.609410010.61805.503210031.02808.9277 10051.3818.6151
10061.45819.555410071.59825.387810081.74827.687210102.03 835.86610132.46853.2621
10152.75856.509110173.04863.262810193.32877.219610203.47881.686310250.99895.6212
#Mann= 3 , 0 , 0
9749.032    0.12       09749.032    0.12       010250.99    0.12       0
#XS Ineff= 2 , 0
       0                               0
Bank Sta=9749.032,10250.99
Exp/Cntr=0.3,0.1

Type RM Length L Ch R = 1 ,11337.31,236.086800,236.086800,236.086800
XS GIS Cut Line= 6
636331.720875313 806003.34097393636442.376234957806192.953035793
636455.670553098806220.335015714636466.209769677806242.861929956
 636527.06389284806358.887979429636567.395477406806446.105158527
#Sta/Elev= 30
9749.022966.74099775.368941.47039797.257922.97739831.992897.3796 9843.57 884.413
9854.728876.21579889.883 840.0359894.407833.0656 9913.04810.08679924.618806.8923
9936.196806.18639947.775801.71029959.353800.60719970.837801.16129981.953795.7962
9993.069793.270610015.18798.737510037.58815.588110048.87815.672610060.16 820.048
10071.45822.408910105.33824.575310116.62827.970810128.91830.123110139.21835.0541
 10173.8860.171110216.71888.251410221.45890.214810227.73891.341210250.98901.7389
#Mann= 3 , 0 , 0
9749.022    0.12       09749.022    0.12       010250.98    0.12       0
#XS Ineff= 2 , 0
       0                               0
Bank Sta=9749.022,10250.98
Exp/Cntr=0.3,0.1

Type RM Length L Ch R = 1 ,11101.22,236.086700,236.086700,236.086700
XS GIS Cut Line= 6
636116.216610836806147.615071367 636188.78888424 806248.02970474
636243.090096337806326.775060605636261.042514833806353.804461532
636330.480716292806460.366149227636395.811328982806564.355032355
#Sta/Elev= 30
9749.005945.13629770.455926.17079782.793914.14999795.131903.2615 9807.47 893.316
9832.146869.69239849.359855.72769866.431 843.9069901.455826.53739917.807 817.828
9929.954810.31439942.102 802.0479954.249 797.4879972.003791.85939990.434788.4479
10014.36789.3673 10026.3792.896110038.23798.316110062.11 817.40610074.04820.5401
10081.52824.726510099.83839.159310109.85844.874210118.15848.154510133.66 856.244
10145.47863.394110155.48867.102810169.09870.917610204.52882.3913   10251894.8118
#Mann= 3 , 0 , 0
9749.005    0.12       09749.005    0.12       0   10251    0.12       0
#XS Ineff= 2 , 0
       0                               0
Bank Sta=9749.005,10251
Exp/Cntr=0.3,0.1

Type RM Length L Ch R = 1 ,10865.14,236.086800,236.086800,236.086800
XS GIS Cut Line= 5
635910.231856367806297.487514602 636015.15331951 806422.91501816
636068.832270403806490.697412174636070.065216054806492.272164542
 636224.38839082806688.952675304
#Sta/Elev= 30
9749.011974.22999758.806962.64279787.614939.9323 9837.03898.3428 9889.18857.5993
9902.218848.23159915.196836.22179927.952827.59769940.708808.51369944.505803.7814
9960.612793.3717 9966.22791.24799991.732786.720710017.18787.340510025.19  789.92
10041.39800.009410055.31813.071910057.59814.428910073.79818.758210080.73823.7646
10093.44834.630610118.87847.704810131.58855.566710144.29861.949210154.79865.3645
10169.71868.000610182.42872.416110203.39878.041510233.26883.7899   10251889.0614
#Mann= 3 , 0 , 0
9749.011    0.12       09749.011    0.12       0   10251    0.12       0
#XS Ineff= 2 , 0
       0                               0
Bank Sta=9749.011,10251
Exp/Cntr=0.3,0.1

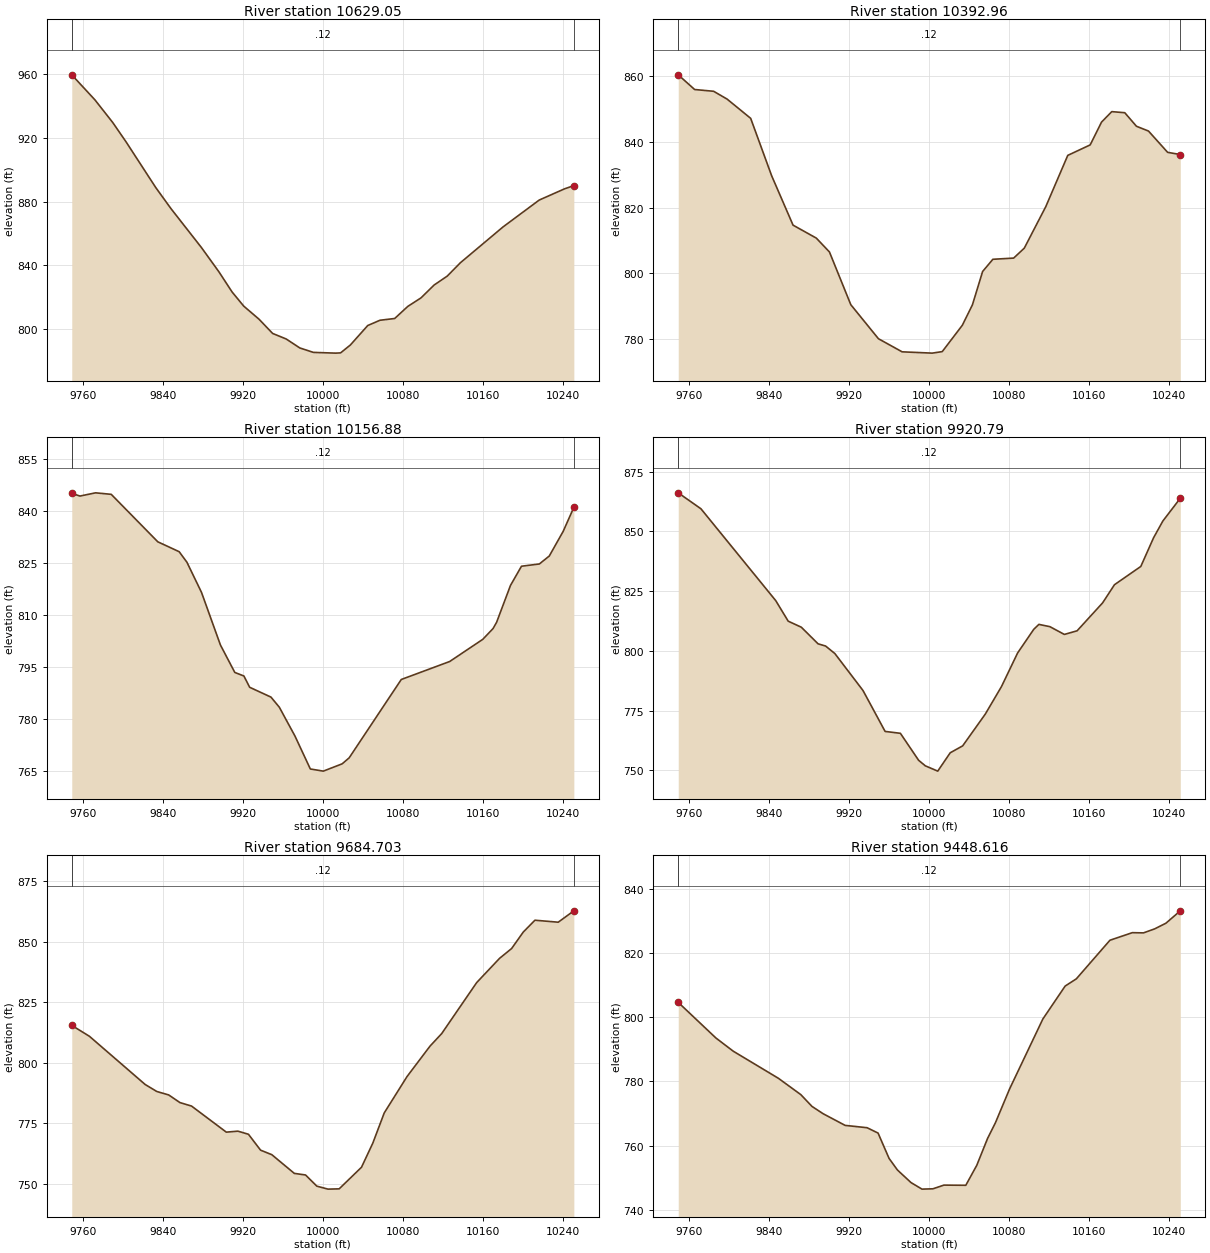
Type RM Length L Ch R = 1 ,10629.05,236.086800,236.086800,236.086800
XS GIS Cut Line= 6
635704.176890584806479.799034167635833.748855202806592.822337416
635891.190968091806645.665993461635892.617216856806647.068068516
635940.734581337806691.154668531  636081.3555518806810.946988904
#Sta/Elev= 30
9749.009959.37839772.134 943.7249789.911929.5685 9803.18917.51049832.985888.7865
9848.198875.58749878.623851.24129896.069836.08279909.339823.36049920.948814.5366
9936.236 806.3399949.824797.43239963.412793.9543    9977788.35139990.588 785.562
10012.74785.100710017.79785.258310027.54790.186610044.92802.384110057.15805.6869
10071.86806.7824   10085814.373610098.14819.675810111.27827.733710124.41833.3312
10137.55841.699410180.13864.096410216.37 880.95810241.82888.019310250.99889.9914
#Mann= 3 , 0 , 0
9749.009    0.12       09749.009    0.12       010250.99    0.12       0
#XS Ineff= 2 , 0
       0                               0
Bank Sta=9749.009,10250.99
Exp/Cntr=0.3,0.1

Type RM Length L Ch R = 1 ,10392.96,236.086700,236.086700,236.086700
XS GIS Cut Line= 6
635563.433095111806756.368498577 635697.99171122806831.707485166
635746.741279281 806846.26758272635877.972024439806864.739975215
635952.660699223806898.397425776636021.436475555806942.037158171
#Sta/Elev= 30
9749.065860.4347 9765.46855.95899784.454855.42029797.956853.0301 9821.48847.1704
9842.444829.67679863.824814.6278 9887.04810.68869900.222806.45139921.558790.3866
9949.195 780.0129972.855776.021710002.93775.625510012.96776.086310033.02784.1077
10043.13 790.345 10053.3800.491310063.55804.222110084.34804.587110094.98807.6209
10116.49820.286110138.43835.887110160.85839.085610172.16846.0168 10182.4849.2181
 10195.4848.8896 10207.1844.757410219.12 843.30110238.25836.812810250.92836.1393
#Mann= 3 , 0 , 0
9749.065    0.12       09749.065    0.12       010250.92    0.12       0
#XS Ineff= 2 , 0
       0                               0
Bank Sta=9749.065,10250.92
Exp/Cntr=0.3,0.1

Type RM Length L Ch R = 1 ,10156.88,236.086800,236.086800,236.086800
XS GIS Cut Line= 6
635473.536885919806849.765762463635535.595899122806901.358084661
635589.214571728 806951.93884515635626.284396675806992.600520334
635727.933519008807113.730104722 635822.68284855807208.962849549
#Sta/Elev= 30
9749.037845.17289757.224844.39449772.867845.32379788.509844.88599835.048831.2032
9856.416828.35279864.194825.30289878.767816.60739897.658801.46249912.039793.5467
9921.126792.52559926.882789.2726 9948.19786.43929956.568783.51479972.143775.2353
9987.554765.717610000.52 765.10210019.37767.205310026.34768.920610078.48791.5196
10126.84796.698510159.93803.0853 10170.2806.191410173.78808.004310187.65818.6355
10198.64824.165710216.47824.810210226.42827.102510240.31834.204910250.99841.1316
#Mann= 3 , 0 , 0
9749.037    0.12       09749.037    0.12       010250.99    0.12       0
#XS Ineff= 2 , 0
       0                               0
Bank Sta=9749.037,10250.99
Exp/Cntr=0.3,0.1

Type RM Length L Ch R = 1 , 9920.79,236.086800,236.086800,236.086800
XS GIS Cut Line= 5
635286.779827611807041.546331082635487.370232615807190.752323445
635489.008224901807191.899921489635524.764456676807218.519222219
635686.002084005 807345.79146543
#Sta/Elev= 30
9749.002 866.167 9771.71859.48249846.489821.02089858.952812.41189872.075809.8815
9888.831802.92219896.341801.99959905.586798.8605 9933.73783.37759955.851766.2334
 9971.12765.44849989.362754.14319996.046751.825210008.47749.607710020.94757.2901
 10033.4760.195610056.04773.515810072.18785.016710088.32799.092810104.46808.9949
10109.58811.0677 10120.6 810.10810135.06806.8593 10147.8808.381610173.28820.0631
10185.16827.6785 10211.5835.332510224.24847.325410233.58854.385510250.99863.9059
#Mann= 3 , 0 , 0
9749.002    0.12       09749.002    0.12       010250.99    0.12       0
#XS Ineff= 2 , 0
       0                               0
Bank Sta=9749.002,10250.99
Exp/Cntr=0.3,0.1

Type RM Length L Ch R = 1 ,9684.703,236.086700,236.086700,236.086700
XS GIS Cut Line= 6
635141.627726965807266.084175398635289.247064678807352.417618146
635359.422822144807388.615757235635397.519958613807407.507483039
635445.843515085807433.835666244635578.396916494807513.066659072
#Sta/Elev= 30
9749.027815.45749766.688810.94779822.441791.00139834.026788.11989845.921786.6969
9857.195783.5243 9868.78782.08649903.534771.30379915.118771.70719925.671770.4272
9937.764763.85919949.016761.98369971.519754.24839982.771753.58439994.023748.9692
10005.21 747.73510016.38 747.85110038.71756.793710050.04766.799610061.43  779.26
10084.21794.292410107.22806.894210118.87812.066310153.82833.149810176.79843.2135
10188.77847.241310200.42854.054810212.07 858.95410235.37858.130210250.98862.8369
#Mann= 3 , 0 , 0
9749.027    0.12       09749.027    0.12       010250.98    0.12       0
#XS Ineff= 2 , 0
       0                               0
Bank Sta=9749.027,10250.98
Exp/Cntr=0.3,0.1

Type RM Length L Ch R = 1 ,9448.616,236.086800,236.086800,236.086800
XS GIS Cut Line= 6
635026.714188583807487.042423197635097.647747695807525.539753729
635154.973777524807554.379871648635250.718747744807597.734767395
635339.855139479807637.374209902635477.889479726807706.610234215
#Sta/Elev= 30
9749.018804.57199786.664793.49319803.956789.39189849.149780.94479871.537775.8706
9882.732772.19519893.896769.9111 9915.88766.28449937.835765.55789948.813 763.889
 9959.79756.01489968.128752.41349981.745748.47859992.722746.443410003.67 746.545
10014.62747.694110036.51747.639110047.46753.8341 10058.4762.302110066.12767.0919
10080.29777.626110113.56799.398810135.87 809.65810147.06811.906210180.62823.9131
   10203826.268910214.18826.206210225.37827.456310236.56829.210210250.98833.0703
#Mann= 3 , 0 , 0
9749.018    0.12       09749.018    0.12       010250.98    0.12       0
#XS Ineff= 2 , 0
       0                               0
Bank Sta=9749.018,10250.98
Exp/Cntr=0.3,0.1

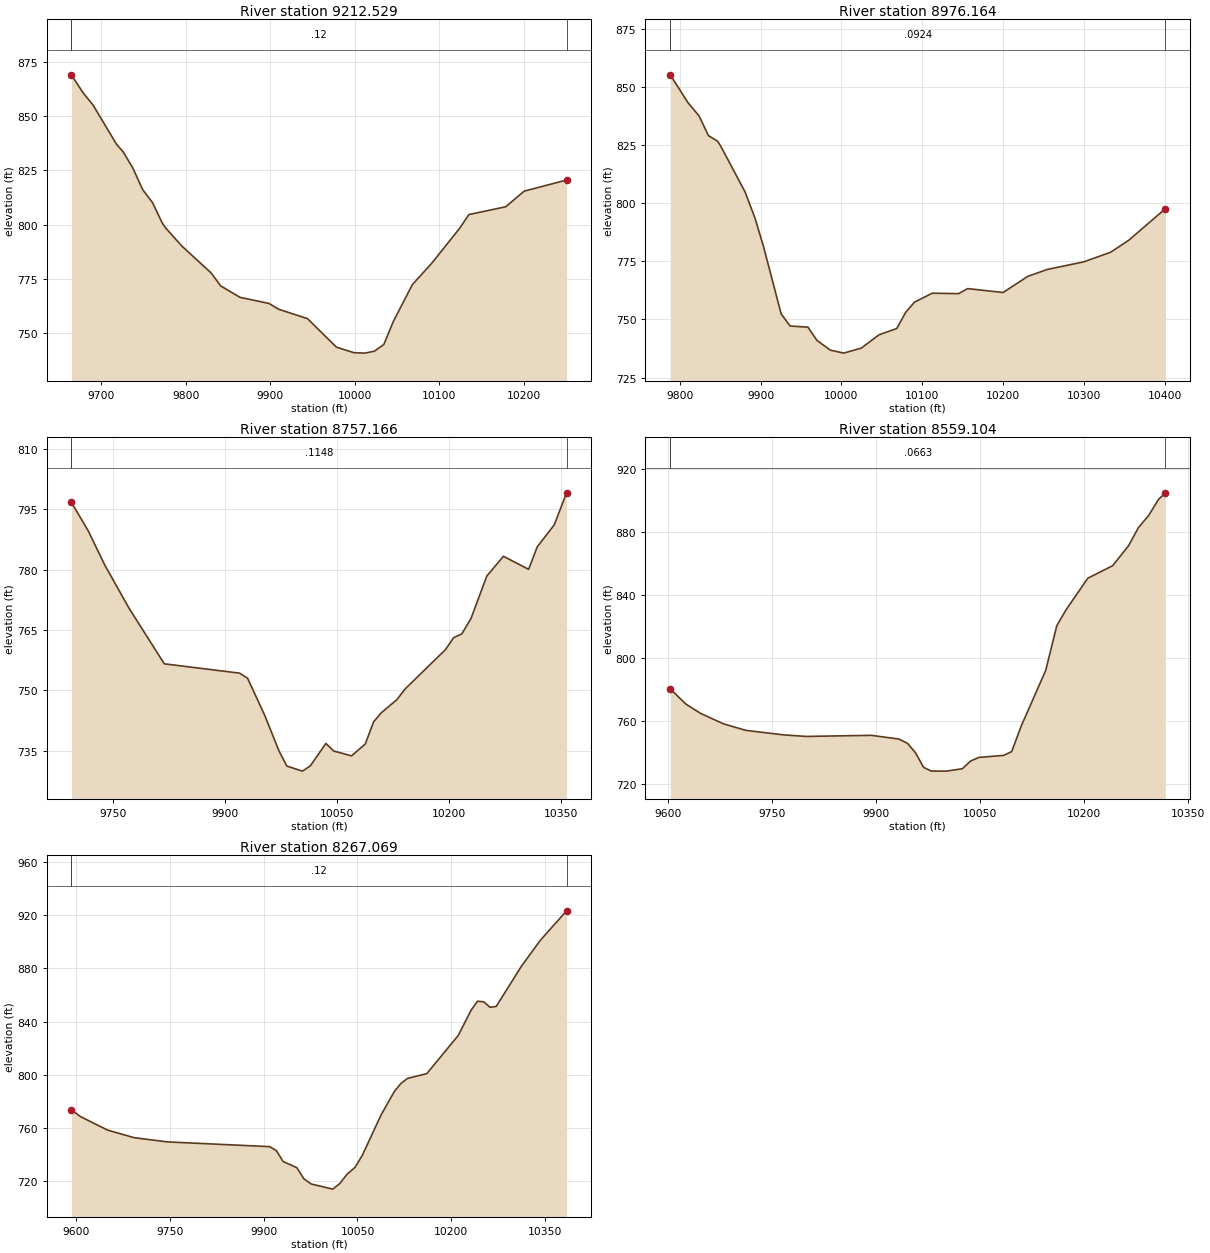
Type RM Length L Ch R = 1 ,9212.529,236.365000,236.365000,236.365000
XS GIS Cut Line= 6
634863.559047363807646.224095871634915.574895502807679.532061596
634989.941862255807723.554316731635137.985206052807805.121266772
635155.204492951807813.573287032635377.290816392807927.962029939
#Sta/Elev= 30
9664.601869.08029678.265860.86469690.121855.19159717.933837.08669725.688833.6365
9737.322 826.0859748.943816.12219760.564810.16579772.184800.69819776.366798.3531
9795.426790.07229829.982777.69389841.399771.69269864.234766.42079898.486763.6116
9909.903760.94749944.156756.58449978.408743.4358    9999740.904610012.02740.6864
10023.27741.569110034.52744.695910045.76755.311310068.26772.281210091.47782.2713
 10124.5798.405210135.15804.611610178.83808.209610200.67815.420910250.81820.5306
#Mann= 3 , 0 , 0
9664.601    0.12       09664.601    0.12       010250.81    0.12       0
#XS Ineff= 2 , 0
       0                               0
Bank Sta=9664.601,10250.81
Exp/Cntr=0.3,0.1

Type RM Length L Ch R = 1 ,8976.164,218.998100,218.998100,218.998100
XS GIS Cut Line= 6
634854.764246526807923.239608468 634889.85957012807945.244397094
634954.977669433807979.801240523635045.049967371808022.015938935
635258.389238378808117.459853048635404.948467189808191.448976855
#Sta/Elev= 30
9788.302855.24019810.441843.1853 9823.99837.56539835.545829.07979846.866826.6932
9850.537824.71659880.829804.89469893.203 793.5449903.445781.68299925.562752.3657
9936.609747.15499958.701746.66059969.748740.99679986.301736.784910002.86735.4894
10024.77737.676610046.69743.3914 10068.6746.093910079.55753.017810090.51 757.438
10112.42 761.26810145.28761.095210156.24763.251910200.06761.567810230.61768.5125
10255.09771.527910299.84 774.75610333.22778.916610355.75784.114110400.83797.6255
#Mann= 3 , 0 , 0
9788.302  0.0924       09788.302  0.0924       010400.83  0.0924       0
#XS Ineff= 2 , 0
       0                               0
Bank Sta=9788.302,10400.83
Exp/Cntr=0.3,0.1

Type RM Length L Ch R = 1 ,8757.166,198.061700,198.061700,198.061700
XS GIS Cut Line= 6
634706.175605808808067.735142446634750.340124377808118.696615646
634818.829204208808169.344800481634916.754273779808210.590911064
635087.444230728808266.510668838 635289.28423417 808364.45957094
#Sta/Elev= 30
9693.624796.71999715.911789.75259738.585781.0668 9770.81770.43159818.058756.5995
9919.029 754.2749929.682753.01479952.856743.70289971.916734.88759982.362 731.171
10003.27729.913510013.73731.214110034.66736.801310045.12 734.91510069.02733.7161
10087.41736.664510098.54742.160110108.67 744.38510129.93747.716110140.72750.3361
10194.94 760.14610205.79763.089310216.86764.055910229.12767.883810250.27778.4279
10272.55783.340210306.31780.088710317.78785.665310340.72791.1697 10357.1799.1151
#Mann= 3 , 0 , 0
9693.624  0.1148       09693.624  0.1148       0 10357.1  0.1148       0
#XS Ineff= 2 , 0
       0                               0
Bank Sta=9693.624,10357.1
Exp/Cntr=0.3,0.1

Type RM Length L Ch R = 1 ,8559.104,292.035200,292.035200,292.035200
XS GIS Cut Line= 6
 634701.75504589808094.086603925 634780.19427264808281.126440311
634821.603665968808350.646737465634863.294518444808387.814709435
 635032.01320115808494.203267353635159.702432404808611.833969091
#Sta/Elev= 30
9603.389780.43429625.975770.81979647.575764.80179679.975758.29689712.375754.1158
9766.676751.25179799.525750.2641 9893.29750.96439932.865748.61489945.298745.9249
9956.892739.91399968.486730.66759979.626728.257510001.37728.2232 10024.4729.7349
10036.22734.599810048.16736.937710083.98738.220410095.55740.639910109.24756.8199
10144.57792.1855 10160.6820.663610173.89830.706510205.34850.810410241.06 858.711
10263.93  871.3910278.34883.032310292.76890.498910307.17900.845910317.02905.0282
#Mann= 3 , 0 , 0
9603.389  0.0663       09603.389  0.0663       010317.02  0.0663       0
#XS Ineff= 2 , 0
       0                               0
Bank Sta=9603.389,10317.02
Exp/Cntr=0.3,0.1

Type RM Length L Ch R = 1 ,8267.069,236.364900,236.364900,236.364900
XS GIS Cut Line= 6
634667.490630469808111.218811636634734.132567321808301.130731852
634743.316063073808377.922119288634643.601158943808621.269511133
634626.570781207808735.236227291  634634.1845786808866.930581511
#Sta/Elev= 30
9592.893773.30049607.716768.25899650.588 758.1659693.159752.42469746.023749.2543
9909.669745.66599920.398742.6476 9931.25734.45779953.126729.79279964.601721.3076
9976.076717.504510010.51713.630310021.97717.921910033.14724.776210046.08730.0469
10057.88739.240410087.89 769.75210109.07787.353710119.53793.350210129.99797.1033
10160.85800.767110211.01829.477410231.67848.6249 10241.7855.303510251.73 854.918
10261.73850.746310271.73851.416610311.76881.531910341.86901.063510384.08923.4852
#Mann= 3 , 0 , 0
9592.893    0.12       09592.893    0.12       010384.08    0.12       0
#XS Ineff= 2 , 0
       0                               0
Bank Sta=9592.893,10384.08
Exp/Cntr=0.3,0.1