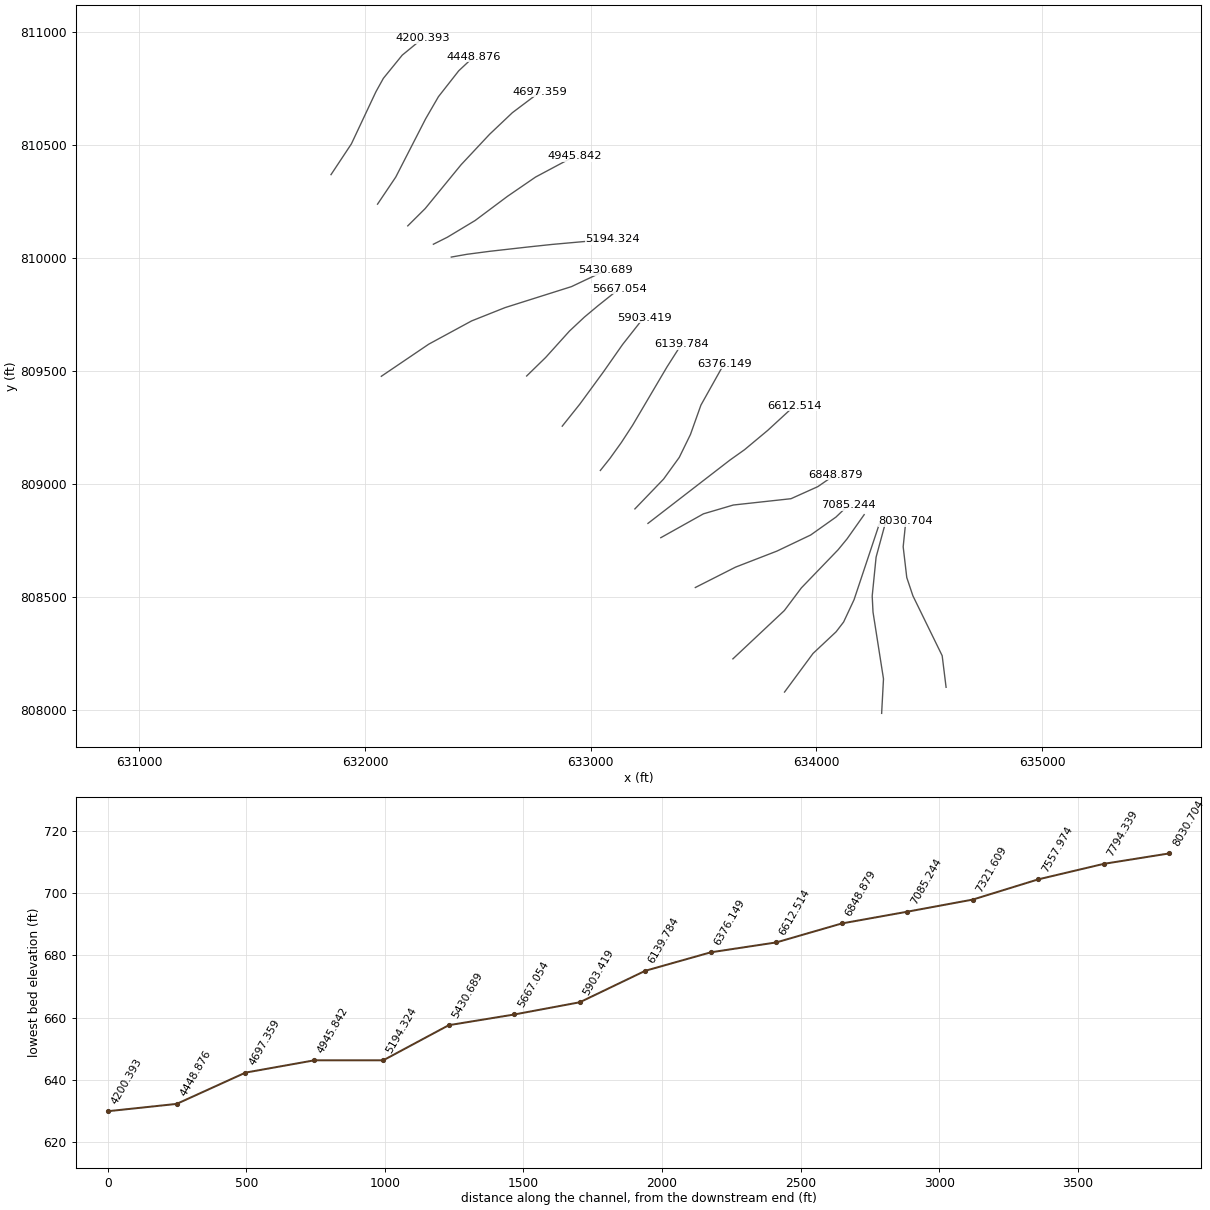
HEC-RAS study 12582_ras.prj: 12582

--- 12582_ras.g01 (geometry) --- (continued)

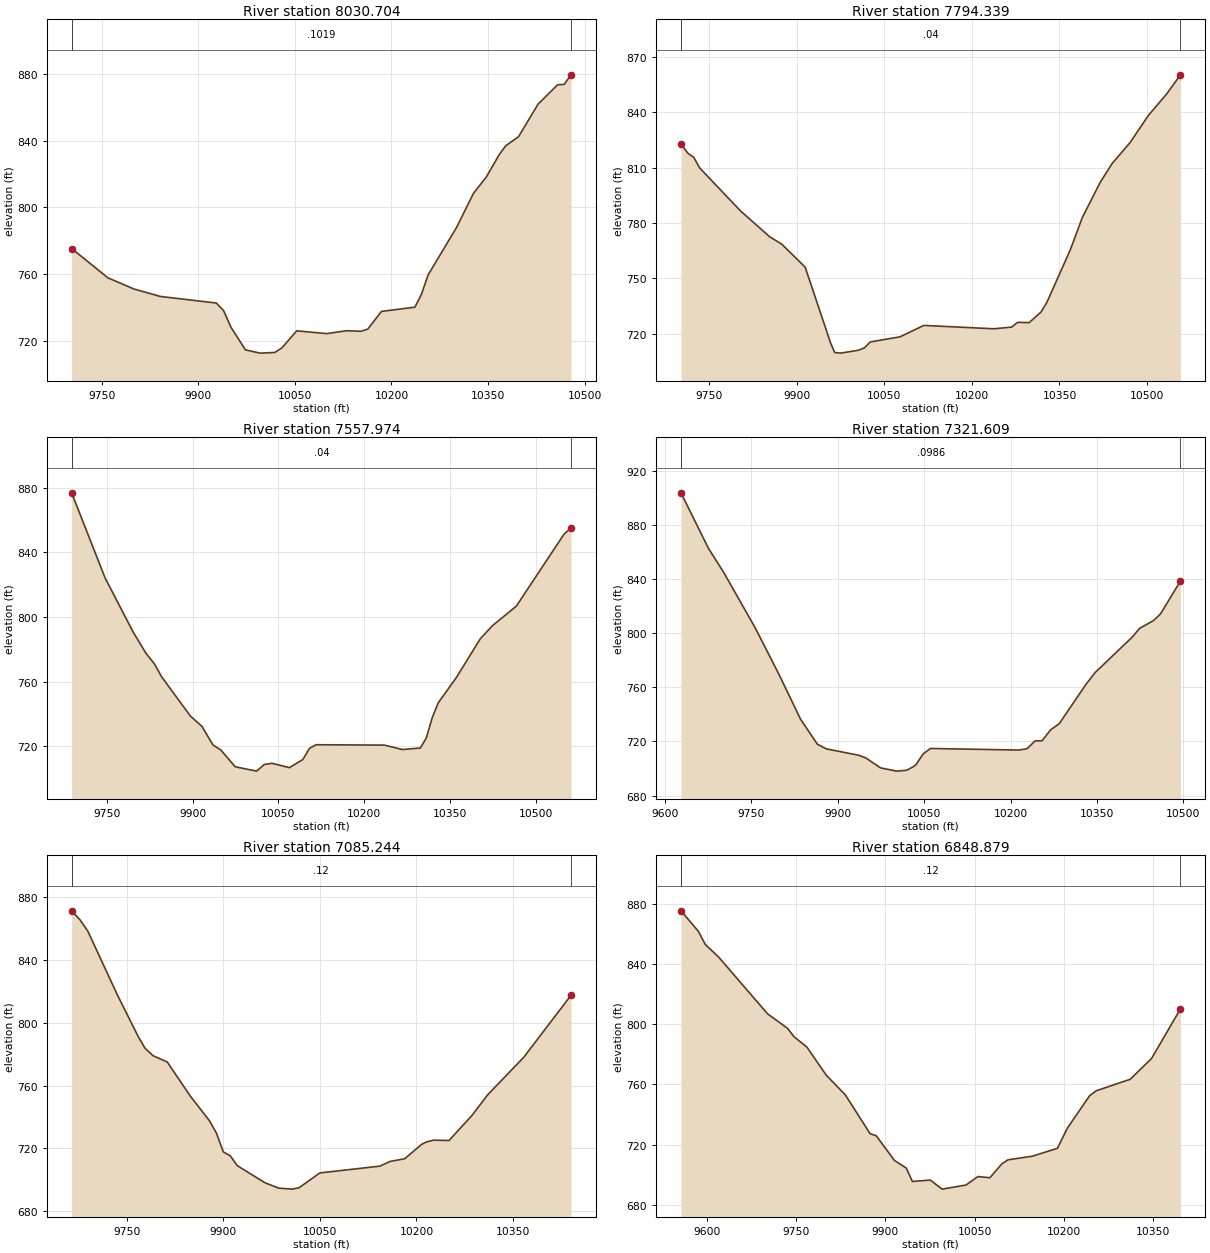
Type RM Length L Ch R = 1 ,8030.704,236.365000,236.365000,236.365000
XS GIS Cut Line= 6
634574.457323304808098.732040032634557.099107559808238.754459107
634427.367131368808504.173912636634400.261341115808585.094616311
634384.334054824808721.365161974634396.100471638808835.812716548
#Sta/Elev= 30
9703.209775.4321 9759.55757.89639799.983751.23559841.228746.76169927.985742.8326
9939.242738.29299950.563728.43679973.204714.84369995.846712.887710018.61  713.27
   10030716.066310052.78 726.20710099.51724.555610130.75 726.30910152.44725.9284
10163.12727.228910184.47 737.82110236.39740.3728 10246.6748.123310256.81759.5675
10300.86787.860810327.41808.433510347.43818.260810367.45831.618810377.46836.8444
10397.47 842.32510427.61861.701110457.92873.319910468.05873.5207   10479879.2732
#Mann= 3 , 0 , 0
9703.209  0.1019       09703.209  0.1019       0   10479  0.1019       0
#XS Ineff= 2 , 0
       0                               0
Bank Sta=9703.209,10479
Exp/Cntr=0.3,0.1

Type RM Length L Ch R = 1 ,7794.339,236.365000,236.365000,236.365000
XS GIS Cut Line= 6
 634288.89690432807983.206154869634297.108579091808135.987966685
634250.696208679808431.866847464634247.090434502808503.169921374
634264.359203269808675.422639566634305.670336118808827.258514537
#Sta/Elev= 30
9701.878 822.8189713.756817.75759723.828 815.544  9733.9 809.8119804.167786.4395
9854.183772.42629874.251768.60159914.475756.11799958.176714.92899965.042709.8591
9975.183 709.52510005.62711.079710015.78712.334710025.98715.599310076.98718.3531
10117.66724.533310238.12722.701410268.15723.621410278.17726.183410298.19726.0734
10318.32731.7659 10328.4  736.9910368.73765.618610389.03782.9097 10419.7802.0196
10440.23812.248410471.02823.616210502.14838.210410533.57849.914510557.11860.2461
#Mann= 3 , 0 , 0
9701.878    0.04       09701.878    0.04       010557.11    0.04       0
#XS Ineff= 2 , 0
       0                               0
Bank Sta=9701.878,10557.11
Exp/Cntr=0.3,0.1

Type RM Length L Ch R = 1 ,7557.974,236.365000,236.365000,236.365000
XS GIS Cut Line= 6
633858.684026394808077.691061267 633984.98072298808248.731296135
634087.089387722808344.574021612634120.548995071808388.138049221
634166.755920413808486.959310077634279.453686046808824.778561151
#Sta/Elev= 30
 9688.25876.82959746.653824.21539796.033790.53579818.398777.44769833.114770.9283
9845.727762.89239896.179738.55869916.311732.21479935.433720.72529949.313717.5938
9974.377707.231910011.78704.527310025.08708.604910038.66709.385110069.24706.6922
10092.69  711.7110104.33718.601710115.72720.8644 10235.3720.636110266.92717.9036
10298.36718.839410308.83725.162210319.29737.883510329.76746.878510361.15762.4052
10403.01786.382510423.94794.428210466.17806.666210549.98851.403110561.99855.0472
#Mann= 3 , 0 , 0
 9688.25    0.04       0 9688.25    0.04       010561.99    0.04       0
#XS Ineff= 2 , 0
       0                               0
Bank Sta=9688.25,10561.99
Exp/Cntr=0.3,0.1

Type RM Length L Ch R = 1 ,7321.609,236.365000,236.365000,236.365000
XS GIS Cut Line= 6
633629.955994794 808224.74273775633857.870340831808438.747833121
633933.160745355808539.055045007634095.934852592808707.958010458
634135.912379338808756.616542795634211.530454689808863.611909683
#Sta/Elev= 30
9628.038903.57319675.582862.67249702.406844.62829756.984803.74449797.684769.8189
9835.582736.34849864.827717.85329880.031  714.489936.674709.7101 9948.83707.7536
9974.522 700.37910002.29698.007710020.05698.666310031.45701.328310035.45702.5304
10048.26710.690210061.06714.751710214.47713.569410228.58714.541110242.69720.3129
10254.75 720.44910269.66728.532610284.57733.065210330.91762.086810346.66770.7362
10411.53797.141210423.95803.4329 10448.5809.334710460.52814.259710494.91838.3827
#Mann= 3 , 0 , 0
9628.038  0.0986       09628.038  0.0986       010494.91  0.0986       0
#XS Ineff= 2 , 0
       0                               0
Bank Sta=9628.038,10494.91
Exp/Cntr=0.3,0.1

Type RM Length L Ch R = 1 ,7085.244,236.365000,236.365000,236.365000
XS GIS Cut Line= 6
 633463.46320266808540.868292492633641.488748348808631.092865749
633824.871698383808702.141452509633974.553459305 808773.52125827
634086.645248803808852.966417235634141.930729018 808905.97696008
#Sta/Elev= 30
9663.921871.21629677.357 865.2629688.992858.3646 9734.86817.85319768.028790.7233
9777.934 783.8259790.456779.02219812.467775.0549 9849.04752.97429878.228737.6148
9889.031729.74429899.835 717.7439910.639715.26149921.443  709.059964.456698.1817
9985.762694.728510007.06694.099610017.74695.024410049.78704.405710143.14708.7325
10159.07711.725910181.64713.415110207.88722.534310215.49724.139810226.81725.2583
10250.65725.049110286.42741.036310310.89754.201210366.85778.016610440.44817.5191
#Mann= 3 , 0 , 0
9663.921    0.12       09663.921    0.12       010440.44    0.12       0
#XS Ineff= 2 , 0
       0                               0
Bank Sta=9663.921,10440.44
Exp/Cntr=0.3,0.1

Type RM Length L Ch R = 1 ,6848.879,236.365000,236.365000,236.365000
XS GIS Cut Line= 6
 633310.47385301808761.555581209633499.435540888808867.282679878
633631.899005466 808906.34142875633887.334432088808934.313834095
634006.200180972808987.822803871634084.205546292809041.526081716
#Sta/Elev= 30
9556.924875.64139586.097862.02829597.826853.19039619.909844.9629  9702.2807.1016
9735.871797.37539746.872791.74449768.277784.92029800.935766.15469832.832753.0937
9874.493727.21689884.799725.85189915.274709.43499935.371704.28299945.419695.4178
9975.482696.35159995.482690.308910035.49693.0442 10055.5698.677210075.62697.8945
10095.83707.152110106.01709.830910147.07712.252510188.98717.481610205.78730.9325
10243.04752.477410254.15755.789210311.35763.480110347.19777.355910395.59810.3202
#Mann= 3 , 0 , 0
9556.924    0.12       09556.924    0.12       010395.59    0.12       0
#XS Ineff= 2 , 0
       0                               0
Bank Sta=9556.924,10395.59
Exp/Cntr=0.3,0.1

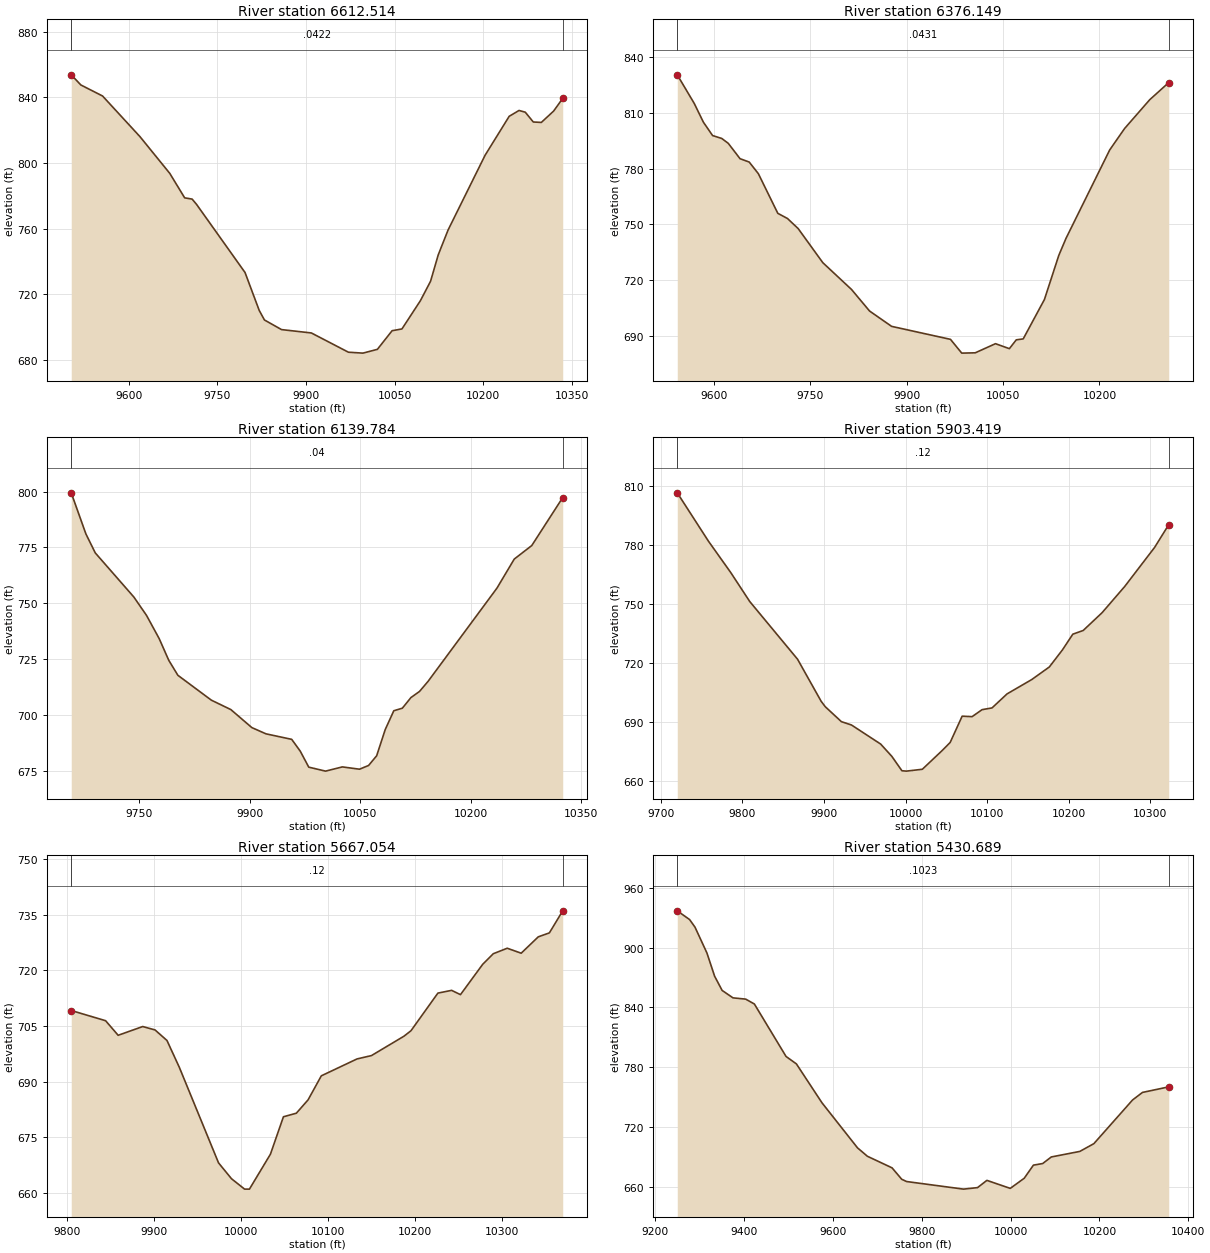
Type RM Length L Ch R = 1 ,6612.514,236.365000,236.365000,236.365000
XS GIS Cut Line= 6
633253.558346457808824.874082244633617.029288245809105.630326598
633681.246753404809151.211482231633784.120878019809236.962977318
 633882.17048563809327.138360991 633900.72811046 809345.99332696
#Sta/Elev= 30
9502.883853.69269519.139847.52449555.856840.80569619.166 816.0519669.602793.6873
 9694.82778.76999707.429778.00629714.876774.82389796.962733.30099820.911710.2591
9829.796704.38929858.738698.53079909.174696.48369971.928684.75829996.415684.2002
10020.94686.507110045.81697.850310062.46 698.92410093.69716.1194 10110.9727.9691
10123.92744.086410140.55759.185110203.21804.748510243.97828.431210260.58 831.989
10271.15 830.93610284.73824.968210298.32 824.70310319.09831.600510334.52839.3457
#Mann= 3 , 0 , 0
9502.883  0.0422       09502.883  0.0422       010334.52  0.0422       0
#XS Ineff= 2 , 0
       0                               0
Bank Sta=9502.883,10334.52
Exp/Cntr=0.3,0.1

Type RM Length L Ch R = 1 ,6376.149,236.364900,236.364900,236.364900
XS GIS Cut Line= 6
633195.764095905808889.170185977633322.738494484809021.143784598
 633392.24805239809117.275407255633441.945487703809219.003102998
633488.220789402809348.912637071633591.307123545809533.222941549
#Sta/Elev= 30
9543.217830.24469569.635814.90419583.889804.84349598.144797.69059612.399796.1276
9622.574793.50379640.908785.26149655.163783.47049669.418777.22249699.639755.9823
9714.754753.18649731.376747.77729769.697729.50389814.428  715.119842.411703.5884
9876.727695.36199968.326688.39479985.846681.009910006.82681.173910038.36686.0751
10059.93683.405710070.72688.1399 10081.5688.646110114.47709.751410136.82733.4049
10147.99742.507310216.09789.999210239.27801.480210278.19816.8532 10307.9826.0942
#Mann= 3 , 0 , 0
9543.217  0.0431       09543.217  0.0431       0 10307.9  0.0431       0
#XS Ineff= 2 , 0
       0                               0
Bank Sta=9543.217,10307.9
Exp/Cntr=0.3,0.1

Type RM Length L Ch R = 1 ,6139.784,236.365000,236.365000,236.365000
XS GIS Cut Line= 6
633042.680804141809059.475348049633085.471313024 809113.21658746
633135.827303798809183.444644154633185.324223145809259.392586446
 633337.99834335 809518.25765488633402.933046966809620.038820313
#Sta/Elev= 30
9657.684799.40989677.529781.09199690.312772.56119742.733752.82399759.894  744.63
9777.055734.2625  9790.1724.55859802.405717.88969847.911 706.7559874.334702.5537
9902.856   694.5 9921.99691.71989956.916689.25379968.559683.97039980.062676.8326
10002.86675.056410025.67676.941810048.95675.9173 10061.3677.588410072.22681.9117
10083.86693.6199 10095.5702.037810107.13703.181810118.77707.931910130.41710.6618
10142.05715.184110235.48756.8128   10259 769.80910282.78775.857210324.77797.2916
#Mann= 3 , 0 , 0
9657.684    0.04       09657.684    0.04       010324.77    0.04       0
#XS Ineff= 2 , 0
       0                               0
Bank Sta=9657.684,10324.77
Exp/Cntr=0.3,0.1

Type RM Length L Ch R = 1 ,5903.419,236.365000,236.365000,236.365000
XS GIS Cut Line= 6
632873.782066455809255.705679467632952.135286671809353.858830684
633055.076489747809494.457268748633141.286384828809617.663544031
633222.061075409 809720.28434148633236.407648389809736.740597497
#Sta/Elev= 30
9720.037806.28229758.184781.77469785.412765.91219808.989751.02859867.499721.7874
9896.535700.35079901.477697.65339921.275690.04359933.645688.35359969.433678.6633
9983.124672.42859995.494665.1062   10001664.910810020.57665.856610044.98675.4111
10054.66 679.46210069.39692.821110081.59692.5821 10093.8696.1345   10106 697.019
10124.43704.138910154.82 711.45410176.28717.822810192.34726.484710205.07734.4793
10217.79736.350810240.95  745.38 10268.7758.702710305.35 778.54110322.71790.1051
#Mann= 3 , 0 , 0
9720.037    0.12       09720.037    0.12       010322.71    0.12       0
#XS Ineff= 2 , 0
       0                               0
Bank Sta=9720.037,10322.71
Exp/Cntr=0.3,0.1

Type RM Length L Ch R = 1 ,5667.054,236.365000,236.365000,236.365000
XS GIS Cut Line= 6
632716.086348078809477.913282648 632800.62658844809560.350969957
632906.056161789809677.206712595632971.968058728809738.919214744
633032.260701064809789.286859251633126.997458546809864.779269284
#Sta/Elev= 30
9804.469709.16759844.005706.41249858.451702.47789886.725704.83999900.862703.9245
9914.603701.08119928.818693.84769973.939668.05579988.886663.7697 10003.9660.9749
10009.51660.971510033.69670.417410048.59680.491810063.48681.458510076.97685.0582
 10092.2 691.543 10133.3696.099410149.88696.999910187.23 702.22410195.33 703.702
10226.32713.858610242.12714.601910252.31713.446210277.88721.631310290.07724.4892
10306.11725.967410322.16724.627810341.82729.0431 10354.6730.109410369.94736.0605
#Mann= 3 , 0 , 0
9804.469    0.12       09804.469    0.12       010369.94    0.12       0
#XS Ineff= 2 , 0
       09901.593                       0
Bank Sta=9804.469,10369.94
Exp/Cntr=0.3,0.1

Type RM Length L Ch R = 1 ,5430.689,236.365000,236.365000,236.365000
XS GIS Cut Line= 6
632072.263443975809476.683249718632282.567472383809619.075437922
  632472.3259549809722.012430991632620.765059394809781.066117652
632914.717332079 809873.96935022 633067.23156732 809946.16261053
#Sta/Elev= 30
9249.062 936.9369276.829928.17419289.041920.52769315.811894.68229333.232871.2676
9350.104857.04319374.529 849.5639403.156848.28969422.737843.39459494.086790.7261
9517.434783.2369 9575.03744.21219654.999699.00139677.349690.51649732.875678.8923
9754.674667.42999765.573 665.1489893.862657.52249925.453659.04039946.513666.3167
9999.163658.268710030.54668.417510051.37 681.621 10072.2683.209210091.59689.8197
10155.86695.388810187.51703.190710274.68747.038210296.96754.606610356.14760.1942
#Mann= 3 , 0 , 0
9249.062  0.1023       09249.062  0.1023       010356.14  0.1023       0
#XS Ineff= 2 , 0
       09871.999                       0
Bank Sta=9249.062,10356.14
Exp/Cntr=0.3,0.1

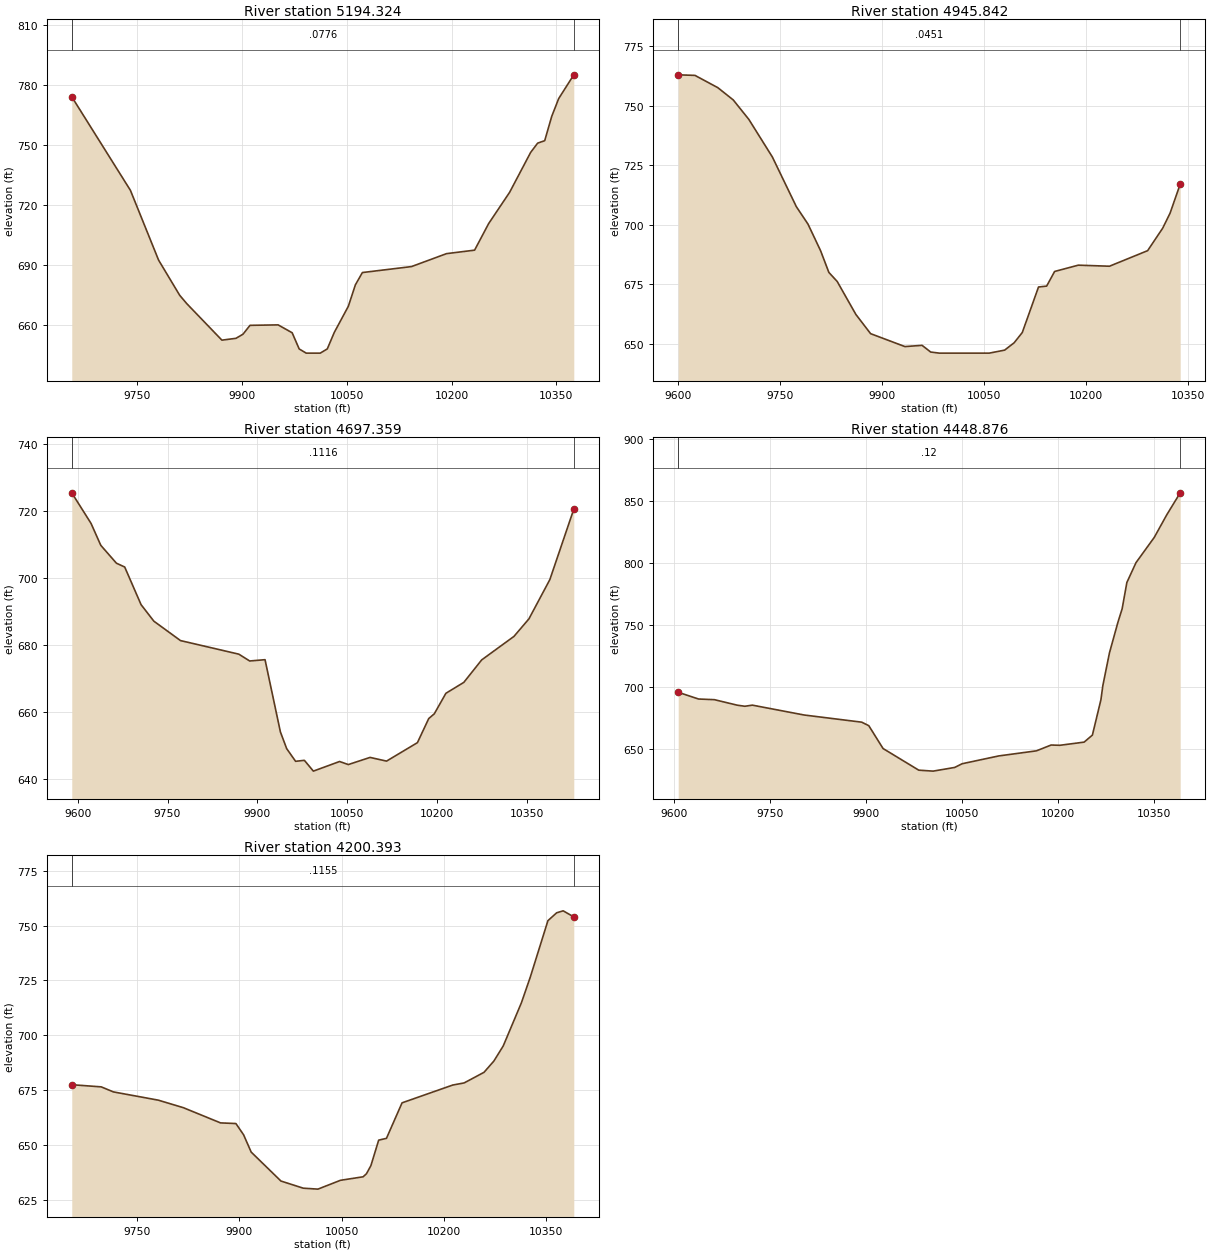
Type RM Length L Ch R = 1 ,5194.324,248.482800,248.482800,248.482800
XS GIS Cut Line= 6
632382.190607292810004.867897561632451.368268186810017.125186915
632553.838351705810030.558694632632722.062617113810049.505268378
632827.574629545810060.756624533633096.503006599810084.914875737
#Sta/Elev= 30
 9656.11774.04739740.114727.38799780.456692.59999810.713675.04029820.798670.8943
9871.134652.6694 9891.26 653.5879901.324655.63279911.387660.0585 9951.64660.2905
9971.766  656.36 9981.83648.28339991.893646.203110012.01646.203110022.07648.3055
10032.12656.549410052.24669.576610062.29680.244410072.35686.387310142.69689.3662
10192.89695.819610233.05697.554810253.13710.778810283.25726.423610313.37746.3325
10323.41750.939710333.45752.137210343.49764.246510353.53773.177310375.12784.9959
#Mann= 3 , 0 , 0
 9656.11  0.0776       0 9656.11  0.0776       010375.12  0.0776       0
#XS Ineff= 2 , 0
       0                               0
Bank Sta=9656.11,10375.12
Exp/Cntr=0.3,0.1

Type RM Length L Ch R = 1 ,4945.842,248.482900,248.482900,248.482900
XS GIS Cut Line= 6
632302.917796809810061.747258756632364.961013548810092.862900803
632487.993890093810166.950072366632630.691620544810273.618127365
632755.601236715810359.365555731632928.210094471810451.436499948
#Sta/Elev= 30
9599.721762.87349624.424 762.6379657.986 757.5039680.697752.35799703.741744.1673
9738.308728.41769773.567707.5994  9790.7700.29199809.234689.13119821.398680.0408
9833.678676.23819861.119662.4301  9882.8654.3646 9933.29648.94879958.543649.4629
 9971.17646.66619983.796646.203110057.44646.203110080.03647.463810093.98650.5466
10105.94654.827610129.85673.9269 10141.8 674.30210153.53680.437910188.38683.0749
10234.21682.638110290.37689.155610312.55698.597410323.39704.886710338.29717.0492
#Mann= 3 , 0 , 0
9599.721  0.0451       09599.721  0.0451       010338.29  0.0451       0
#XS Ineff= 2 , 0
       0                               0
Bank Sta=9599.721,10338.29
Exp/Cntr=0.3,0.1

Type RM Length L Ch R = 1 ,4697.359,248.482900,248.482900,248.482900
XS GIS Cut Line= 6
 632189.46897666810143.148389599632266.770426013810219.923823452
632425.677373356810413.989280377632551.652773088810548.587872656
632652.901274817810644.586707749632776.139540011810737.329142315
#Sta/Elev= 30
9590.115725.39829622.349716.24629638.598709.70689664.677704.36839678.496703.2303
9705.803691.98919727.145687.04959771.633681.24859869.052677.1871 9887.13675.1482
9912.785675.53949938.439653.94499948.888648.96679963.793645.16789978.426645.4706
9993.449642.239610037.23645.1158 10051.8644.200110088.14646.337410115.64645.2321
10167.19650.748610186.06657.945810195.35659.364110214.73665.499710244.62668.7558
10274.54675.485410328.34682.494510353.32687.730110388.24699.460110428.24 720.516
#Mann= 3 , 0 , 0
9590.115  0.1116       09590.115  0.1116       010428.24  0.1116       0
#XS Ineff= 2 , 0
       0                               0
Bank Sta=9590.115,10428.24
Exp/Cntr=0.3,0.1

Type RM Length L Ch R = 1 ,4448.876,248.482900,248.482900,248.482900
XS GIS Cut Line= 6
632055.461154957810239.300894439632136.131566805810359.193321471
632268.614165571810617.522693844632325.350016839 810715.49172851
632415.214624353810830.090038113632481.162320328810891.791270974
#Sta/Elev= 30
9606.569695.77099638.398690.3303 9663.17689.80279698.909685.34479710.732684.4894
9722.554685.37819803.393677.42639893.213671.65979904.369668.83079926.681650.3924
9982.462632.926210004.83632.153210038.68635.127410050.07638.094810107.23644.3927
10166.34648.522510189.26653.214810202.84652.9851 10240.8655.553310253.75661.2286
10267.09689.786510270.05701.104610280.44727.618210293.78752.516810300.25763.1437
10307.59784.320510321.86800.328910350.41820.725310369.84838.853610390.95856.6797
#Mann= 3 , 0 , 0
9606.569    0.12       09606.569    0.12       010390.95    0.12       0
#XS Ineff= 2 , 0
       0                               0
Bank Sta=9606.569,10390.95
Exp/Cntr=0.3,0.1

Type RM Length L Ch R = 1 ,4200.393,0.000000,0.000000,0.000000
XS GIS Cut Line= 6
631849.327106026810370.058563109631939.729083056810506.522666618
632048.347080572810737.349008046632081.411402101810796.859300348
 632164.98951365810899.594528732632255.573863935810973.973708166
#Sta/Elev= 30
9653.755677.43739696.992676.45159714.801674.15779780.711670.39189817.551666.9569
9872.227660.01219894.785659.71469906.064654.58039917.228646.68579960.905633.4837
9993.662630.225410015.21629.793210048.34633.822210081.54635.417810086.48636.8195
10092.98640.516910104.42652.133410115.86652.969110138.74669.163610213.07677.2723
10229.94678.251710259.04683.074910273.59688.2388 10287.3695.121310313.98714.8036
10326.95726.455510352.91752.263110365.76755.869710375.32756.768410390.91754.0025
#Mann= 3 , 0 , 0
9653.755  0.1155       09653.755  0.1155       010390.91  0.1155       0
#XS Ineff= 2 , 0
       0                               0
Bank Sta=9653.755,10390.91
Exp/Cntr=0.3,0.1